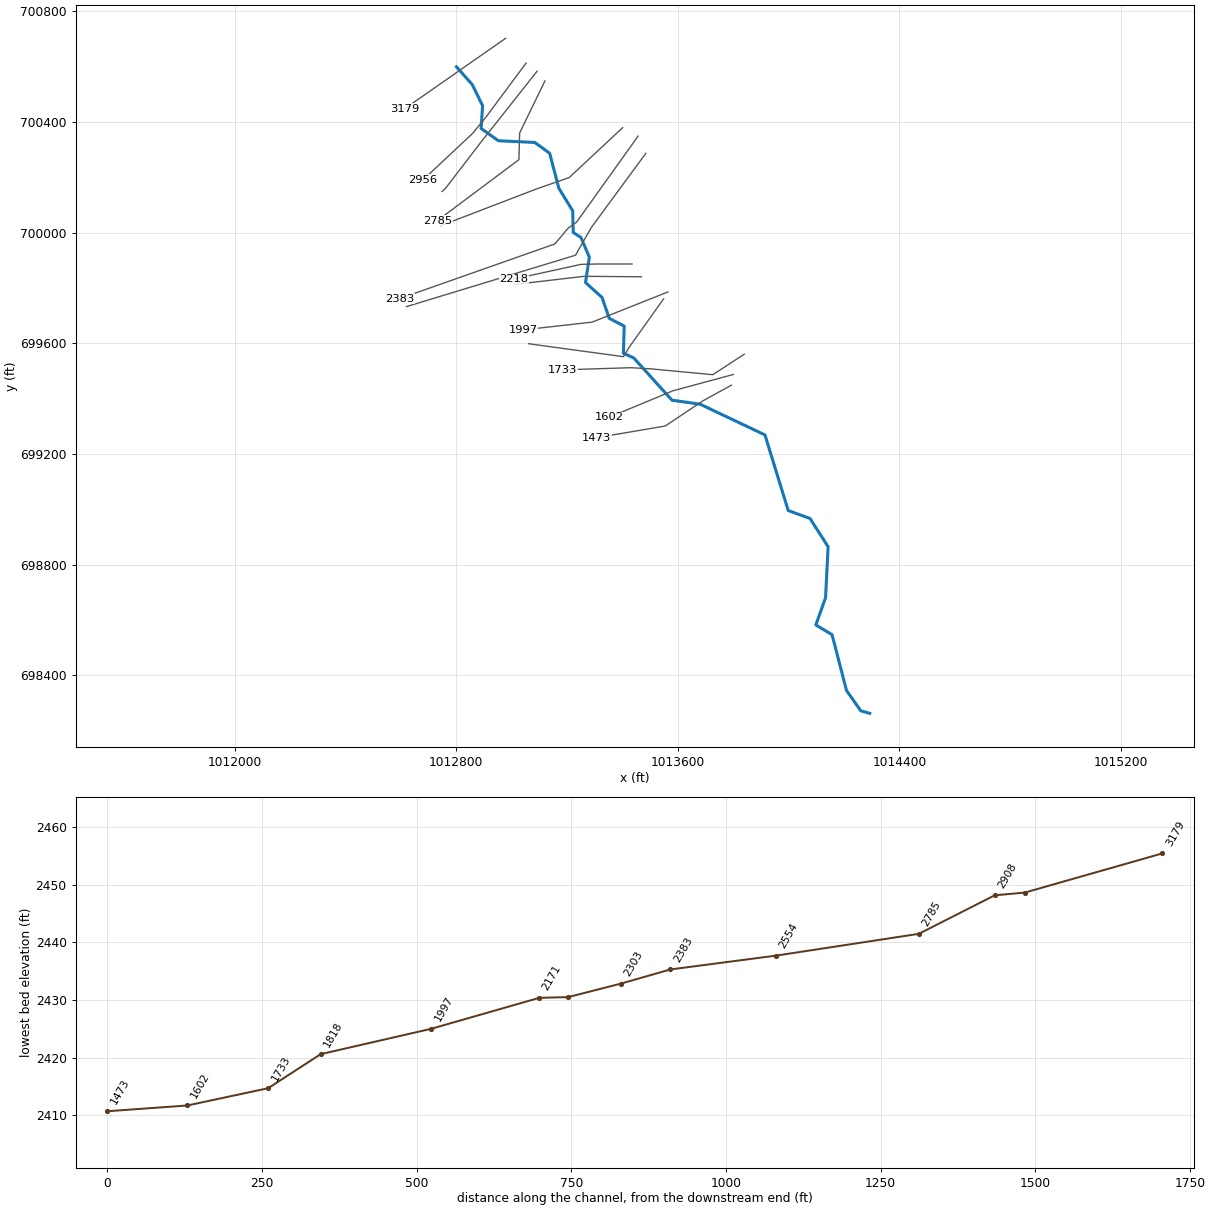
--- lds_flat_crk_trib1.prj (project) ---

Proj Title=lds_flat_crk_trib1
Current Plan=p01
Default Exp/Contr=0.3,0.1
English Units
Geom File=g01
Flow File=f01
Plan File=p01
Y Axis Title=Elevation
X Axis Title(PF)=Main Channel Distance
X Axis Title(XS)=Station
BEGIN DESCRIPTION:
END DESCRIPTION:
DSS Export Rating Curves= 0
DSS Export Rating Curve Sorted= 0
DSS Export Volume Flow Curves= 0
DXF OffsetX= 0
DXF OffsetY= 0
DXF ScaleX= 1
DXF ScaleY= 10

--- lds_flat_crk_trib1.p01 (plan) ---

Plan Title=lds_flat_crk_trib1
Program Version=3.13
Short Identifier=lds_flat_crk
Geom File=g01
Flow File=f01
Subcritical Flow
K Sum by GR= 0
Std Step Tol= 0.01
Critical Tol= 0.01
Num of Std Step Trials= 20
Max Error Tol= 0.3
Flow Tol Ratio= 0.001
Split Flow NTrial= 30
Split Flow Tol= 0.02
Split Flow Ratio= 0.02
Log Output Level= 0
Friction Slope Method= 0
Unsteady Friction Slope Method= 2
Unsteady Bridges Friction Slope Method= 1
Parabolic Critical Depth
Global Vel Dist= 0 , 0 , 0
Global Log Level= 0
CheckData=True
Encroach Param=-1 ,10,10, 2
Encroach River=flat_crk_trib1
Encroach Reach=main
Encroach Node=3179
       4      .7
Encroach Node=2956
       1     245     303
Encroach Node=2908
       4      .7
Encroach Node=2785
       4      .7
Encroach Node=2554
       4      .7
Encroach Node=2383
       1     370     430
Encroach Node=2303
       1   361.5     482
Encroach Node=2218
       4      .7
Encroach Node=2171
       1     158     228
Encroach Node=1997
       4      .7
Encroach Node=1818
       1     212     287
Encroach Node=1733
       1     343     413
Encroach Node=1602
       4      .7
Encroach Node=1473
       4      .7
Encroach Node=1318
       1     103   167.2
Encroach Node=1134
       4      .7
Encroach Node=1036
       1     148     208
Encroach Node=1020
       4      .7
Encroach Node=870
       1     235     290
Encroach Node=791
       1   238.6  270.95
Encroach Node=529
       1     283   315.9
Encroach Node=202
       1   502.5   530.9
Computation Interval=1HOUR
Output Interval=1HOUR
Run HTab= 0
Run UNet= 0
Run PostProcess= 0
UNET Theta= 1
UNET Theta Warmup= 1
UNET ZTol= 0.02
UNET ZSATol= 0.05
UNET MxIter= 20
UNET MaxInSteps= 0
UNET DtIC= 0
UNET DtMin= 0
UNET MaxCRTS= 20
UNET WFStab= 2
UNET SFStab= 1
UNET WFX= 1
UNET SFX= 1
UNET DSS MLevel= 4
UNET DZMax Abort= 100
UNET Convert EG Bridges=-1
UNET Use Existing IB Tables=-1
UNET Froude Reduction=False
UNET Froude Limit= 1
UNET Froude Power= 10
Instantaneous Interval=1HOUR
Write IC File= 0
Echo Input=False
Echo Output=False
Write Detailed= 0
Detailed Automatic Start=False, 10

--- lds_flat_crk_trib1.f01 (steady flow) ---

Flow Title=lds_flat_crk_trib1
Program Version=3.13
Number of Profiles= 2
Profile Names=100-year,FW
River Rch & RM=flat_crk_trib1,main            ,3179
     520     520
Boundary for River Rch & Prof#=flat_crk_trib1,main            , 1
Up Type= 0
Dn Type= 3
Dn Slope=0.013
Boundary for River Rch & Prof#=flat_crk_trib1,main            , 2
Up Type= 0
Dn Type= 3
Dn Slope=0.013
DSS Import GetInterval= 0
DSS Import GetPeak= 0
DSS Import FillOption= 0

--- lds_flat_crk_trib1.g01 (geometry) ---

Geom Title=lds_flat_crk_trib1
Program Version=3.13

River Reach=flat_crk_trib1  ,main
Reach XY= 30
  1012800.651142  700598.7240496  1012857.807392  700534.6407162
 1012895.1303087  700458.2552995 1012889.8594754  700375.8490495
 1012952.4219754  700331.5157161 1013083.7761421  700325.3282161
 1013137.3178088  700286.3802995 1013170.2969755  700160.5052994
 1013220.6511422   700078.046966 1013222.4740588  700000.0052993
 1013249.9011422   699982.515716 1013280.5990589  699911.2657159
 1013266.8698922  699819.2344659 1013326.2344756  699765.8073825
 1013352.5782256  699689.7344658 1013406.3907256  699662.0886325
 1013403.7865589  699563.9427991 1013440.9011423  699546.8698824
  1013578.942809  699394.3594657 1013680.6198924  699379.8594657
 1013914.5886425  699268.8907156 1013998.6198925  698995.8282155
 1014077.4532259  698966.9636322 1014142.6511426  698864.9115488
 1014133.4532259  698681.0990487 1014098.3490592   698582.463632
 1014156.8594759  698547.3594653  1014209.015726  698345.7761319
  1014260.671976  698272.2657152 1014293.1198927  698263.0677985

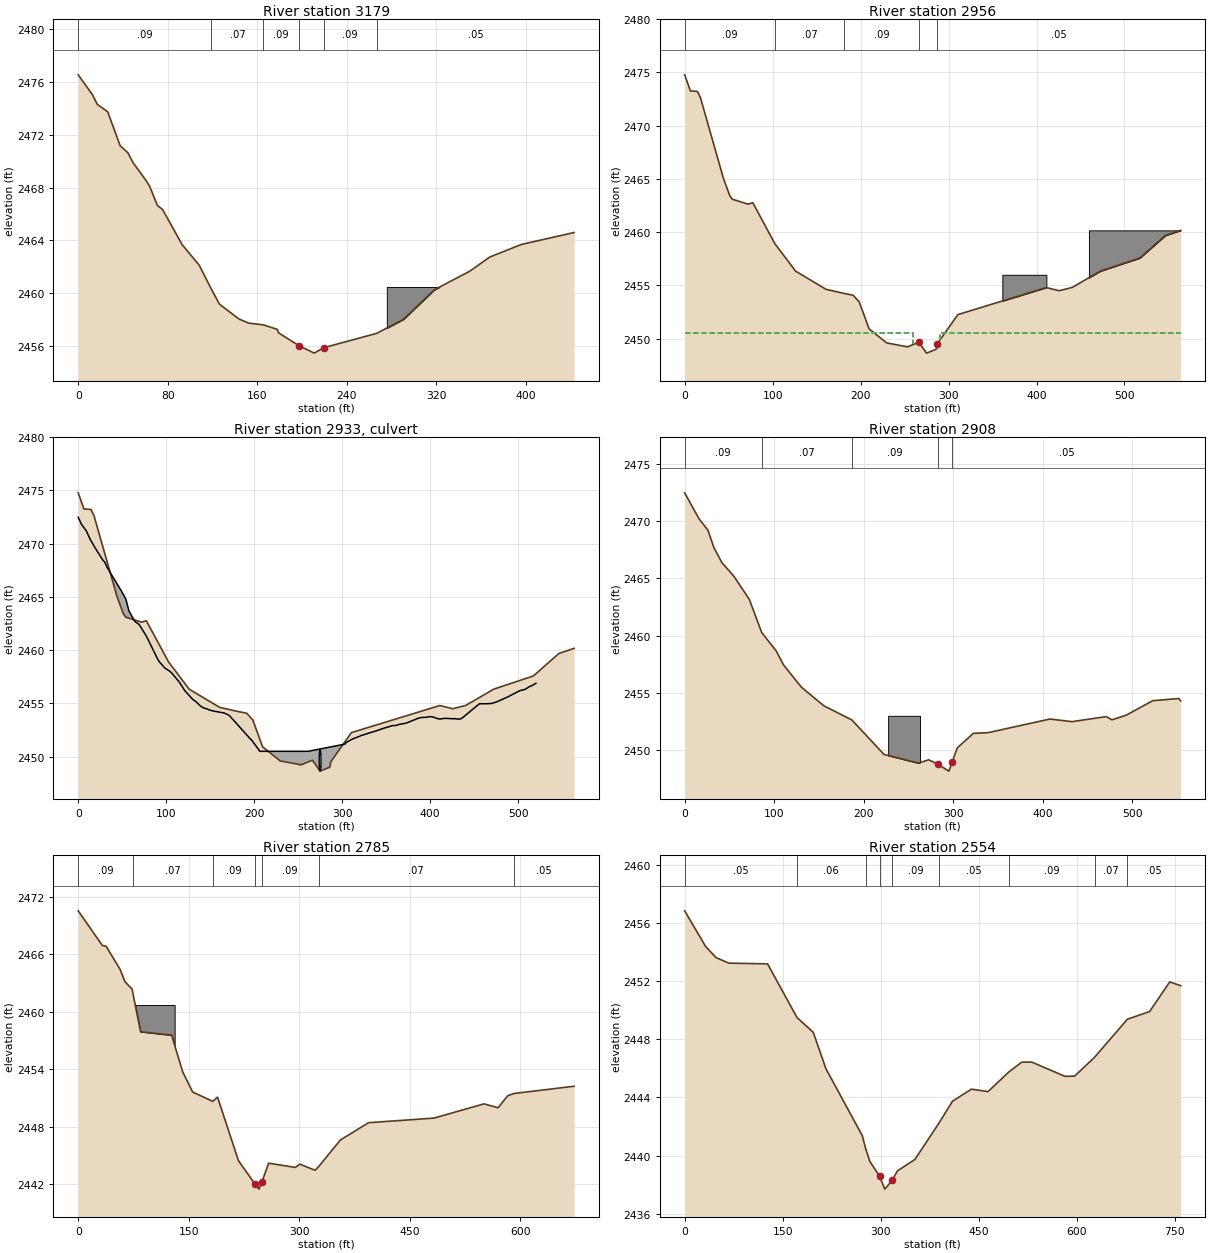
Type RM Length L Ch R = 1 ,3179    ,179.66,222.29,212.52
XS GIS Cut Line= 2
 1012978.1615587  700701.4219663 1012614.6823919  700447.5990495
#Sta/Elev= 30
       0 2476.55   12.77 2475.04   17.01 2474.31   26.35 2473.75   37.52 2471.17
   44.37 2470.64   49.24 2469.86   60.63 2468.54    63.9 2468.09   70.79 2466.64
   75.39 2466.34    92.9 2463.67  108.24  2462.1  119.12 2460.28  126.29 2459.15
  143.52 2458.04  152.26 2457.72  165.63 2457.58  178.01 2457.24  179.09 2456.98
  197.24 2456.01  211.01 2455.44  219.34 2455.85  266.84 2456.94  290.65    2458
  318.27 2460.24  349.94 2461.65  367.94 2462.73  396.07 2463.68  443.33 2464.59
#Mann= 6 ,-1 , 0
       0     .09       0  119.12     .07       0  165.63     .09       0
  197.24     .05       0  219.34     .09       0  266.84     .05       0
#Block Obstruct= 1 ,-1
  275.87  322.812460.459
Bank Sta=197.24,219.34
Exp/Cntr=0.5,0.3

Type RM Length L Ch R = 1 ,2956    ,49.15,48.62,45.17
XS GIS Cut Line= 4
 1013052.2761421  700612.0782163 1012906.0782254  700415.1094662
 1012858.3594753  700357.2344662 1012680.6823919  700190.7344661
#Sta/Elev= 30
       0 2474.78    6.51 2473.27   14.44 2473.22   17.99 2472.62   43.97 2465.08
   51.16 2463.45   54.03  2463.1   72.14 2462.63   77.44 2462.77  102.61 2458.91
  126.13 2456.34  160.77 2454.63  181.66 2454.24  191.49 2454.08  198.47 2453.45
  209.68 2450.92  229.68  2449.6  253.26 2449.23  266.28 2449.66  274.97 2448.64
  286.08 2449.01   287.2 2449.52  310.61 2452.26  411.07  2454.8  425.71  2454.5
  440.54 2454.81  472.43 2456.34   517.5 2457.58  546.44 2459.69  563.81 2460.17
#Mann= 5 ,-1 , 0
       0     .09       0  102.61     .07       0  181.66     .09       0
  266.28     .05       0   287.2     .05       0
#XS Ineff= 2 , 0
       0  259.97  2450.5  289.97       0  2450.5
Permanent Ineff=
       F       F
#Block Obstruct= 2 ,-1
   361.1  411.19    2456  459.56  563.812460.172
Bank Sta=266.28,287.2
Exp/Cntr=0.5,0.3

Type RM Length L Ch R = 2 ,2933    ,,,
BEGIN DESCRIPTION:
Private Driveway
END DESCRIPTION:
Bridge Culvert--1,0,-1,-1, 0
Deck Dist Width WeirC Skew NumUp NumDn MinLoCord MaxHiCord MaxSubmerge Is_Ogee
20,10,2.6,0, 102, 102, , , 0.95, 0, 0,0,,
       0    3.61    7.71    8.95   13.73      16   18.13   23.32   28.37   30.21
   32.81   38.06   49.57   54.17    57.7   61.37   64.59   68.97    70.3   77.85
    88.8   90.75   92.62   93.96   98.51  103.18  105.71  114.93  120.98  130.19
  133.75  138.93  142.68  146.94   147.8  148.79  150.44  156.12  157.42   162.5
  166.29  171.28  171.64  193.99  196.08  196.86  206.51  210.67  211.11   212.8
  220.75  228.17  240.28  249.44   251.7  257.37  261.25  303.49  304.26   305.6
     311  322.97  323.46  324.21  329.17  335.66  339.19  347.73  350.78  351.99
  356.81  361.45  365.21  370.11  371.59  374.45     383  386.72  390.11  395.13
  399.52  402.07     408  410.65  411.39  417.22  418.78  425.64  427.61   432.4
  434.49  436.66  456.16  463.97  470.02  476.42  489.04  502.08  508.05  512.74
  515.58  520.34
 2472.49 2471.83 2471.37 2471.25 2470.39 2470.08 2469.76 2469.07 2468.42 2468.27
 2467.79 2467.06 2465.49  2464.8 2463.68 2463.14 2462.69 2462.43 2462.28 2461.26
 2459.42  2459.1 2458.86 2458.75 2458.32 2458.07 2457.91    2457 2456.22 2455.38
 2455.17 2454.76 2454.57 2454.47 2454.44 2454.39 2454.35 2454.24 2454.23 2454.15
 2454.09 2453.89 2453.88 2451.82 2451.62 2451.59  2450.5  2450.5  2450.5  2450.5
  2450.5  2450.5  2450.5  2450.5  2450.5  2450.5  2450.5 2451.18 2451.32 2451.37
 2451.62 2452.02 2452.03 2452.04 2452.18 2452.34 2452.43 2452.68 2452.75 2452.77
 2452.91 2452.93 2453.04  2453.1 2453.12  2453.2 2453.49 2453.61 2453.68 2453.69
 2453.76 2453.75 2453.59 2453.53 2453.54  2453.6 2453.59 2453.56 2453.57 2453.52
 2453.54 2453.64 2454.97 2454.97 2454.99 2455.17 2455.64  2456.2 2456.32 2456.57
 2456.66 2456.89
                                                                                
                                                                                
                                                                                
                                                                                
                                                                                
                                                                                
                                                                                
                                                                                
                                                                                
                                                                                
                
       0    3.61    7.71    8.95   13.73      16   18.13   23.32   28.37   30.21
   32.81   38.06   49.57   54.17    57.7   61.37   64.59   68.97    70.3   77.85
    88.8   90.75   92.62   93.96   98.51  103.18  105.71  114.93  120.98  130.19
  133.75  138.93  142.68  146.94   147.8  148.79  150.44  156.12  157.42   162.5
  166.29  171.28  171.64  193.99  196.08  196.86  206.51  210.67  211.11   212.8
  220.75  228.17  240.28  249.44   251.7  257.37  261.25  303.49  304.26   305.6
     311  322.97  323.46  324.21  329.17  335.66  339.19  347.73  350.78  351.99
  356.81  361.45  365.21  370.11  371.59  374.45     383  386.72  390.11  395.13
  399.52  402.07     408  410.65  411.39  417.22  418.78  425.64  427.61   432.4
  434.49  436.66  456.16  463.97  470.02  476.42  489.04  502.08  508.05  512.74
  515.58  520.34
 2472.49 2471.83 2471.37 2471.25 2470.39 2470.08 2469.76 2469.07 2468.42 2468.27
 2467.79 2467.06 2465.49  2464.8 2463.68 2463.14 2462.69 2462.43 2462.28 2461.26
 2459.42  2459.1 2458.86 2458.75 2458.32 2458.07 2457.91    2457 2456.22 2455.38
 2455.17 2454.76 2454.57 2454.47 2454.44 2454.39 2454.35 2454.24 2454.23 2454.15
 2454.09 2453.89 2453.88 2451.82 2451.62 2451.59  2450.5  2450.5  2450.5  2450.5
  2450.5  2450.5  2450.5  2450.5  2450.5  2450.5  2450.5 2451.18 2451.32 2451.37
 2451.62 2452.02 2452.03 2452.04 2452.18 2452.34 2452.43 2452.68 2452.75 2452.77
 2452.91 2452.93 2453.04  2453.1 2453.12  2453.2 2453.49 2453.61 2453.68 2453.69
 2453.76 2453.75 2453.59 2453.53 2453.54  2453.6 2453.59 2453.56 2453.57 2453.52
 2453.54 2453.64 2454.97 2454.97 2454.99 2455.17 2455.64  2456.2 2456.32 2456.57
 2456.66 2456.89
                                                                                
                                                                                
                                                                                
                                                                                
                                                                                
                                                                                
                                                                                
                                                                                
                                                                                
                                                                                
                
BR Coef=-1 , 0 , 0 ,, 0 ,,,0.8,-1,,0,
WSPro=,,,, 1 ,,,, 0 ,,,, 0 ,,,,-1 ,-1 ,-1 , 0 , 0 , 0 , 0 , 0
Culvert=1,2,,19,0.027,0.9,1,2,3,2448.64,274.97,2448.17,295.15,Culvert #1  , 0 ,18
Culvert Bottom n=0.027
BC Design=,, 0 ,, 0 ,,,,,,

Type RM Length L Ch R = 1 ,2908    ,94.33,122.8,147.57
XS GIS Cut Line= 4
 1013091.8803088  700582.6302996 1012888.8178087  700325.7657161
  1012761.901142  700160.2761327 1012748.7032253  700148.0886327
#Sta/Elev= 30
       0 2472.47   15.96 2470.21    25.9 2469.22   32.79 2467.67   41.52 2466.38
   55.04 2465.18   72.32 2463.15   85.97 2460.28  102.35 2458.65  110.47 2457.44
  130.53 2455.49  155.54 2453.87  186.74 2452.64   222.6 2449.63  261.11 2448.87
  272.58 2449.16  282.57 2448.78  295.15 2448.17  298.87 2448.99  304.58 2450.21
  322.53 2451.47  339.03 2451.53  408.02 2452.72  432.62 2452.49  470.93 2452.93
  477.33 2452.65   493.6 2453.07  522.74 2454.32  551.96 2454.51  553.95  2454.3
#Mann= 5 ,-1 , 0
       0     .09       0   85.97     .07       0  186.74     .09       0
  282.57     .05       0  298.87     .05       0
#Block Obstruct= 1 ,-1
  227.24  262.83    2453
Bank Sta=282.57,298.87
Exp/Cntr=0.5,0.3

Type RM Length L Ch R = 1 ,2785    ,260.37,231.35,147.82
XS GIS Cut Line= 4
 1013120.3073921  700547.4844662 1013028.9323921  700359.6511328
 1013026.3907254  700263.1927994 1012731.8803086   700042.859466
#Sta/Elev= 30
       0 2470.56   32.85 2466.93   37.82 2466.86   56.82 2464.45   63.46 2463.16
   73.13 2462.38   74.72 2461.77   84.61 2457.93  126.77 2457.57  141.91 2453.72
  155.29 2451.63  182.63 2450.65  189.15 2451.09  217.58 2444.44  239.52 2442.06
  245.44 2441.48  249.55 2442.27  258.46 2444.19  294.68 2443.75  300.78 2444.09
  321.54 2443.45  326.22 2443.82  355.83 2446.61  394.03 2448.42  482.77  2448.9
  550.91 2450.39  569.98 2449.98  582.83 2451.23  591.25 2451.47  673.18 2452.23
#Mann= 7 ,-1 , 0
       0     .09       0   74.72     .07       0  182.63     .09       0
  239.52     .05       0  249.55     .09       0  326.22     .07       0
  591.25     .05       0
#Block Obstruct= 1 ,-1
   77.63   130.92460.724
Bank Sta=239.52,249.55
Exp/Cntr=0.3,0.1

Type RM Length L Ch R = 1 ,2554    ,140.85,170.17,180.65
XS GIS Cut Line= 4
 1013400.7761423  700378.6823828 1013207.8698922  700198.4740494
 1013091.1094754  700157.8594661 1012744.4115586  700024.7552993
#Sta/Elev= 30
       0 2456.84   32.03 2454.39   48.01 2453.62   67.68 2453.24  126.85 2453.19
  171.91  2449.5  196.79 2448.48  216.01 2445.99  271.79 2441.37   276.8 2440.51
  283.36  2439.6  298.33 2438.57  306.31 2437.69  317.48 2438.29  325.69 2438.95
  352.34 2439.73  388.52 2442.19  409.93 2443.74  438.83 2444.57  464.24  2444.4
   496.3 2445.76  516.02 2446.43  531.28 2446.43  582.11 2445.45  596.89 2445.47
  627.45 2446.77  677.47 2449.38  711.52 2449.91  742.33 2451.95  758.98 2451.69
#Mann= 9 ,-1 , 0
       0     .05       0  171.91     .06       0   276.8     .09       0
  298.33     .05       0  317.48     .09       0  388.52     .05       0
   496.3     .09       0  627.45     .07       0  677.47     .05       0
Bank Sta=298.33,317.48
Exp/Cntr=0.5,0.3

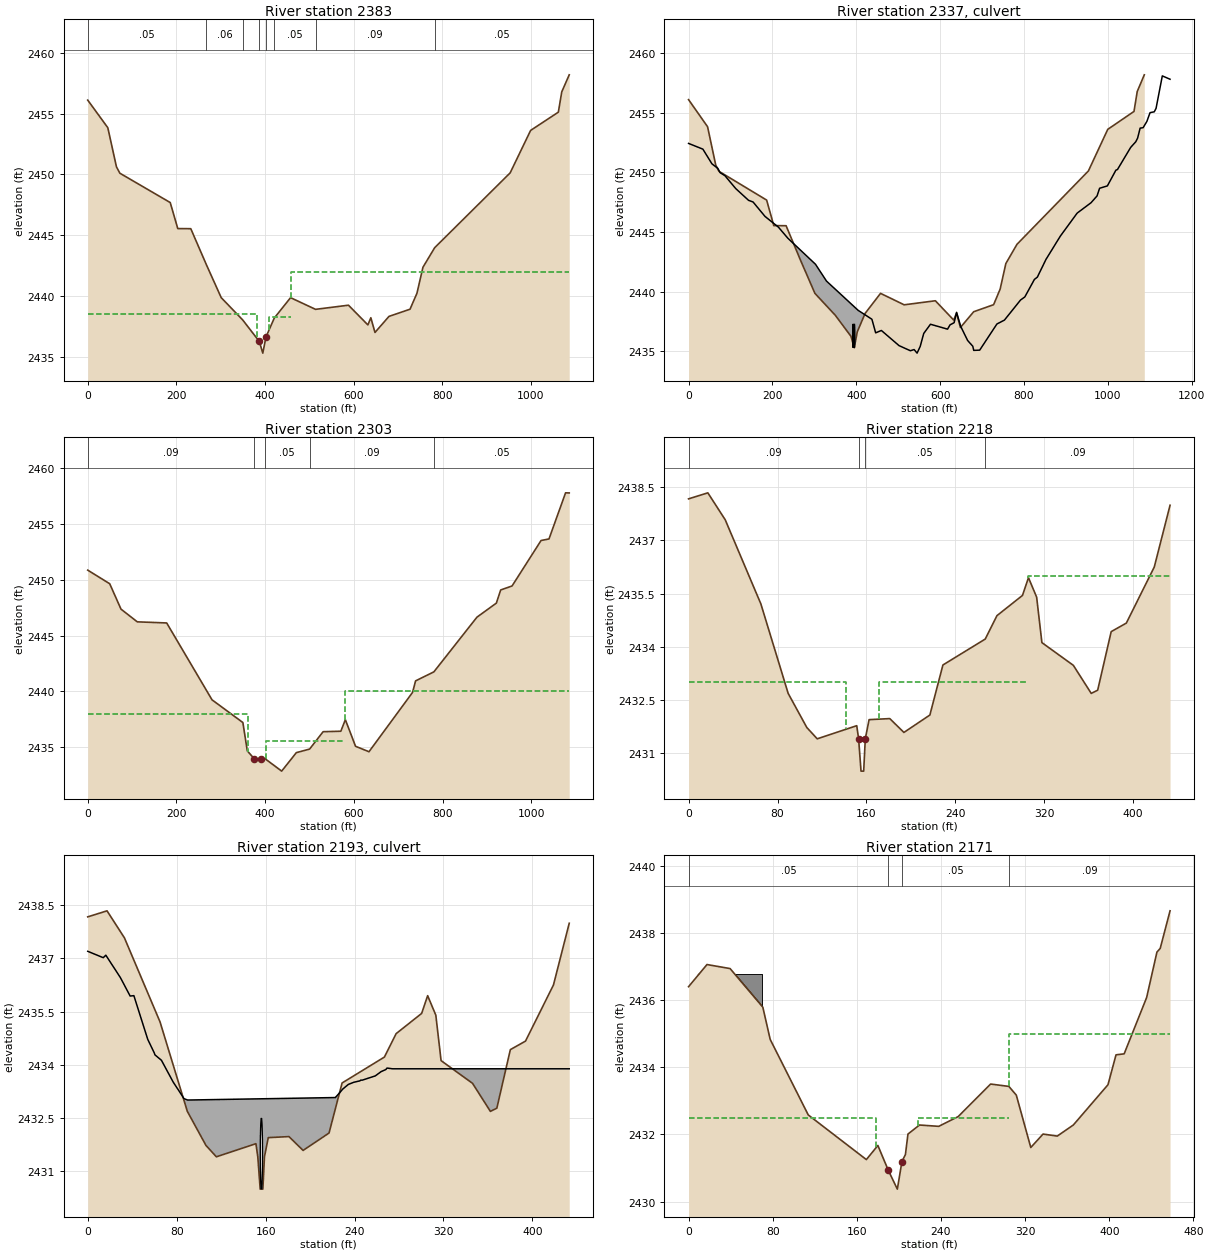
Type RM Length L Ch R = 1 ,2383    ,61.33,80.46,93.08
XS GIS Cut Line= 5
 1013456.6198923  700348.2240495 1013234.5261422   700037.296966
 1013204.0678088  700015.7136327 1013155.8386421   699958.609466
 1012596.8282252  699761.6094659
#Sta/Elev= 30
       0  2456.1   45.33 2453.83   64.86 2450.61   72.58 2450.09   186.2 2447.68
  203.24 2445.54  232.62 2445.53   267.7 2442.58  301.31 2439.86  349.76 2438.03
  387.32 2436.26  395.17  2435.3  402.26 2436.62  421.06 2438.18  457.85 2439.86
  514.21  2438.9  588.57 2439.24   632.4 2437.62  639.08 2438.21   648.4    2437
  680.01 2438.32   727.5 2438.91  743.13 2440.22  756.69 2442.36  783.21 2443.97
  953.56 2450.12  999.76 2453.61 1062.31 2455.11 1070.03 2456.78 1086.89 2458.18
#Mann= 8 ,-1 , 0
       0     .05       0   267.7     .06       0  349.76     .09       0
  387.32     .05       0  402.26     .09       0  421.06     .05       0
  514.21     .09       0  783.21     .05       0
#XS Ineff= 3 ,-1
       0     381  2438.5     409  457.85  2438.3  457.85 1086.89    2442
Permanent Ineff=
       F       F       F
Bank Sta=387.32,402.26
Exp/Cntr=0.5,0.3

Type RM Length L Ch R = 2 ,2337    ,,,
BEGIN DESCRIPTION:
NC 9
END DESCRIPTION:
Bridge Culvert--1,0,-1,-1, 0
Deck Dist Width WeirC Skew NumUp NumDn MinLoCord MaxHiCord MaxSubmerge Is_Ogee
28,22,3,0, 60, 60, , , 0.95, 0, 0.5,0.5,,
       0   34.11   55.72   69.74   75.19   86.89  112.31  143.03  153.83  182.32
  214.32  236.57  302.72  328.97  404.33  437.24  446.22  459.82  501.93  529.01
  537.88  544.98  552.42  560.84  576.92  617.66  623.59  633.32  639.24  649.06
  665.53  677.76  680.16  694.29  735.31  753.33  791.71  801.93  824.84  831.79
  852.45  886.66  926.81  959.96  974.23  980.24  998.85 1019.18 1022.87 1054.48
 1066.54 1070.98 1076.96 1084.08  1093.1 1100.59 1110.68 1114.94 1129.84 1148.32
 2452.43 2451.95 2450.72 2450.34 2449.98 2449.72 2448.65 2447.66 2447.52 2446.31
 2445.41 2444.49  2442.3 2440.89 2438.44 2437.69 2436.55 2436.75 2435.48 2435.05
 2435.15 2434.85 2435.41  2436.5 2437.27 2436.86 2437.22  2437.4 2438.27 2437.09
 2435.91 2435.43 2435.08  2435.1 2437.29 2437.62  2439.3 2439.56 2441.03 2441.22
 2442.71 2444.66 2446.59 2447.46 2448.03 2448.67 2448.87 2450.19 2450.24  2452.1
 2452.57 2452.88 2453.71 2453.75 2454.28 2455.01 2455.08 2455.37 2458.09 2457.81
                                                                                
                                                                                
                                                                                
                                                                                
                                                                                
                                                                                
     -30    -1.9    4.11   25.72   39.74   45.19   56.89   82.31  113.03  123.83
  152.32  159.44   174.3  184.32  260.58  272.72  298.97   425.1  447.92  471.93
  499.01  507.88  514.98  522.42  530.84  546.92  587.66  593.59  603.82  635.53
  723.33  761.71  771.93   789.8  794.84  801.79  822.45  856.66  883.01  896.81
  929.96  944.23  950.24  968.85  989.18  992.87 1024.48 1036.54 1040.98 1046.96
 1054.08  1063.1 1065.51 1070.59 1076.91 1080.68 1084.94 1099.84 1105.36 1118.32
 2452.43  2451.9 2451.95 2450.72 2450.34 2449.98 2449.72 2448.65 2447.66 2447.52
 2446.31 2446.22 2445.63 2445.41 2442.57  2442.3 2440.89 2436.75 2436.28 2435.48
 2435.05 2435.15 2434.85 2435.41  2436.5 2437.27 2436.86 2437.22 2437.44 2436.91
 2437.62  2439.3 2439.56 2440.59 2441.03 2441.22 2442.71 2444.66 2445.81 2446.59
 2447.46 2448.03 2448.67 2448.87 2450.19 2450.24  2452.1 2452.57 2452.88 2453.71
 2453.75 2454.28 2454.64 2455.01 2455.18 2455.08 2455.37 2458.09 2457.88 2457.81
                                                                                
                                                                                
                                                                                
                                                                                
                                                                                
                                                                                
BR Coef=-1 , 0 , 0 ,, 0 ,,,0.8,-1,,0,
WSPro=,,,, 1 ,,,, 0 ,,,, 0 ,,,,-1 ,-1 ,-1 , 0 , 0 , 0 , 0 , 0
Multiple Barrel Culv=1,2,,28,0.027,0.9,1,2,3,2435.3,2433.53, 2,Culvert #1  , 0 ,23
   392.5     380   395.5     383
Culvert Bottom n=0.027
BC Design=,, 0 ,, 0 ,,,,,,

Type RM Length L Ch R = 1 ,2303    ,132.62,84.85,35.71
XS GIS Cut Line= 5
  1013484.536559  700286.0365495 1013287.8282255  700018.2552993
 1013245.9428089  699944.6511326 1013230.7136422  699917.9948826
 1012620.4948919  699732.3698825
#Sta/Elev= 30
       0 2450.87   49.55 2449.65   74.98 2447.37  111.69 2446.23  177.98 2446.13
   280.2 2439.23  349.78 2437.19  359.69 2434.65  375.84 2433.92   391.2 2433.92
  398.91 2433.97  437.19 2432.83  470.32 2434.49  500.19 2434.81  530.67 2436.37
  570.58 2436.41  580.77 2437.45  603.75 2435.06  634.04 2434.57  732.34  2439.9
  739.08 2440.93  780.35 2441.74  877.46 2446.65  921.17 2447.91  930.96 2449.09
   956.6 2449.45    1022 2453.53 1039.86 2453.67 1077.22 2457.81 1085.48  2457.8
#Mann= 5 ,-1 , 0
       0     .09       0  375.84     .05       0  398.91     .05       0
  500.19     .09       0  780.35     .05       0
#XS Ineff= 3 ,-1
       0   361.5    2438   401.5  580.77  2435.5  580.77 1085.48    2440
Permanent Ineff=
       F       F       F
Bank Sta=375.84,391.2
Exp/Cntr=0.5,0.3

Type RM Length L Ch R = 1 ,2218    ,49.01,46.75,41.69
XS GIS Cut Line= 4
 1013434.6823923  699886.3594659 1013310.6719755  699886.2657159
 1013251.0261422  699884.9948826 1013007.3490587  699831.6927992
#Sta/Elev= 30
       0 2438.17   17.34 2438.34   32.99 2437.58   65.05 2435.21   89.59 2432.69
  106.35 2431.73  115.72 2431.41  151.27 2431.78  152.97 2431.41  155.13  2430.5
  157.53  2430.5  158.97 2431.41  162.39 2431.95  180.98 2431.98  193.71 2431.59
  217.06 2432.08  228.79 2433.49  266.84 2434.22   277.4 2434.88  300.36 2435.45
  305.76 2435.95  313.11  2435.4  317.84 2434.12  346.13 2433.48   362.2 2432.69
     368 2432.78  380.16 2434.43  393.78 2434.67  418.91 2436.25  433.11 2437.99
#Mann= 4 ,-1 , 0
       0     .09       0  152.97     .05       0  158.97     .05       0
  266.84     .09       0
#XS Ineff= 3 ,-1
       0   141.2 2433.01   171.2  305.76 2433.01  305.76  433.11    2436
Permanent Ineff=
       F       F       F
Bank Sta=152.97,158.97
Exp/Cntr=0.5,0.3

Type RM Length L Ch R = 2 ,2193    ,,,
BEGIN DESCRIPTION:
Private Drive
END DESCRIPTION:
Bridge Culvert--1,0,-1,-1, 0
Deck Dist Width WeirC Skew NumUp NumDn MinLoCord MaxHiCord MaxSubmerge Is_Ogee
16,8,3,0, 29, 29, , , 0.95, 0, 0.5,0.5,,
       0   13.93   16.27   29.35   38.13    41.5   53.96    59.8   60.52   66.29
   76.96   82.45   86.55   89.83  222.84     223  227.03  229.43  234.44  239.28
  244.82  245.49  246.96  258.66  263.88   268.2  269.19  274.23  433.11
  2437.2 2437.02 2437.09 2436.46 2435.94 2435.95 2434.72 2434.34 2434.28 2434.13
 2433.51 2433.25 2433.05 2433.01 2433.08 2433.09 2433.23 2433.32 2433.45 2433.51
 2433.55 2433.57 2433.57 2433.69 2433.81 2433.87 2433.91 2433.89 2433.89
                                                                                
                                                                                
                                                                        
       0   13.93   16.27   29.35   38.13    41.5   53.96    59.8   60.52   66.29
   76.96   82.45   86.55   89.83  222.84     223  227.03  229.43  234.44  239.28
  244.82  245.49  246.96  258.66  263.88   268.2  269.19  274.23   457.8
  2437.2 2437.02 2437.09 2436.46 2435.94 2435.95 2434.72 2434.34 2434.28 2434.13
 2433.51 2433.25 2433.05 2433.01 2433.08 2433.09 2433.23 2433.32 2433.45 2433.51
 2433.55 2433.57 2433.57 2433.69 2433.81 2433.87 2433.91 2433.89 2433.89
                                                                                
                                                                                
                                                                        
BR Coef=-1 , 0 , 0 ,, 0 ,,,0.8,-1,,0,
WSPro=,,,, 1 ,,,, 0 ,,,, 0 ,,,,-1 ,-1 ,-1 , 0 , 0 , 0 , 0 , 0
Culvert=1,2,,12,0.027,0.9,1,2,3,2430.5,156.2,2430.37,198,Culvert #1  , 0 ,14
Culvert Bottom n=0.027
BC Design=,, 0 ,, 0 ,,,,,,

Type RM Length L Ch R = 1 ,2171    ,135.63,174.66,178.79
XS GIS Cut Line= 3
  1013468.536559  699840.0886326 1013262.4428089  699841.8490492
 1013012.4323921  699812.6615492
#Sta/Elev= 30
       0  2436.4   17.51 2437.06   39.47 2436.94   70.61 2435.79   77.61 2434.83
  113.81 2432.58  169.05 2431.25  180.01 2431.67  189.93 2430.93   198.5 2430.37
  202.86 2431.19   206.2  2431.4  208.61 2432.01  219.56 2432.28  237.88 2432.24
  256.33 2432.53  287.19  2433.5  304.54 2433.43  311.62 2433.17   325.4 2431.61
  337.04 2432.01  350.58 2431.95  365.84 2432.28  398.79 2433.48  406.43 2434.37
  414.18  2434.4  435.57 2436.08  445.32 2437.43  448.44 2437.54  457.81 2438.66
#Mann= 4 ,-1 , 0
       0     .05       0  189.93     .05       0  202.86     .05       0
  304.54     .09       0
#XS Ineff= 3 ,-1
       0     178  2432.5     218  304.54  2432.5  304.54  457.81    2435
Permanent Ineff=
       F       F       F
#Block Obstruct= 1 ,-1
    9.27   69.712436.771
Bank Sta=189.93,202.86
Exp/Cntr=0.5,0.3

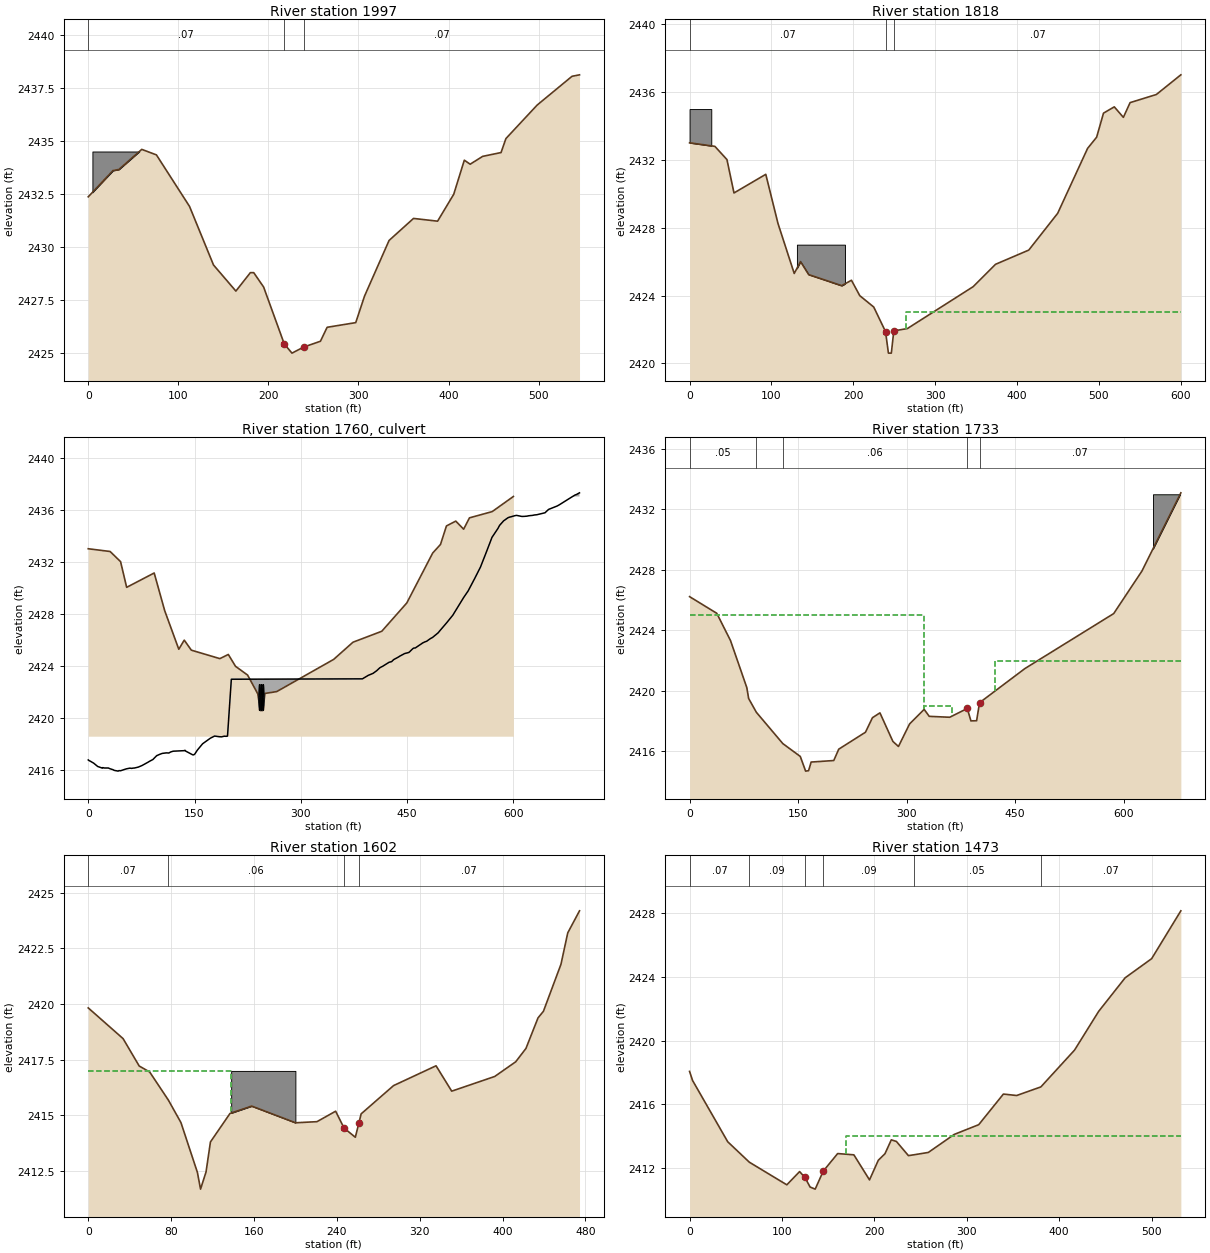
Type RM Length L Ch R = 1 ,1997    ,106.33,178.67,139.3
XS GIS Cut Line= 3
 1013564.4948923  699785.3698826 1013290.3698922  699676.2344658
 1013041.6198921  699648.3073825
#Sta/Elev= 30
       0 2432.38   27.54 2433.62   34.02 2433.67   59.44 2434.62    75.7 2434.36
  112.42 2431.93  139.09 2429.16  163.91 2427.93     180  2428.8  183.72  2428.8
  194.72 2428.12  217.64 2425.43  226.19    2425  239.36 2425.29  257.75 2425.56
  265.21 2426.22  296.95 2426.44  306.69 2427.69  333.97 2430.32  361.09 2431.36
  387.81 2431.23  405.73  2432.5  417.49 2434.11  423.98 2433.92  437.85 2434.29
  458.26 2434.47  463.67 2435.13  498.28 2436.71  537.02 2438.07  545.36 2438.14
#Mann= 3 , 0 , 0
       0     .07       0  217.64     .05       0  239.36     .07       0
#Block Obstruct= 1 ,-1
    4.64   64.48 2434.52
Bank Sta=217.64,239.36
Exp/Cntr=0.5,0.3

Type RM Length L Ch R = 1 ,1818    ,151.05,84.93,54.93
XS GIS Cut Line= 4
  1013548.755309  699760.3907159 1013425.9011423  699587.7657158
 1013403.7344756  699551.5157158 1013061.2344754  699598.2761325
#Sta/Elev= 30
       0 2433.01    30.9  2432.8   45.65 2432.02   54.26 2430.05   93.09 2431.15
  107.99 2428.25  127.83  2425.3  135.51    2426  145.52 2425.23  185.82 2424.58
  197.71  2424.9   207.9 2423.99  224.93 2423.32  239.36 2421.87  242.87  2420.6
  246.44  2420.6  249.44 2421.91  266.05 2422.05  346.36 2424.52  373.67 2425.84
  414.32 2426.68  449.61 2428.85  486.15 2432.68  497.18 2433.34  505.58 2434.76
  518.76 2435.13  529.85 2434.51  538.06 2435.38  570.16 2435.86  600.05 2437.02
#Mann= 3 ,-1 , 0
       0     .07       0  239.36     .05       0  249.44     .07       0
#XS Ineff= 2 , 0
       0   224.5    2423   264.5       0    2423
Permanent Ineff=
       F       F
#Block Obstruct= 2 ,-1
       0   26.51    2435  131.11  189.78    2427
Bank Sta=239.36,249.44
Exp/Cntr=0.5,0.3

Type RM Length L Ch R = 2 ,1760    ,,,
BEGIN DESCRIPTION:
Seventh Street
Note: Imagery shows two structures in this location (Seventh Street and a Private Driveway).  Due to the close proximity of both structures, they were modeled as one.
END DESCRIPTION:
Bridge Culvert--1,0,-1,-1, 0
Deck Dist Width WeirC Skew NumUp NumDn MinLoCord MaxHiCord MaxSubmerge Is_Ogee
15,55,2.6,0, 139, 84, , , 0.95, 0, 0.5,0.5,,
       0     .98    1.55    1.71    2.74    7.03    7.73   13.27   19.92   20.59
   22.69   28.38   30.88   34.99   36.59   42.27   43.35   45.67   53.48   58.75
   61.41   62.99   65.37   70.72   75.92   79.33   83.94   86.37   91.26   95.22
   96.87   97.24  100.96  104.47  110.26  113.73  116.37  119.97  135.56  136.53
  137.45  147.45  148.95  150.53  154.12  161.46   168.8  172.46   176.8  178.32
  184.88  188.25   192.1   193.7   194.7  196.57  201.98  386.99  392.73  394.62
   395.3     402  407.27  411.36  413.88  415.48  424.58  428.16  431.23  433.42
  437.09  439.99  446.45  446.58  452.35   453.1  458.23   459.5  461.63  466.24
  468.75  472.22  474.92  477.58  482.41  486.05  492.09  492.92  493.86  496.73
   505.1  509.54  512.64  514.52  518.36  521.99  527.17  529.87  536.15  537.62
  545.55  545.59  545.65  553.63  560.47  561.65  569.88  569.97  570.43  578.29
  580.53  586.25  592.48   594.3  597.23   602.4  604.52  611.17  611.89  614.35
  618.02  619.08  621.69  627.06  629.69  633.23  644.68  649.36   650.2  652.17
  661.87  664.84  678.47  680.36  681.37  682.44   687.3  688.58  693.38
 2416.81 2416.77 2416.75 2416.74 2416.72 2416.59 2416.56 2416.31 2416.18 2416.22
 2416.19 2416.19 2416.13 2416.06 2416.01 2415.95 2415.99 2415.98 2416.12 2416.18
 2416.16 2416.18 2416.19 2416.26 2416.38 2416.48 2416.62  2416.7 2416.84 2417.06
 2417.15 2417.15 2417.24 2417.31 2417.35 2417.34 2417.42 2417.48 2417.52 2417.55
 2417.49  2417.2  2417.2 2417.27 2417.57 2418.05 2418.33 2418.48  2418.6 2418.64
 2418.59 2418.58 2418.63 2418.62 2418.62 2418.64    2423 2423.03 2423.22 2423.29
  2423.3 2423.45 2423.66 2423.87 2423.95 2423.99  2424.3 2424.35 2424.51 2424.57
 2424.68 2424.78 2424.97 2424.97 2425.05 2425.08 2425.35 2425.39  2425.4 2425.57
 2425.67 2425.79 2425.86 2425.91  2426.1 2426.21 2426.48 2426.52 2426.56 2426.75
 2427.28 2427.58  2427.8 2427.91 2428.25 2428.56 2429.03 2429.27 2429.77 2429.92
 2430.74 2430.74 2430.75 2431.61 2432.54 2432.72 2433.89  2433.9 2433.93 2434.57
  2434.8 2435.15 2435.39 2435.43 2435.47 2435.55 2435.57 2435.49 2435.49 2435.49
  2435.5 2435.51 2435.54 2435.57  2435.6 2435.62 2435.77 2436.01 2436.04 2436.08
 2436.29 2436.38 2436.85 2436.92 2436.96 2436.98 2437.14 2437.16  2437.3
                                                                                
                                                                                
                                                                                
                                                                                
                                                                                
                                                                                
                                                                                
                                                                                
                                                                                
                                                                                
                                                                                
                                                                                
                                                                                
                                                                        
       0  201.98  386.99  392.73  394.62   395.3     402  407.27  411.36  413.88
  415.48  424.58  428.16  431.23  433.42  437.09  439.99  446.45  446.58  452.35
   453.1  458.23   459.5  461.63  466.24  468.75  472.22  474.92  477.58  482.41
  486.05  492.09  492.92  493.86  496.73   505.1  509.54  512.64  514.52  518.36
  521.99  527.17  529.87  536.15  537.62  545.55  545.59  545.65  553.63  560.47
  561.65  569.88  569.97  570.43  578.29  580.53  586.25  592.48   594.3  597.23
   602.4  604.52  611.17  611.89  614.35  618.02  619.08  621.69  627.06  629.69
  633.23  644.68  649.36   650.2  652.17  661.87  664.84  678.47  680.36  681.37
  682.44   687.3  688.58  693.38
    2420    2420 2423.03 2423.22 2423.29  2423.3 2423.45 2423.66 2423.87 2423.95
 2423.99  2424.3 2424.35 2424.51 2424.57 2424.68 2424.78 2424.97 2424.97 2425.05
 2425.08 2425.35 2425.39  2425.4 2425.57 2425.67 2425.79 2425.86 2425.91  2426.1
 2426.21 2426.48 2426.52 2426.56 2426.75 2427.28 2427.58  2427.8 2427.91 2428.25
 2428.56 2429.03 2429.27 2429.77 2429.92 2430.74 2430.74 2430.75 2431.61 2432.54
 2432.72 2433.89  2433.9 2433.93 2434.57  2434.8 2435.15 2435.39 2435.43 2435.47
 2435.55 2435.57 2435.49 2435.49 2435.49  2435.5 2435.51 2435.54 2435.57  2435.6
 2435.62 2435.77 2436.01 2436.04 2436.08 2436.29 2436.38 2436.85 2436.92 2436.96
 2436.98 2437.14 2437.16  2437.3
                                                                                
                                                                                
                                                                                
                                                                                
                                                                                
                                                                                
                                                                                
                                                                                
                                
BR Coef=-1 , 0 , 0 ,, 0 ,,,0.8,-1,,0,
WSPro=,,,, 1 ,,,, 0 ,,,, 0 ,,,,-1 ,-1 ,-1 , 0 , 0 , 0 , 0 , 0
Multiple Barrel Culv=1,2,,62,0.027,0.9,1,2,3,2420.6,2417.93, 3,Culvert #1  , 0 ,10
     242     390   244.5   392.5     247     395
Culvert Bottom n=0.027
BC Design=,, 0 ,, 0 ,,,,,,

Type RM Length L Ch R = 1 ,1733    ,110.49,130.62,155.29
XS GIS Cut Line= 5
 1013840.0990591  699560.5469658 1013726.3073924  699486.4219657
 1013499.3073923  699507.8282158 1013430.9636423  699511.6719658
 1013184.4740588  699503.9844658
#Sta/Elev= 30
       0 2426.22   37.57 2425.12   56.55 2423.32    79.1 2420.21   81.63 2419.49
   92.26 2418.58  128.85 2416.51     153 2415.66  160.38 2414.69  164.47 2414.72
  167.98 2415.29  199.27 2415.39  206.12 2416.14  243.06 2417.26  252.71 2418.22
  263.06 2418.54  280.99 2416.65  288.67 2416.32  304.04 2417.81  324.17 2418.77
  331.18 2418.31  359.48 2418.25  383.75 2418.83  388.77 2418.01  396.65 2418.02
  400.67 2419.21  463.45 2421.47  586.06  2425.1  625.08 2427.91  678.87 2433.08
#Mann= 5 ,-1 , 0
       0     .05       0   92.26     .07       0  128.85     .06       0
  383.75     .05       0  400.67     .07       0
#XS Ineff= 3 ,-1
       0  324.17    2425  324.17   362.5    2419   422.5  678.87    2422
Permanent Ineff=
       F       F       F
#Block Obstruct= 1 ,-1
  640.35  677.742432.984
Bank Sta=383.75,400.67
Exp/Cntr=0.5,0.3

Type RM Length L Ch R = 1 ,1602    ,90.32,129.29,128.08
XS GIS Cut Line= 3
 1013800.2136424  699487.1719657 1013582.3698923  699428.2969657
 1013352.7448922   699332.911549
#Sta/Elev= 30
       0 2419.83   33.65 2418.45   49.22 2417.22   59.34 2416.95   77.36 2415.69
   89.51 2414.68  105.41 2412.44  108.44 2411.69  113.73 2412.46     118 2413.81
   136.9 2415.09  157.78 2415.42  200.15 2414.67  220.84 2414.72  238.87 2415.19
  247.03 2414.43  257.87 2414.02  261.28 2414.65  263.48 2415.07  294.77 2416.34
   335.8 2417.23  350.93 2416.09  392.45 2416.75  412.73 2417.41  422.61 2418.01
  434.24 2419.38  439.49 2419.68  456.42 2421.79  462.96  2423.2  474.31 2424.19
#Mann= 4 ,-1 , 0
       0     .07       0   77.36     .06       0  247.03     .05       0
  261.28     .07       0
#XS Ineff= 2 , 0
       0     138    2417               0
Permanent Ineff=
       F       F
#Block Obstruct= 1 ,-1
     138     200    2417
Bank Sta=247.03,261.28
Exp/Cntr=0.3,0.1

Type RM Length L Ch R = 1 ,1473    ,132.96,155.38,189.41
XS GIS Cut Line= 4
 1013793.4532258  699448.6302991 1013689.0678091   699391.036549
  1013554.692809  699301.0469657 1013307.5261422  699259.0573823
#Sta/Elev= 30
       0 2418.07    3.27  2417.5   41.29 2413.66   64.65 2412.38  105.24 2410.96
  119.07 2411.79  124.82 2411.42  130.46 2410.82  135.95 2410.69  144.68 2411.82
  160.27 2412.92  177.82 2412.84  194.72 2411.27  204.25  2412.5  211.46 2412.91
  218.31 2413.78  223.81 2413.68  236.85 2412.79  242.49 2412.84  258.38 2412.99
  286.38 2414.12  312.91 2414.73  339.59 2416.65  353.97 2416.56  380.18  2417.1
  416.65 2419.41  442.64 2421.83  471.36 2423.94  500.04 2425.14  531.65 2428.14
#Mann= 6 ,-1 , 0
       0     .07       0   64.65     .09       0  124.82     .05       0
  144.68     .09       0  242.49     .05       0  380.18     .07       0
#XS Ineff= 2 , 0
       0                  168.84       0    2414
Permanent Ineff=
       F       F
Bank Sta=124.82,144.68
Exp/Cntr=0.3,0.1