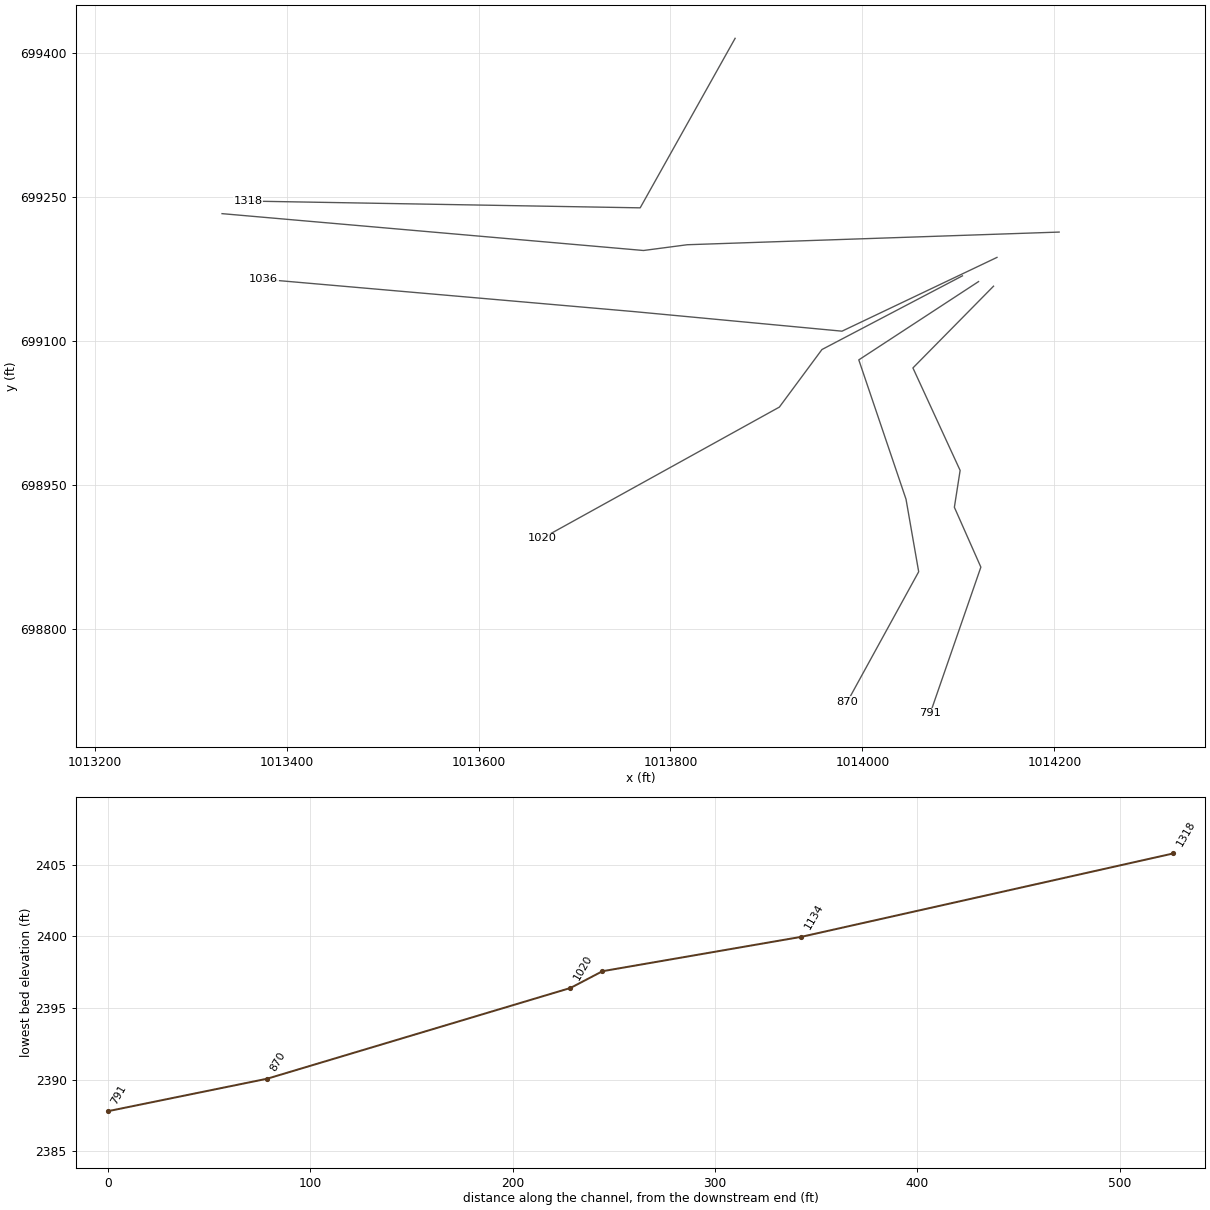
HEC-RAS study lds_flat_crk_trib1.prj: lds_flat_crk_trib1

--- lds_flat_crk_trib1.g01 (geometry) --- (continued)

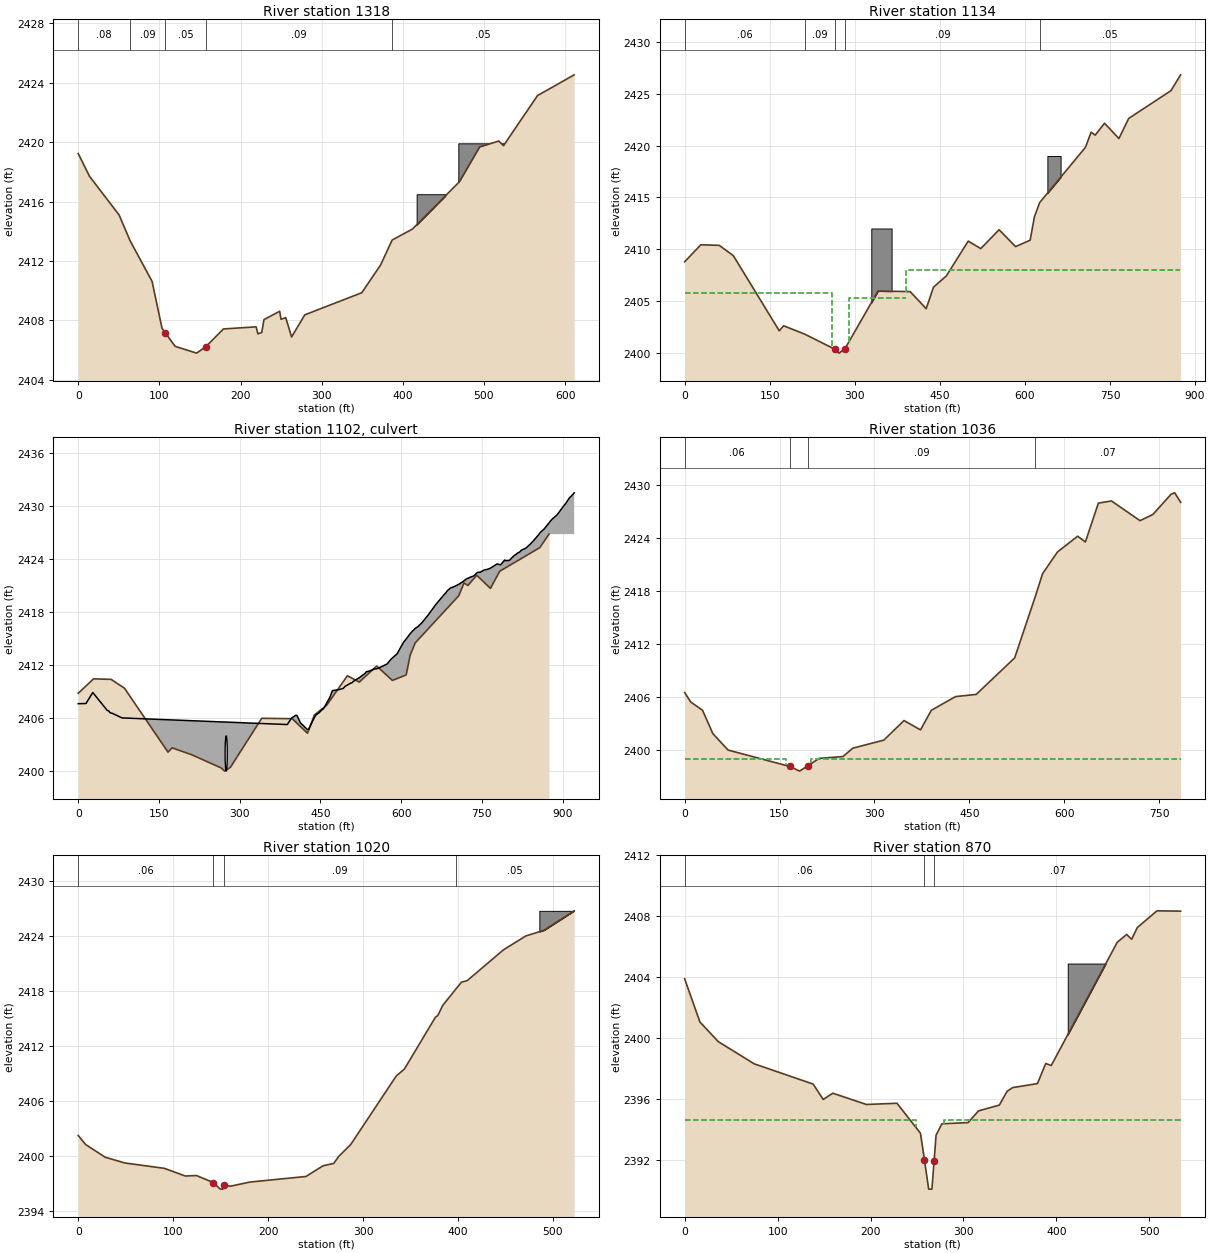
Type RM Length L Ch R = 1 ,1318    ,223.6,183.78,89.76
XS GIS Cut Line= 3
 1013867.3386425  699415.3386324 1013768.4219758  699238.7136323
 1013359.8073922  699245.7761323
#Sta/Elev= 30
       0 2419.24   13.98  2417.7   50.38  2415.1   64.04 2413.35      91 2410.63
  103.25 2407.47  107.31 2407.16  119.36 2406.25   145.9 2405.79  157.18 2406.22
  178.97 2407.42  219.28 2407.56  221.41 2407.09  226.17 2407.18   228.9 2408.05
  248.25 2408.61  249.91 2408.07  255.72 2408.18  262.93 2406.88  279.22 2408.37
  349.46 2409.86  372.71 2411.74  386.84 2413.41  411.88 2414.15  469.95 2417.35
  494.75 2419.68  518.16 2420.08  524.13 2419.77  565.92 2423.14  611.11 2424.54
#Mann= 5 ,-1 , 0
       0     .08       0   64.04     .09       0  107.31     .05       0
  157.18     .09       0  386.84     .05       0
#XS Ineff= 2 , 0
       0                  248.25       0 2408.61
Permanent Ineff=
       F       F
#Block Obstruct= 2 ,-1
     417  452.452416.496  468.99  525.232419.892
Bank Sta=107.31,157.18
Exp/Cntr=0.5,0.3

Type RM Length L Ch R = 1 ,1134    ,83.28,98.3,101.35
XS GIS Cut Line= 4
 1014204.9948926  699213.4636323 1013817.4532258  699200.2657156
 1013771.8594758  699194.2657156 1013332.7240589   699232.661549
#Sta/Elev= 30
       0 2408.79   28.56 2410.43   61.07 2410.37   85.91 2409.37  166.82 2402.12
  174.43 2402.61  211.47 2401.81  265.55 2400.33  272.21 2399.97  282.83 2400.41
  340.95 2405.96  397.57 2405.91  425.93 2404.26  438.71 2406.33  461.41 2407.42
  500.06 2410.78  522.18 2410.06  554.42 2411.88  583.56 2410.25  609.25 2410.87
   616.7 2413.12  626.01  2414.5  706.71 2419.83  716.76 2421.29  723.97 2421.01
  740.35 2422.16  765.78 2420.68  782.99 2422.62   857.5  2425.3  874.56 2426.83
#Mann= 5 ,-1 , 0
       0     .06       0  211.47     .09       0  265.55     .05       0
  282.83     .09       0  626.01     .05       0
#XS Ineff= 3 ,-1
       0   259.9  2405.8   289.9  389.48  2405.3  390.95  872.89    2408
Permanent Ineff=
       F       F       F
#Block Obstruct= 2 ,-1
  329.09  364.87    2412  639.61  662.89    2419
Bank Sta=265.55,282.83
Exp/Cntr=0.5,0.3

Type RM Length L Ch R = 2 ,1102    ,,,
BEGIN DESCRIPTION:
Sixth Street
END DESCRIPTION:
Bridge Culvert--1,0,-1,-1, 0
Deck Dist Width WeirC Skew NumUp NumDn MinLoCord MaxHiCord MaxSubmerge Is_Ogee
40,21,3,0, 131, 131, , , 0.95, 0, 0.5,0.5,,
       0   12.37   13.72   14.03   14.34   14.75   27.03   54.13   56.33    59.4
   63.38   81.34  388.37  396.05  404.08  406.43  412.78   425.7  427.96  439.24
  441.46  448.18  451.93  455.81  466.03  466.75  471.92  472.19  473.03  486.75
  492.39  495.79  506.39  509.27  510.16  516.83  520.76  532.46  535.33  538.92
  547.86  549.66  554.15  561.42  561.52  561.63  562.93  573.86  580.25  580.41
  580.92  592.26  596.41  604.09     609  612.21  615.67  620.57  624.73  625.93
  630.97     632  637.81  639.26  640.36  650.06  660.92  662.94  679.35  682.76
   684.5  688.44  691.95  693.74  699.07  709.54  709.89  710.44  712.45  721.29
  726.39  728.79  734.51  737.04  740.33  742.41  746.86  747.95  753.42  756.28
  758.65  764.89  771.37  777.02  777.46  777.74  778.33   784.7  789.72  792.34
  793.48  800.72  807.34  809.65  812.43  816.91  819.45  823.48  829.59  831.91
  839.93  842.63  845.25  848.26  855.46   857.3  865.09  866.04  867.19  878.26
     881  885.71  889.29   897.7  901.69  904.39  907.52  912.54  915.23  920.03
  921.27
 2407.61 2407.62 2407.63 2407.64 2407.64 2407.66 2408.88 2406.83 2406.82 2406.58
 2406.52    2406 2405.25 2405.97  2406.3 2406.28 2405.45 2404.68  2404.7 2406.11
 2406.32 2406.63 2406.88 2407.06 2408.18 2408.23 2409.07 2409.09  2409.1 2409.24
 2409.35 2409.58 2409.95    2410  2410.1 2410.37  2410.5 2411.03 2411.24 2411.27
 2411.48 2411.55 2411.56 2411.74 2411.74 2411.74 2411.79 2412.12  2412.6 2412.61
 2412.65 2413.26 2413.71 2414.55 2414.93 2415.18 2415.47 2415.82 2416.06 2416.15
 2416.34  2416.4 2416.75 2416.84 2416.93 2417.67 2418.57 2418.76 2419.95 2420.16
 2420.34 2420.57 2420.74 2420.77  2420.9 2421.23 2421.27  2421.3 2421.35 2421.76
 2421.89 2421.97 2422.08 2422.22 2422.43  2422.5 2422.51 2422.56 2422.74 2422.81
 2422.81 2422.95 2423.19 2423.42 2423.44 2423.44 2423.45 2423.35 2423.71  2423.9
 2423.82 2423.85 2424.25 2424.39  2424.5 2424.72 2424.77 2425.02 2425.18 2425.26
 2425.71 2425.88 2426.05 2426.27 2426.77 2426.95  2427.4 2427.45 2427.54 2428.39
 2428.56 2428.81    2429 2429.69 2430.01 2430.21 2430.48 2430.95  2431.1 2431.41
 2431.51
                                                                                
                                                                                
                                                                                
                                                                                
                                                                                
                                                                                
                                                                                
                                                                                
                                                                                
                                                                                
                                                                                
                                                                                
                                                                                
        
       0   12.37   13.72   14.03   14.34   14.75   27.03   54.13   56.33    59.4
   63.38   81.34  388.37  396.05  404.08  406.43  412.78   425.7  427.96  439.24
  441.46  448.18  451.93  455.81  466.03  466.75  471.92  472.19  473.03  486.75
  492.39  495.79  506.39  509.27  510.16  516.83  520.76  532.46  535.33  538.92
  547.86  549.66  554.15  561.42  561.52  561.63  562.93  573.86  580.25  580.41
  580.92  592.26  596.41  604.09     609  612.21  615.67  620.57  624.73  625.93
  630.97     632  637.81  639.26  640.36  650.06  660.92  662.94  679.35  682.76
   684.5  688.44  691.95  693.74  699.07  709.54  709.89  710.44  712.45  721.29
  726.39  728.79  734.51  737.04  740.33  742.41  746.86  747.95  753.42  756.28
  758.65  764.89  771.37  777.02  777.46  777.74  778.33   784.7  789.72  792.34
  793.48  800.72  807.34  809.65  812.43  816.91  819.45  823.48  829.59  831.91
  839.93  842.63  845.25  848.26  855.46   857.3  865.09  866.04  867.19  878.26
     881  885.71  889.29   897.7  901.69  904.39  907.52  912.54  915.23  920.03
  921.27
 2407.61 2407.62 2407.63 2407.64 2407.64 2407.66 2408.88 2406.83 2406.82 2406.58
 2406.52    2406 2405.25 2405.97  2406.3 2406.28 2405.45 2404.68  2404.7 2406.11
 2406.32 2406.63 2406.88 2407.06 2408.18 2408.23 2409.07 2409.09  2409.1 2409.24
 2409.35 2409.58 2409.95    2410  2410.1 2410.37  2410.5 2411.03 2411.24 2411.27
 2411.48 2411.55 2411.56 2411.74 2411.74 2411.74 2411.79 2412.12  2412.6 2412.61
 2412.65 2413.26 2413.71 2414.55 2414.93 2415.18 2415.47 2415.82 2416.06 2416.15
 2416.34  2416.4 2416.75 2416.84 2416.93 2417.67 2418.57 2418.76 2419.95 2420.16
 2420.34 2420.57 2420.74 2420.77  2420.9 2421.23 2421.27  2421.3 2421.35 2421.76
 2421.89 2421.97 2422.08 2422.22 2422.43  2422.5 2422.51 2422.56 2422.74 2422.81
 2422.81 2422.95 2423.19 2423.42 2423.44 2423.44 2423.45 2423.35 2423.71  2423.9
 2423.82 2423.85 2424.25 2424.39  2424.5 2424.72 2424.77 2425.02 2425.18 2425.26
 2425.71 2425.88 2426.05 2426.27 2426.77 2426.95  2427.4 2427.45 2427.54 2428.39
 2428.56 2428.81    2429 2429.69 2430.01 2430.21 2430.48 2430.95  2431.1 2431.41
 2431.51
                                                                                
                                                                                
                                                                                
                                                                                
                                                                                
                                                                                
                                                                                
                                                                                
                                                                                
                                                                                
                                                                                
                                                                                
                                                                                
        
BR Coef=-1 , 0 , 0 ,, 0 ,,,0.8,-1,,0,
WSPro=,,,, 1 ,,,, 0 ,,,, 0 ,,,,-1 ,-1 ,-1 , 0 , 0 , 0 , 0 , 0
Culvert=1,4,,40,0.027,0.9,1,2,3,2399.97,274.9,2397.57,180.2,Culvert #1  , 0 ,30
Culvert Bottom n=0.027
BC Design=,, 0 ,, 0 ,,,,,,

Type RM Length L Ch R = 1 ,1036    ,5.93,15.83,69.64
XS GIS Cut Line= 4
 1014140.2032259  699187.0677989 1013978.7240592  699110.2032156
 1013761.0573924  699130.6823822 1013375.9219756  699164.2761323
#Sta/Elev= 30
       0 2406.49     9.5 2405.42   28.22 2404.48   44.51 2401.83   68.63 2399.96
  166.32  2398.1  181.72 2397.57  194.69 2398.18  212.74 2399.02  250.23 2399.22
  265.65 2400.17  314.84 2401.09  346.78 2403.31  372.87 2402.25  389.85 2404.47
  428.22 2406.03  460.95 2406.28  521.76 2410.43  554.41 2417.41  565.87 2419.99
  589.46 2422.45  621.28 2424.24  633.52 2423.58  654.05 2427.99  674.65 2428.24
  719.91    2426  740.13  2426.7  769.17 2429.01  774.81 2429.16  784.07 2428.09
#Mann= 4 ,-1 , 0
       0     .06       0  166.32     .05       0  194.69     .09       0
  554.41     .07       0
#XS Ineff= 2 , 0
       0   160.2    2399   200.2       0    2399
Permanent Ineff=
       F       F
Bank Sta=166.32,194.69
Exp/Cntr=0.5,0.3

Type RM Length L Ch R = 1 ,1020    ,25.16,149.78,240.24
XS GIS Cut Line= 4
 1014104.2136426  699167.8698823 1013957.8282258  699091.0782156
 1013913.4428092  699031.0886322 1013666.2761424  698894.3177988
#Sta/Elev= 30
       0 2402.25    7.72 2401.27   28.38 2399.88   49.06 2399.25   90.56 2398.67
  112.84 2397.83  124.62 2397.88   142.2 2397.12  149.75  2396.4  152.24  2396.4
  153.73 2396.82  160.48 2396.72  180.83 2397.17  239.93 2397.78  257.99 2398.95
  269.17  2399.2  274.46 2399.97   287.1 2401.27   335.1 2408.74  343.63 2409.49
   376.3 2415.14   378.8 2415.32   383.9 2416.41  397.98 2418.23  403.75 2418.95
  409.73 2419.12  447.96 2422.48  471.53 2423.99  490.59 2424.61  522.41 2426.73
#Mann= 4 ,-1 , 0
       0     .06       0   142.2     .05       0  153.73     .09       0
  397.98     .05       0
#Block Obstruct= 1 ,-1
  485.74  522.412426.729
Bank Sta=142.2,153.73
Exp/Cntr=0.5,0.3

Type RM Length L Ch R = 1 ,870     ,98.57,78.79,74.52
XS GIS Cut Line= 5
 1014121.0053093  699161.8698823 1013996.2240592  699080.2865489
 1014045.4219759  698935.1094655 1014058.6198926  698859.5157155
 1013984.2240592  698723.9427987
#Sta/Elev= 30
       0 2403.88    16.4 2401.05   36.14 2399.76   74.82  2398.3  138.28 2396.97
  149.08 2395.96  159.42 2396.37  195.65 2395.63   228.5 2395.71  253.77 2393.74
  258.05    2392   262.6 2390.07  266.08 2390.07  268.44 2391.93  270.56 2393.61
  276.79 2394.36  305.05 2394.44  316.21 2395.21  338.63 2395.59  347.05  2396.5
  353.07 2396.74  379.65    2397  388.57 2398.32  394.55 2398.19  465.49 2406.28
  475.65  2406.8  481.03 2406.48  487.09 2407.25   508.3 2408.35  533.75 2408.33
#Mann= 3 , 0 , 0
       0     .06       0  258.05     .05       0  268.44     .07       0
#XS Ineff= 2 , 0
       0   248.9  2394.6   278.9       0  2394.6
Permanent Ineff=
       F       F
#Block Obstruct= 1 ,-1
  412.26  454.122404.888
Bank Sta=258.05,268.44
Exp/Cntr=0.5,0.3

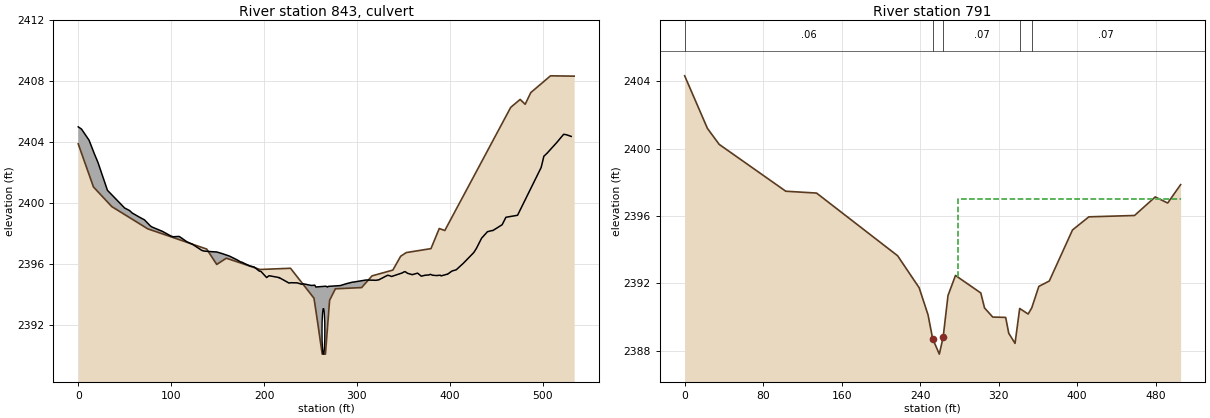
Type RM Length L Ch R = 2 ,843     ,,,
BEGIN DESCRIPTION:
Portman Villa Road
END DESCRIPTION:
Bridge Culvert--1,0,-1,-1, 0
Deck Dist Width WeirC Skew NumUp NumDn MinLoCord MaxHiCord MaxSubmerge Is_Ogee
18,16,3,0, 109, 109, , , 0.95, 0, 1,1,,
       0    3.57   11.69   17.62   20.26   21.32   31.47   49.29   49.67   50.21
   55.29   58.07   65.78   71.29   77.65   79.36   90.41  100.05  102.28  108.27
  108.91  110.85  116.93  122.77  122.85  130.13  132.86   135.3  143.52  149.06
  154.57  162.75  171.06   174.9  176.22   178.4  184.78   189.5  194.75  196.05
  196.87  202.74  205.46  215.27  215.92  216.22  225.33  226.64  228.76  235.65
  240.54  242.24  251.04  254.54  255.74  266.36  268.42  269.13  281.53  282.47
  288.85  295.33  295.98  307.91  309.81  320.56   323.5     333  335.19  337.27
  348.56  350.63  351.76  354.42  359.46  365.24  369.23   373.2  377.28  378.99
  381.66     386  388.43  389.74  390.57  394.82   396.9  397.31  402.05  402.93
  406.83  414.37  425.68  428.52  434.08   440.4  445.54  445.98  446.34  456.23
  460.34  472.83  498.24  501.17  504.64  514.91  522.43  525.41  530.57
    2405 2404.85 2404.12 2403.19 2402.81 2402.65 2400.83 2399.71 2399.68 2399.66
  2399.5 2399.34 2399.07 2398.89 2398.49 2398.42 2398.14 2397.82 2397.78  2397.8
 2397.79 2397.71 2397.45 2397.29 2397.29    2397 2396.89 2396.84  2396.8 2396.78
 2396.68 2396.51 2396.26 2396.12 2396.11 2396.04 2395.86 2395.79 2395.53 2395.51
 2395.49  2395.1 2395.22 2395.11 2395.08  2395.1 2394.79 2394.74 2394.76 2394.75
 2394.66 2394.69 2394.58  2394.6 2394.48 2394.53 2394.48 2394.52 2394.57 2394.58
  2394.7  2394.8  2394.8 2394.92 2394.94 2394.92 2394.95 2395.25 2395.22 2395.17
  2395.4 2395.47 2395.49 2395.38 2395.29 2395.39 2395.19 2395.25 2395.27 2395.31
 2395.25 2395.23 2395.25 2395.25 2395.21 2395.28 2395.32 2395.31 2395.52 2395.54
 2395.61 2396.03 2396.74 2397.01 2397.68 2398.11 2398.19 2398.18 2398.19 2398.57
 2399.06 2399.19 2402.33 2403.07 2403.27 2403.96 2404.51 2404.48 2404.37
                                                                                
                                                                                
                                                                                
                                                                                
                                                                                
                                                                                
                                                                                
                                                                                
                                                                                
                                                                                
                                                                        
       0    3.57   11.69   17.62   20.26   21.32   31.47   49.29   49.67   50.21
   55.29   58.07   65.78   71.29   77.65   79.36   90.41  100.05  102.28  108.27
  108.91  110.85  116.93  122.77  122.85  130.13  132.86   135.3  143.52  149.06
  154.57  162.75  171.06   174.9  176.22   178.4  184.78   189.5  194.75  196.05
  196.87  202.74  205.46  215.27  215.92  216.22  225.33  226.64  228.76  235.65
  240.54  242.24  251.04  254.54  255.74  266.36  268.42  269.13  281.53  282.47
  288.85  295.33  295.98  307.91  309.81  320.56   323.5     333  335.19  337.27
  348.56  350.63  351.76  354.42  359.46  365.24  369.23   373.2  377.28  378.99
  381.66     386  388.43  389.74  390.57  394.82   396.9  397.31  402.05  402.93
  406.83  414.37  425.68  428.52  434.08   440.4  445.54  445.98  446.34  456.23
  460.34  472.83  498.24  501.17  504.64  514.91  522.43  525.41  530.57
    2405 2404.85 2404.12 2403.19 2402.81 2402.65 2400.83 2399.71 2399.68 2399.66
  2399.5 2399.34 2399.07 2398.89 2398.49 2398.42 2398.14 2397.82 2397.78  2397.8
 2397.79 2397.71 2397.45 2397.29 2397.29    2397 2396.89 2396.84  2396.8 2396.78
 2396.68 2396.51 2396.26 2396.12 2396.11 2396.04 2395.86 2395.79 2395.53 2395.51
 2395.49  2395.1 2395.22 2395.11 2395.08  2395.1 2394.79 2394.74 2394.76 2394.75
 2394.66 2394.69 2394.58  2394.6 2394.48 2394.53 2394.48 2394.52 2394.57 2394.58
  2394.7  2394.8  2394.8 2394.92 2394.94 2394.92 2394.95 2395.25 2395.22 2395.17
  2395.4 2395.47 2395.49 2395.38 2395.29 2395.39 2395.19 2395.25 2395.27 2395.31
 2395.25 2395.23 2395.25 2395.25 2395.21 2395.28 2395.32 2395.31 2395.52 2395.54
 2395.61 2396.03 2396.74 2397.01 2397.68 2398.11 2398.19 2398.18 2398.19 2398.57
 2399.06 2399.19 2402.33 2403.07 2403.27 2403.96 2404.51 2404.48 2404.37
                                                                                
                                                                                
                                                                                
                                                                                
                                                                                
                                                                                
                                                                                
                                                                                
                                                                                
                                                                                
                                                                        
BR Coef=-1 , 0 , 0 ,, 0 ,,,0.8,-1,,0,
WSPro=,,,, 1 ,,,, 0 ,,,, 0 ,,,,-1 ,-1 ,-1 , 0 , 0 , 0 , 0 , 0
Culvert=1,3,,35,0.027,0.9,1,2,3,2390.07,263.9,2387.8,258.6,Culvert #1  , 0 ,10
Culvert Bottom n=0.027
BC Design=,, 0 ,, 0 ,,,,,,

Type RM Length L Ch R = 1 ,791     ,323.52,262.54,103.11
XS GIS Cut Line= 6
 1014136.6094759  699157.0782156 1014052.6198926  699071.8907156
 1014101.8073926  698965.0990488 1014095.8073926  698926.7032155
 1014123.4115593  698864.3177988 1014070.6198926  698711.9427987
#Sta/Elev= 30
       0 2404.32   23.18  2401.2   35.21 2400.25  103.06 2397.47  134.45 2397.36
  217.06 2393.64  239.02 2391.74  248.09 2390.13  252.77 2388.72  259.58  2387.8
  263.49 2388.81  268.43 2391.28  276.07 2392.47  301.87 2391.43  305.68 2390.54
  314.04    2390  327.21 2389.98  330.34 2389.04  336.77 2388.44   341.5 2390.51
  350.13 2390.18  353.83 2390.55     361 2391.82  371.68 2392.14  395.34 2395.17
  412.01 2395.95  458.59 2396.03  479.64 2397.13  492.38 2396.77  505.55 2397.86
#Mann= 5 ,-1 , 0
       0     .06       0  252.77     .05       0  263.49     .07       0
   341.5     .09       0  353.83     .07       0
#XS Ineff= 2 , 0
       0   238.6  2391.3   278.6       0    2397
Permanent Ineff=
       F       F
Bank Sta=252.77,263.49
Exp/Cntr=0.5,0.3