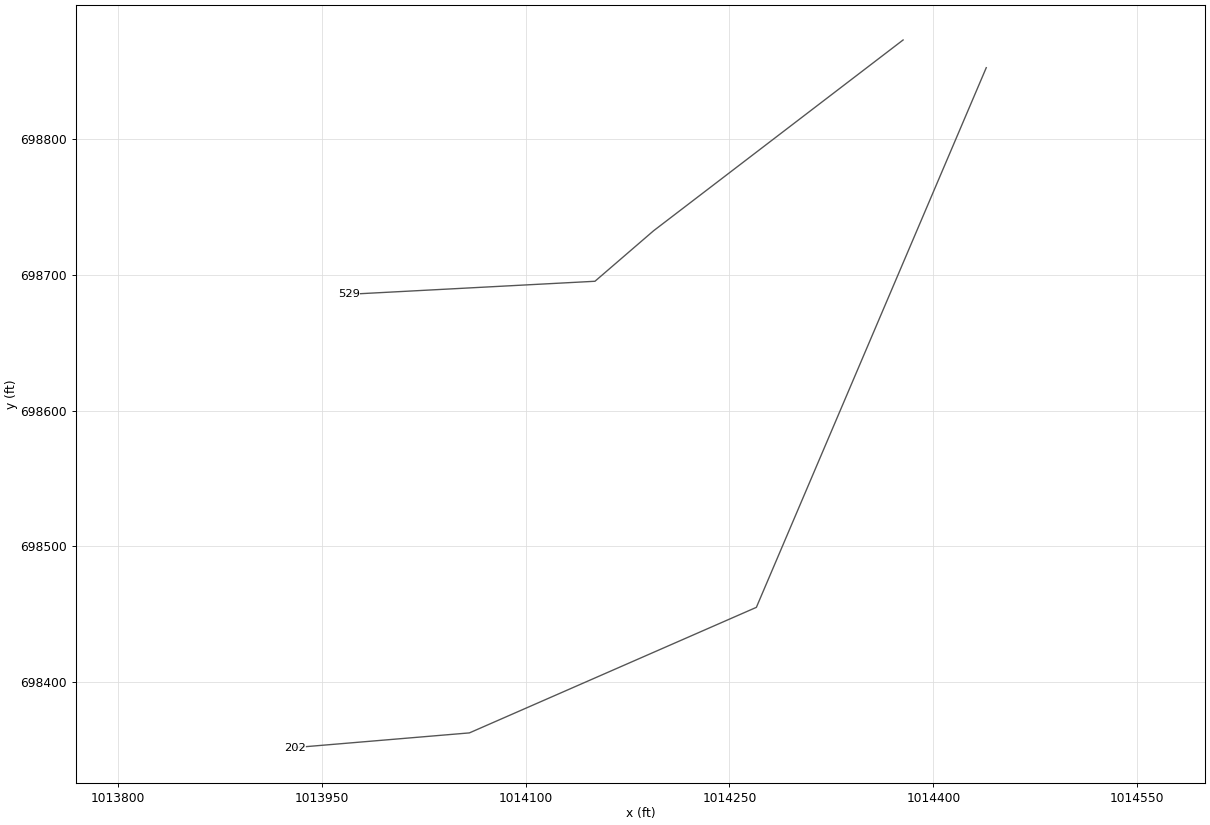
HEC-RAS study lds_flat_crk_trib1.prj: lds_flat_crk_trib1

--- lds_flat_crk_trib1.g01 (geometry) --- (continued)

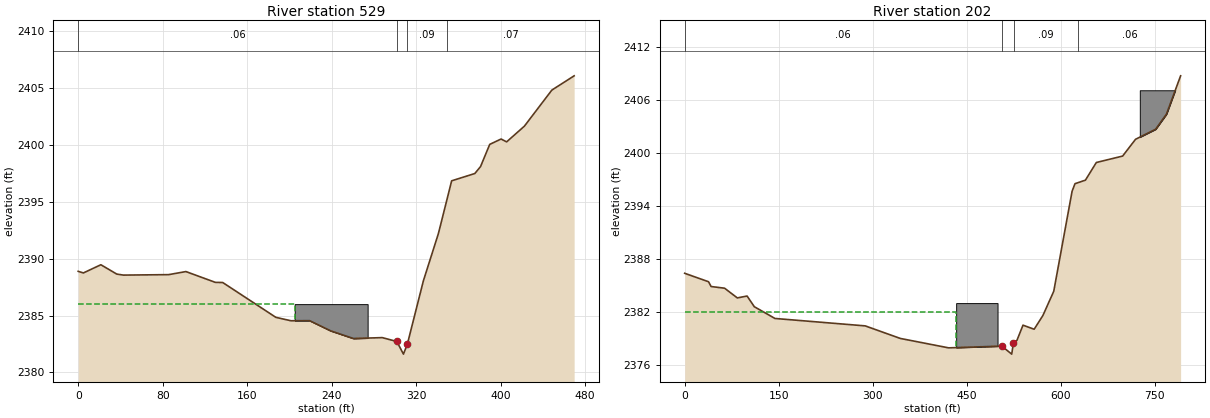
Type RM Length L Ch R = 1 ,529     ,299.87,327.1,308.31
XS GIS Cut Line= 4
  1014377.765726  698872.7136321 1014194.1928093  698732.3386321
 1014151.0053093  698695.1407154 1013969.8282259  698685.5469654
#Sta/Elev= 30
       0 2388.88     4.9 2388.74   21.45 2389.46   36.48 2388.64   42.74 2388.55
   85.58 2388.59  101.97 2388.86  129.88 2387.91  136.79  2387.9  187.12 2384.84
  201.44 2384.54  219.03 2384.55  239.09 2383.65  260.57 2382.98  287.82 2383.06
  301.67 2382.72   307.9 2381.61  311.62 2382.49  326.79 2388.05  341.01  2392.2
   348.9 2395.11  353.54 2396.83  375.48 2397.47  380.89 2398.08  389.61 2400.03
  400.33  2400.5   405.6 2400.25  422.41 2401.63  448.44  2404.8  469.52 2406.05
#Mann= 4 ,-1 , 0
       0     .06       0  301.67     .05       0  311.62     .09       0
   348.9     .07       0
#XS Ineff= 2 , 0
       0     205    2386               0
Permanent Ineff=
       F       F
#Block Obstruct= 1 ,-1
     205     274    2386
Bank Sta=301.67,311.62
Exp/Cntr=0.3,0.1

Type RM Length L Ch R = 1 ,202     ,155.93,201.65,218.35
XS GIS Cut Line= 4
 1014438.9636427  698852.3177988 1014269.7865593  698455.1823819
 1014058.6198926  698362.7969652 1013930.2344758  698351.9948819
#Sta/Elev= 30
       0 2386.38   38.08 2385.42   42.14 2384.88   63.63 2384.69   83.93 2383.59
   99.55  2383.8   111.1 2382.59  144.04 2381.26  287.98 2380.42   343.8    2379
  421.01 2377.93  505.81 2378.13  521.59 2377.22  524.27 2378.43  524.51 2378.44
  529.95 2378.78   539.6  2380.5  557.42 2380.04  571.37  2381.6  588.66 2384.34
  617.87 2395.66  622.54 2396.53  627.98 2396.66  639.17 2396.93  656.57 2398.93
  698.52 2399.66  719.12 2401.56  751.18  2402.7  768.42 2404.41     791 2408.75
#Mann= 4 ,-1 , 0
       0     .06       0  505.81     .05       0  524.51     .09       0
  627.98     .06       0
#XS Ineff= 2 , 0
       0     433    2382               0
Permanent Ineff=
       F       F
#Block Obstruct= 2 ,-1
  725.88  783.312407.114     433     499    2383
Bank Sta=505.81,524.27
Exp/Cntr=0.3,0.1

Chan Stop Cuts=-1
Use User Specified Reach Order=0
User Specified Reach Order=flat_crk_trib1  ,main