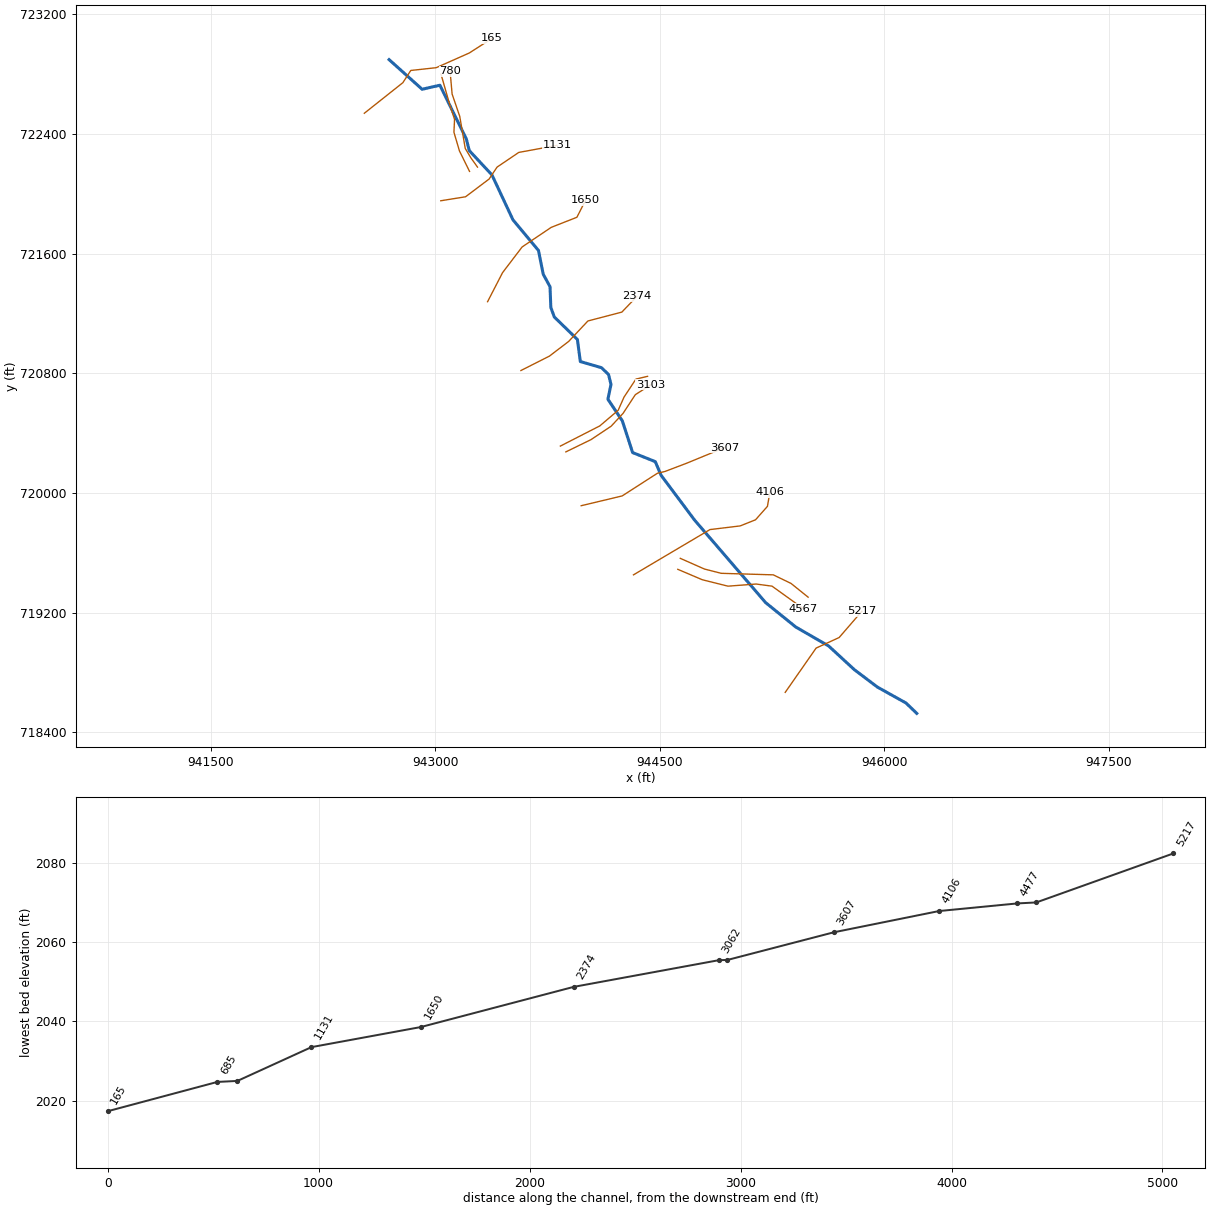
--- lds_herron_cove_bch.prj (project) ---

Proj Title=Herron Cove Branch Limited Detail Study
Current Plan=p02
Default Exp/Contr=0.3,0.1
English Units
Geom File=g01
Flow File=f02
Plan File=p02
Y Axis Title=Elevation
X Axis Title(PF)=Main Channel Distance
X Axis Title(XS)=Station
BEGIN DESCRIPTION:
Herron Cove Branch
END DESCRIPTION:
DSS Export Rating Curves= 0
DSS Export Rating Curve Sorted= 0
DSS Export Volume Flow Curves= 0
DXF OffsetX= 0
DXF OffsetY= 0
DXF ScaleX= 1
DXF ScaleY= 10

--- lds_herron_cove_bch.p02 (plan) ---

Plan Title=Floodway Run
Program Version=3.13
Short Identifier=Floodway
Geom File=g01
Flow File=f02
Subcritical Flow
K Sum by GR= 0
Std Step Tol= 0.01
Critical Tol= 0.01
Num of Std Step Trials= 20
Max Error Tol= 0.3
Flow Tol Ratio= 0.001
Split Flow NTrial= 30
Split Flow Tol= 0.02
Split Flow Ratio= 0.02
Log Output Level= 0
Friction Slope Method= 1
Unsteady Friction Slope Method= 2
Unsteady Bridges Friction Slope Method= 1
Parabolic Critical Depth
Global Vel Dist= 0 , 0 , 0
Global Log Level= 0
CheckData=True
Encroach Param=-1 ,5,5, 2
Encroach River=Herron Cove Bran
Encroach Reach=Reach-1
Encroach Node=5217
       4      .7
Encroach Node=4567
       1 3504.77 3566.29
Encroach Node=4477
       1 3494.95 3573.58
Encroach Node=4106
       4      .7
Encroach Node=3607
       4      .7
Encroach Node=3103
       1  4959.4  5088.8
Encroach Node=3062
       1  4955.9  5096.9
Encroach Node=2374
       1 4975.66 5021.88
Encroach Node=1650
       4      .7
Encroach Node=1131
       4      .7
Encroach Node=780
       1 3500.89 3608.01
Encroach Node=685
       1 3520.69 3605.54
Encroach Node=165
       4      .7
BEGIN DESCRIPTION:
Floodway Run
END DESCRIPTION:
Computation Interval=1HOUR
Output Interval=1HOUR
Run HTab= 0
Run UNet= 0
Run PostProcess= 0
UNET Theta= 1
UNET Theta Warmup= 1
UNET ZTol= 0.02
UNET ZSATol= 0.05
UNET MxIter= 20
UNET MaxInSteps= 0
UNET DtIC= 0
UNET DtMin= 0
UNET MaxCRTS= 20
UNET WFStab= 2
UNET SFStab= 1
UNET WFX= 1
UNET SFX= 1
UNET DSS MLevel= 4
UNET DZMax Abort= 100
UNET Convert EG Bridges=-1
UNET Use Existing IB Tables=-1
UNET Froude Reduction=False
UNET Froude Limit= 1
UNET Froude Power= 10
Instantaneous Interval=1HOUR
Write IC File= 0
Echo Input=False
Echo Output=False
Write Detailed= 0
Detailed Automatic Start=False, 10

--- lds_herron_cove_bch.f02 (steady flow) ---

Flow Title=Floodway
Program Version=3.13
Number of Profiles= 2
Profile Names=100-year,100-FW
River Rch & RM=Herron Cove Bran,Reach-1         ,5217
    1190    1190
River Rch & RM=Herron Cove Bran,Reach-1         ,4106
    1330    1330
River Rch & RM=Herron Cove Bran,Reach-1         ,780
    1440    1440
Boundary for River Rch & Prof#=Herron Cove Bran,Reach-1         , 1
Up Type= 0
Dn Type= 3
Dn Slope=0.01
Boundary for River Rch & Prof#=Herron Cove Bran,Reach-1         , 2
Up Type= 0
Dn Type= 3
Dn Slope=0.01
DSS Import GetInterval= 0
DSS Import GetPeak= 0
DSS Import FillOption= 0

--- lds_herron_cove_bch.g01 (geometry) ---

Geom Title=Existing Conditions
Program Version=3.13

River Reach=Herron Cove Bran,Reach-1
Reach XY= 30
       946217.03       718527.63       946145.06       718596.86
       945953.75       718703.45       945800.44       718819.22
       945628.36       718977.72       945408.74       719104.51
       945207.23       719267.53       944731.75       719819.98
       944508.55       720118.59       944470.01       720209.44
       944318.59         720270.       944249.77       720481.98
       944153.42       720626.51       944174.06       720725.62
       944157.54       720791.69       944110.75       720837.11
       943968.97       720878.41        943949.7       721025.69
       943795.53       721175.73       943772.13       721239.04
       943766.63       721378.07        943721.2       721462.04
       943689.54       721620.33       943518.86       721825.43
       943378.46        722125.5       943227.04       722287.93
       943207.78       722365.01         943031.       722724.43
       942912.15       722697.46       942691.47        722895.5

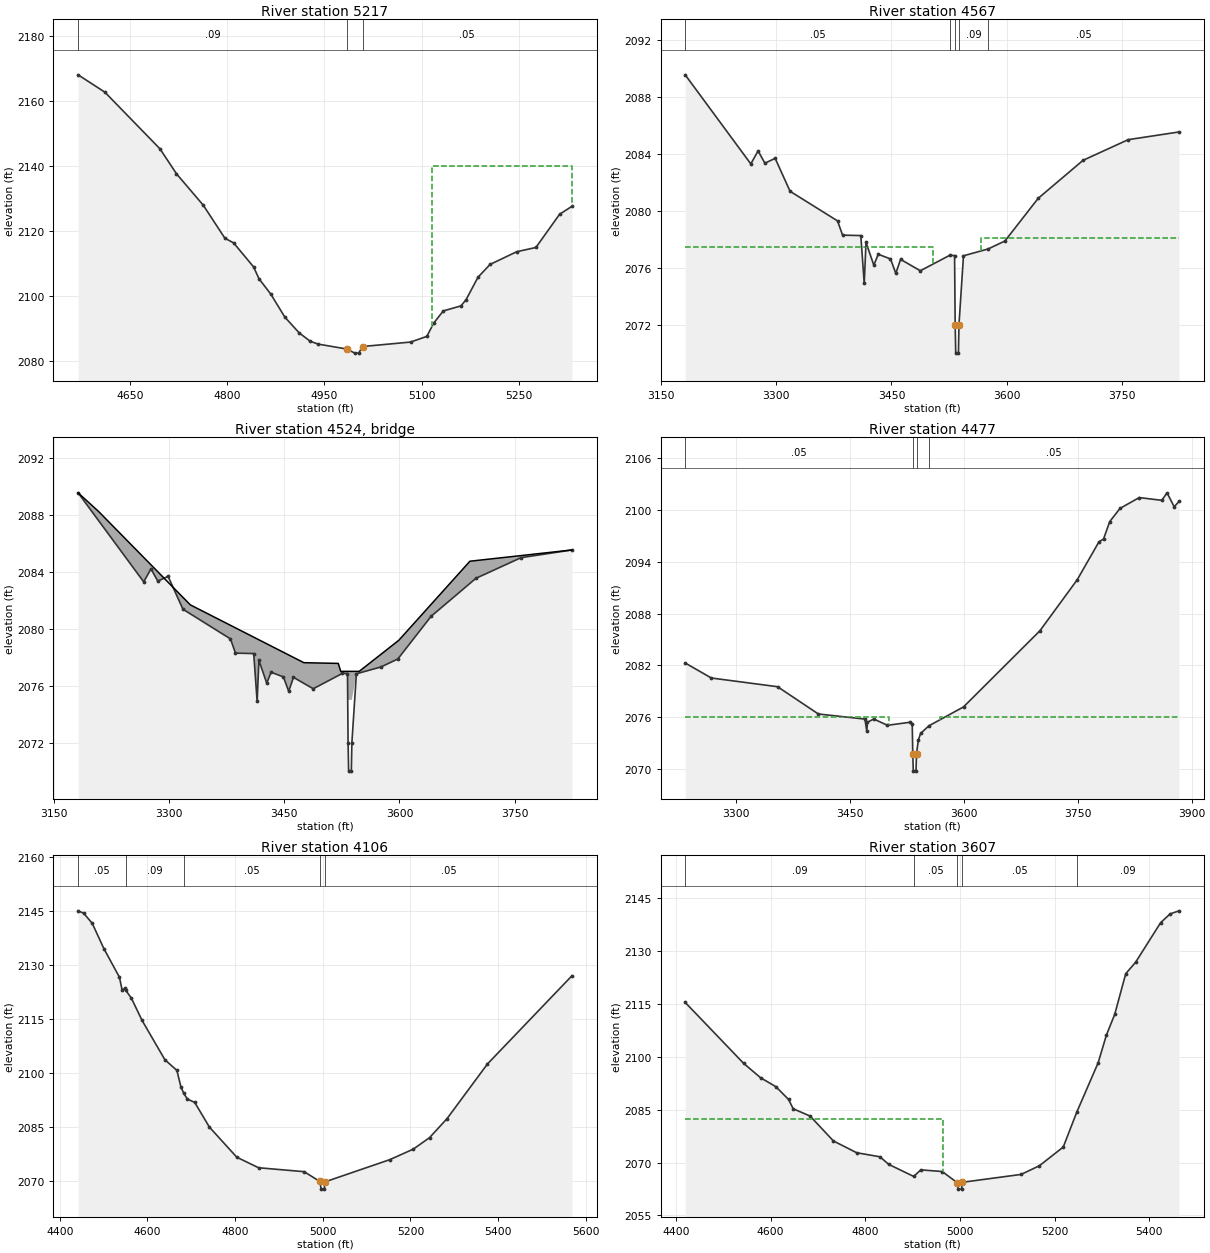
Type RM Length L Ch R = 1 ,5217    ,650,650,650
BEGIN DESCRIPTION:
xs 1
END DESCRIPTION:
XS GIS Cut Line= 4
       945338.23       718668.19       945544.38       718963.74
       945698.31       719034.42       945850.16       719209.88
#Sta/Elev= 30
  4570.2 2168.18  4611.5 2162.83  4696.6 2145.34    4722 2137.66  4763.4 2127.95
  4796.6 2117.81  4810.2 2116.34  4840.8 2108.98  4849.4 2105.27  4867.4 2100.58
  4889.1 2093.48  4911.1 2088.64  4928.3 2086.01  4940.7 2085.14  4984.9 2083.62
  4997.1 2082.36    5003 2082.36  5009.1  2084.4  5083.1 2085.77  5108.2 2087.52
  5118.8 2091.61  5133.6 2095.37  5160.9 2096.93  5168.9 2098.89  5187.1 2105.75
  5205.8 2109.71  5246.9 2113.63  5276.5 2114.94  5313.1  2125.2    5332 2127.61
#Mann= 3 ,-1 , 0
  4570.2     .09       0  4984.9     .05       0  5009.1     .05       0
#XS Ineff= 2 , 0
       0                  5115.5       0    2140
Permanent Ineff=
       F       F
Bank Sta=4984.9,5009.1
Exp/Cntr=0.5,0.3

Type RM Length L Ch R = 1 ,4567    ,90,90,90
BEGIN DESCRIPTION:
Herron_Cove_Bch_XS15
END DESCRIPTION:
XS GIS Cut Line= 6
       944620.62       719489.94       944784.11       719420.45
       944955.78       719377.54        945143.8       719391.84
       945250.07       719377.54       945460.57        719226.3
#Sta/Elev= 30
3181.273 2089.533266.762 2083.283276.238 2084.193285.147 2083.333298.511 2083.67
3317.886 2081.363379.758 2079.283386.334 2078.283410.093 2078.253414.548 2074.89
3416.881 2077.773427.064 2076.173432.791 2076.943448.772 2076.613455.702  2075.6
3461.924 2076.583487.663 2075.783525.776 2076.863532.281 2076.853533.059    2072
3533.766    20703537.302    20703538.009    20723543.878 2076.83 3575.98 2077.31
3597.901 2077.873641.176 2080.863699.653 2083.533758.484 2084.98 3824.67 2085.52
#Mann= 5 ,-1 , 0
3181.273     .05       03525.776     .09       03533.059     .05       0
3538.009     .09       0 3575.98     .05       0
#XS Ineff= 2 , 0
       03504.775 2077.473566.293       0 2078.11
Permanent Ineff=
       F       F
Bank Sta=3533.059,3538.009
Skew Angle= 45
Exp/Cntr=0.5,0.3

Type RM Length L Ch R = 3 ,4524    ,,,
BEGIN DESCRIPTION:
Herron_Cove_Bch_XS14
Structure ID: Herron Cove Rd SR 2098 - 2
Approximate Survey Structure
END DESCRIPTION:
Bridge Culvert--1,0,-1,-1, 0
Deck Dist Width WeirC Skew NumUp NumDn MinLoCord MaxHiCord MaxSubmerge Is_Ogee
34,18,3,45, 12, 9, , , , 0, 1,1,,
3181.2733208.0023327.432 3475.43 3520.263523.5133523.5133547.5553547.5553599.103
3691.804 3824.67
 2089.53 2088.22 2081.67 2077.61 2077.56    2077    2077    2077    2077 2079.18
 2084.73 2085.52
    2050    2050    2050    2050    2050       0    2075    2075       0    2050
    2050    2050
3208.002 3436.683523.5133523.5133547.5553547.5553555.7573653.1963883.289
 2088.22 2077.88    2077    2077    2077    2077 2077.76 2082.51    2101
    2050    2050       0    2075    2075       0    2050    2050    2050
BR Coef= 1 , 1 , 0 ,1.25, 0 ,,,0.8,0,2,0,
WSPro=,,,, 1 ,,,, 0 ,,,, 0 ,,,,-1 ,-1 ,-1 , 0 , 0 , 0 , 0 , 0
BC Design=,, 0 ,, 0 ,,,,,,
BC HTab HWMax=2089.53

Type RM Length L Ch R = 1 ,4477    ,371,371,371
BEGIN DESCRIPTION:
Herron_Cove_Bch_XS13
END DESCRIPTION:
XS GIS Cut Line= 6
       944636.97       719563.51       944798.42       719491.98
       944910.82       719463.37       945258.24       719453.15
       945376.78       719395.93       945491.22       719303.96
#Sta/Elev= 30
 3233.67 2082.283268.106 2080.543355.222 2079.533408.891 2076.373470.126 2075.78
3472.601 2074.35 3473.45 2075.423481.794 2075.793499.754 2075.063529.948 2075.42
3532.352 2075.263533.059 2071.753533.766 2069.753537.302 2069.753538.009 2071.75
3540.342 2073.333543.383 2074.123554.272    2075 3599.81 2077.19 3700.29 2086.01
3749.363 2091.923778.072 2096.333784.011 2096.643792.214 2098.67 3805.79  2100.2
3831.034 2101.453860.661 2101.133867.591    21023876.996 2100.383883.289    2101
#Mann= 4 ,-1 , 0
 3233.67     .05       03533.059     .05       03538.009     .09       0
3554.272     .05       0
#XS Ineff= 2 , 0
       03501.946    20763569.121       0    2076
Permanent Ineff=
       F       F
Bank Sta=3533.059,3538.009
Skew Angle= 45
Exp/Cntr=0.5,0.3

Type RM Length L Ch R = 1 ,4106    ,499,499,499
BEGIN DESCRIPTION:
Herron_Cove_Bch_XS12
END DESCRIPTION:
XS GIS Cut Line= 6
       944324.29       719453.15        944835.2       719755.61
       945037.53       719780.14       945139.71       719821.01
       945219.41       719910.93       945235.76       720006.98
#Sta/Elev= 30
  4441.9 2145.03  4454.5 2144.37  4474.1 2141.57  4500.7 2134.54  4536.2 2126.62
  4542.5 2122.94    4548 2123.52  4550.5 2122.98  4563.3 2120.83  4587.8 2114.63
  4639.9 2103.72  4667.2 2100.77  4676.4 2096.22  4682.9  2094.4  4691.1 2092.83
    4708 2091.87  4741.3 2085.06  4803.8 2076.69  4853.6 2073.76  4957.6 2072.67
  4993.2 2069.96  4996.5 2067.83  5003.5 2067.83    5005 2069.84  5153.2 2076.02
  5206.7 2078.94  5243.5  2082.1  5283.6  2087.4  5375.7 2102.55  5568.3    2127
#Mann= 5 ,-1 , 0
  4441.9     .05       0  4550.5     .09       0  4682.9     .05       0
  4993.2     .05       0    5005     .05       0
Bank Sta=4993.2,5005
Exp/Cntr=0.3,0.1

Type RM Length L Ch R = 1 ,3607    ,504,504,504
BEGIN DESCRIPTION:
Herron_Cove_Bch_XS11
END DESCRIPTION:
XS GIS Cut Line= 6
       943974.82       719915.02       944248.67       719980.42
       944483.69       720131.65       944534.79       720143.91
       944679.89       720199.09        944933.3       720303.32
#Sta/Elev= 30
  4419.5 2115.39  4542.7 2098.15  4578.6 2094.05  4611.1  2091.5  4637.8 2087.89
  4647.6 2085.25  4683.4 2083.17  4732.6 2076.12  4781.6 2072.79  4830.9 2071.63
  4849.3 2069.49  4902.1 2066.07  4917.1 2067.93  4962.4 2067.46  4993.6 2064.34
  4996.5 2062.47  5003.5 2062.47  5003.9 2064.39    5129 2066.64  5167.6  2069.1
    5218  2074.4  5246.7 2084.34  5291.7 2098.28  5309.1 2106.12  5326.7 2112.01
    5350 2123.55  5370.7 2126.75  5423.7    2138  5443.6 2140.47  5462.4 2141.35
#Mann= 5 ,-1 , 0
  4419.5     .09       0  4902.1     .05       0  4993.6     .05       0
  5003.9     .05       0  5246.7     .09       0
#XS Ineff= 2 , 0
         4964.71 2082.26
Permanent Ineff=
       F       F
Bank Sta=4993.6,5003.9
Exp/Cntr=0.5,0.3

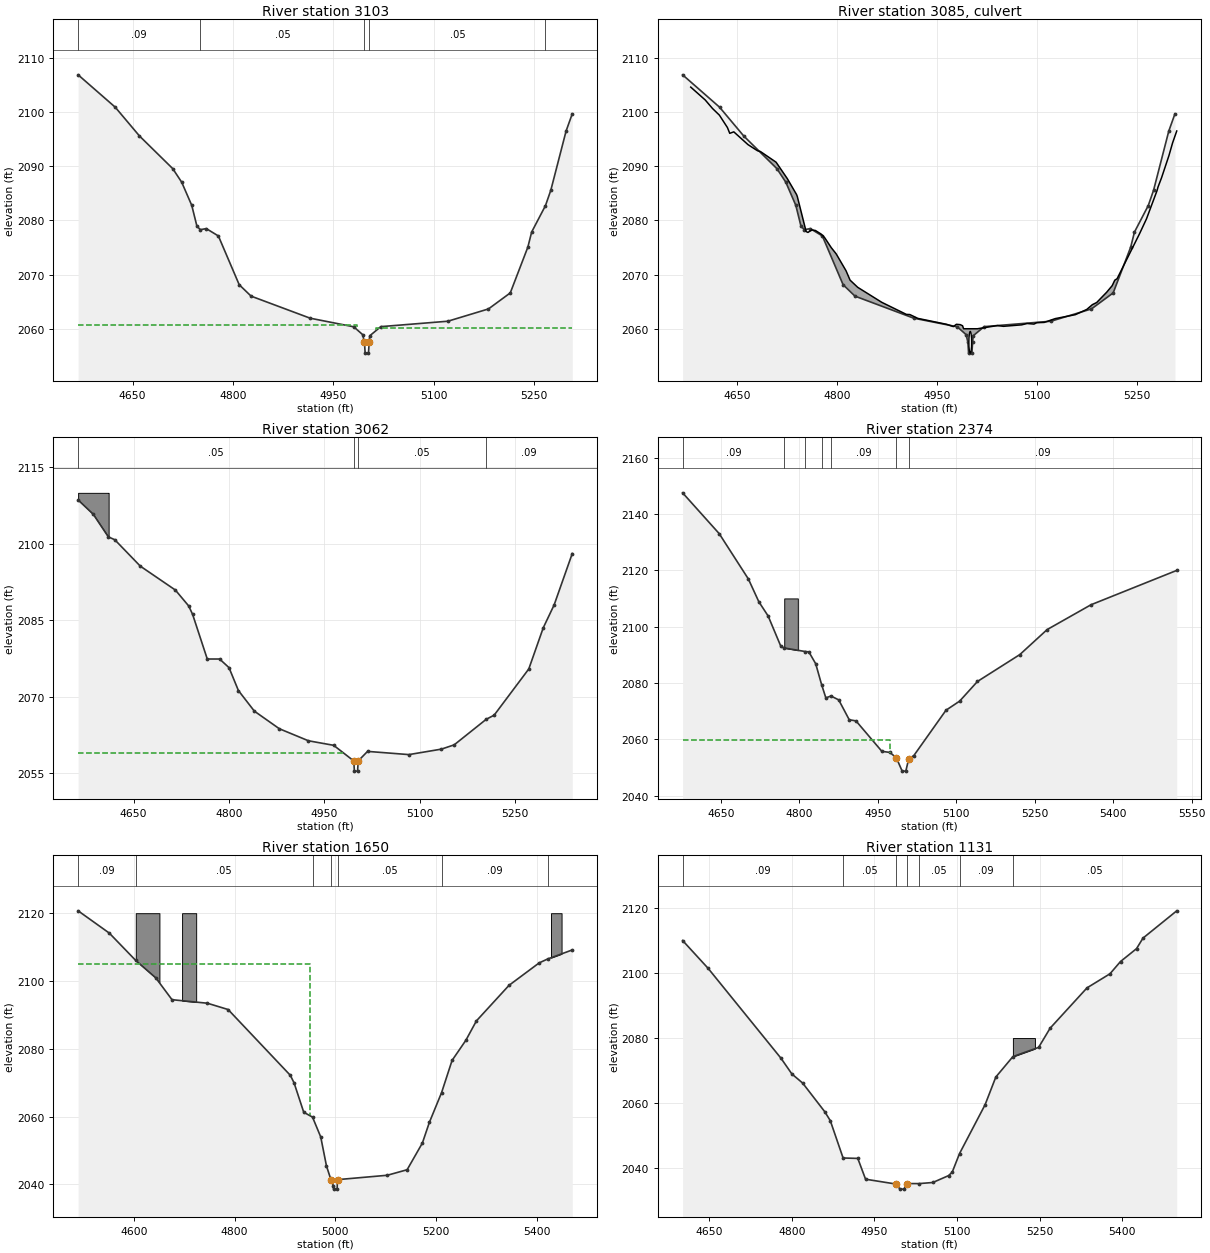
Type RM Length L Ch R = 1 ,3103    ,41,41,41
BEGIN DESCRIPTION:
Herron_Cove_Bch_XS10
END DESCRIPTION:
XS GIS Cut Line= 6
       943872.64        720274.7       944040.22       720356.45
        944175.1       720446.37        944254.8       720532.21
       944336.55       720656.87       944438.73       720722.27
#Sta/Elev= 30
  4568.6 2106.88    4624 2100.91  4660.2  2095.6    4710 2089.56  4723.4 2087.05
  4738.4 2082.78  4746.1 2078.95  4751.2 2078.29  4760.1 2078.49  4778.2 2077.13
  4809.3 2068.13  4827.1 2066.02  4915.3 2061.95  4980.5 2060.36  4993.8 2058.91
  4996.5  2057.5  4997.5  2055.5  5002.5  2055.5  5003.5  2057.5  5004.4  2058.7
  5020.9 2060.39  5121.1 2061.39  5181.8 2063.66  5214.4 2066.62  5240.7 2075.09
  5246.3 2077.85    5267 2082.74    5275 2085.59  5297.8 2096.51    5307 2099.68
#Mann= 5 ,-1 , 0
  4568.6     .09       0  4751.2     .05       0  4996.5     .05       0
  5003.5     .05       0    5267     .09       0
#XS Ineff= 2 , 0
       0    4986 2060.71    5014       0 2060.06
Permanent Ineff=
       F       F
Bank Sta=4996.5,5003.5
Exp/Cntr=0.5,0.3

Type RM Length L Ch R = 2 ,3085    ,,,
BEGIN DESCRIPTION:
Herron_Cove_Bch_XS9
Structure ID: Driveway
Approximate Survey Structure
END DESCRIPTION:
Bridge Culvert--1,0,-1,-1, 0
Deck Dist Width WeirC Skew NumUp NumDn MinLoCord MaxHiCord MaxSubmerge Is_Ogee
12,12,3,0, 60, 60, , , , 0, 1,1,,
  4580.8  4602.5  4613.4  4623.8  4635.8  4639.3  4645.4  4666.7    4681  4685.3
  4708.8  4725.6  4739.5  4740.6  4753.8  4756.5  4762.3  4767.8  4776.7  4781.8
  4791.5  4798.9  4813.7  4819.8  4831.2  4867.3  4904.2  4909.4  4921.5  4964.6
  4974.7  4979.2    4985  4988.5    4990  5010.8  5040.8  5049.8  5077.1  5085.2
  5095.6  5099.7  5110.9  5127.4  5157.6  5174.7  5183.2  5189.6  5204.6  5212.9
  5216.8  5220.2  5253.9  5264.4  5280.2  5281.6  5286.9    5298  5303.5  5309.7
 2104.61 2102.24 2100.67 2099.43 2097.15 2096.08 2096.35 2093.99 2092.86 2092.72
 2090.75 2087.72 2084.78 2084.43 2077.96 2077.78 2078.24 2078.14 2077.45 2076.79
 2074.98 2073.83 2070.71 2068.97 2067.65 2064.88 2062.65 2062.62 2061.91 2060.82
  2060.4 2060.82 2060.76 2060.55    2060    2060 2060.59 2060.45 2060.72 2060.97
 2060.86 2061.12 2061.17 2061.87  2062.6 2063.56 2064.45 2064.84 2066.74 2067.96
 2068.97 2069.23 2077.54 2080.31 2085.52 2086.16 2087.87 2091.97 2094.33 2096.51
  2035.5  2035.5  2035.5  2035.5  2035.5  2035.5  2035.5  2035.5  2035.5  2035.5
  2035.5  2035.5  2035.5  2035.5  2035.5  2035.5  2035.5  2035.5  2035.5  2035.5
  2035.5  2035.5  2035.5  2035.5  2035.5  2035.5  2035.5  2035.5  2035.5  2035.5
  2035.5  2035.5  2035.5  2035.5  2035.5  2035.5  2035.5  2035.5  2035.5  2035.5
  2035.5  2035.5  2035.5  2035.5  2035.5  2035.5  2035.5  2035.5  2035.5  2035.5
  2035.5  2035.5  2035.5  2035.5  2035.5  2035.5  2035.5  2035.5  2035.5  2035.5
  4580.8  4602.5  4613.4  4623.8  4635.8  4639.3  4645.4  4666.7    4681  4685.3
  4708.8  4725.6  4739.5  4740.6  4753.8  4756.5  4762.3  4767.8  4776.7  4781.8
  4791.5  4798.9  4813.7  4819.8  4831.2  4867.3  4904.2  4909.4  4921.5  4964.6
  4974.7  4979.2    4985  4988.5    4990  5010.8  5040.8  5049.8  5077.1  5085.2
  5095.6  5099.7  5110.9  5127.4  5157.6  5174.7  5183.2  5189.6  5204.6  5212.9
  5216.8  5220.2  5253.9  5264.4  5280.2  5281.6  5286.9    5298  5304.5  5340.3
 2104.61 2102.24 2100.67 2099.43 2097.15 2096.08 2096.35 2093.99 2092.86 2092.72
 2090.75 2087.72 2084.78 2084.43 2077.96 2077.78 2078.24 2078.14 2077.45 2076.79
 2074.98 2073.83 2070.71 2068.97 2067.65 2064.88 2062.65 2062.62 2061.91 2060.82
  2060.4 2060.82 2060.76 2060.55    2060    2060 2060.59 2060.45 2060.72 2060.97
 2060.86 2061.12 2061.17 2061.87  2062.6 2063.56 2064.45 2064.84 2066.74 2067.96
 2068.97 2069.23 2077.54 2080.31 2085.52 2086.16 2087.87 2091.97 2094.64  2098.1
 2035.44 2035.44 2035.44 2035.44 2035.44 2035.44 2035.44 2035.44 2035.44 2035.44
 2035.44 2035.44 2035.44 2035.44 2035.44 2035.44 2035.44 2035.44 2035.44 2035.44
 2035.44 2035.44 2035.44 2035.44 2035.44 2035.44 2035.44 2035.44 2035.44 2035.44
 2035.44 2035.44 2035.44 2035.44 2035.44 2035.44 2035.44 2035.44 2035.44 2035.44
 2035.44 2035.44 2035.44 2035.44 2035.44 2035.44 2035.44 2035.44 2035.44 2035.44
 2035.44 2035.44 2035.44 2035.44 2035.44 2035.44 2035.44 2035.44 2035.44  2035.5
Culvert=1,4,,12,0.013,0.2,1,1,3,2055.5,5000,2055.44,5000,Culvert #1  , 0 ,12
Culvert Bottom n=0.013
BC Design=,, 0 ,, 0 ,,,,,,
BC HTab HWMax=2106.88

Type RM Length L Ch R = 1 ,3062    ,688,688,688
BEGIN DESCRIPTION:
Herron_Cove_Bch_XS8
END DESCRIPTION:
XS GIS Cut Line= 6
       943835.85       720313.53       944099.48       720448.42
        944222.1       720552.64       944260.93       720640.52
       944340.64        720761.1        944418.3       720779.49
#Sta/Elev= 30
  4562.8  2108.6  4586.6  2105.8  4610.3 2101.37  4620.5  2100.8  4660.6 2095.63
  4715.8 2090.94  4736.8 2087.82    4743 2086.15    4766 2077.42  4785.4 2077.42
  4800.2 2075.73    4815 2071.24  4840.1  2067.2  4879.4 2063.75  4925.2 2061.39
  4964.9  2060.5  4996.5 2057.44  4997.5 2055.44  5002.5 2055.44  5003.5 2057.44
  5018.2 2059.31  5083.2 2058.68  5134.3 2059.75  5154.5 2060.59  5204.9  2065.6
  5217.4 2066.41  5271.9 2075.47  5294.7 2083.55  5311.8 2088.03  5340.3  2098.1
#Mann= 4 ,-1 , 0
  4562.8     .05       0  4996.5     .05       0  5003.5     .05       0
  5204.9     .09       0
#XS Ineff= 2 , 0
       0    4981    2059    5019       0    2059
Permanent Ineff=
       F       F
#Block Obstruct= 1 ,-1
  4562.8  4610.8    2110
Bank Sta=4996.5,5003.5
Exp/Cntr=0.5,0.3

Type RM Length L Ch R = 1 ,2374    ,724,724,724
BEGIN DESCRIPTION:
Herron_Cove_Bch_XS7
END DESCRIPTION:
XS GIS Cut Line= 6
       943572.22       720818.32       943762.28       720914.37
       943891.03       721012.47       944019.78       721149.39
       944246.63       721208.66       944346.77       721312.89
#Sta/Elev= 30
  4576.7 2147.47  4646.7 2132.98  4702.4 2116.91  4722.5  2108.8  4740.2 2103.77
  4764.5 2093.02    4771 2092.41  4811.2 2091.15  4818.1 2091.03  4831.2 2086.81
  4842.5 2079.39  4850.6 2074.69  4860.3 2075.37  4875.2 2073.99  4895.3 2066.94
  4908.2 2066.54  4957.7 2055.73  4973.1 2055.35  4985.4 2053.43  4996.5 2048.71
  5003.5 2048.71    5009 2053.06  5018.9 2054.25  5080.3 2070.32  5106.4 2073.55
  5140.5 2080.53  5221.5 2090.07  5273.7 2098.94  5357.6 2107.75  5521.5 2119.94
#Mann= 7 ,-1 , 0
  4576.7     .09       0    4771     .05       0  4811.2     .09       0
  4842.5     .05       0  4860.3     .09       0  4985.4     .05       0
    5009     .09       0
#XS Ineff= 2 , 0
       0  4973.6 2059.71               0
Permanent Ineff=
       F       F
#Block Obstruct= 1 ,-1
    4771    4797    2110
Bank Sta=4985.4,5009
Exp/Cntr=0.3,0.1

Type RM Length L Ch R = 1 ,1650    ,519,519,519
BEGIN DESCRIPTION:
Herron_Cove_Bch_XS6
END DESCRIPTION:
XS GIS Cut Line= 6
       943349.46       721278.14        943449.6       721472.29
       943580.39       721643.96       943774.54       721774.76
       943946.21        721842.2       944003.43        721954.6
#Sta/Elev= 30
  4489.1  2120.7  4551.1 2114.12  4603.6 2106.05  4643.4 2100.91  4675.6 2094.48
  4745.9 2093.44    4787 2091.58  4910.6 2072.17  4918.1 2069.92  4937.2 2061.28
  4954.7 2059.83    4971 2053.98  4982.4 2045.43  4991.5 2041.26  4996.1 2039.57
  4996.5 2038.59  5003.5 2038.59  5004.4 2041.39  5103.2 2042.68  5142.6 2044.31
  5172.9 2052.19  5186.8 2058.29  5211.1 2067.09  5231.9 2076.57  5259.2 2082.49
  5280.2 2088.22    5345 2098.72  5404.9 2105.34  5421.7 2106.49  5470.6 2109.16
#Mann= 7 ,-1 , 0
  4489.1     .09       0  4603.6     .05       0  4954.7     .09       0
  4991.5     .05       0  5004.4     .05       0  5211.1     .09       0
  5421.7     .05       0
#XS Ineff= 2 , 0
       0 4948.73    2105               0
Permanent Ineff=
       F       F
#Block Obstruct= 3 ,-1
  4603.6  4650.6    2120  4695.6  4723.6    2120 5428.37 5449.37    2120
Bank Sta=4991.5,5004.4
Exp/Cntr=0.3,0.1

Type RM Length L Ch R = 1 ,1131    ,351,351,351
BEGIN DESCRIPTION:
Herron_Cove_Bch_XS5
END DESCRIPTION:
XS GIS Cut Line= 6
       943036.78       721952.55       943202.32       721979.12
       943359.68       722097.65       943412.81       722177.36
       943557.91       722275.45       943813.37       722322.46
#Sta/Elev= 30
  4601.7 2110.02  4647.9 2101.48  4780.2 2073.82  4800.1 2068.96  4819.7 2066.15
  4859.7 2057.36  4869.8 2054.61  4893.1  2043.1  4919.8 2042.97  4933.9 2036.57
  4988.9 2035.09  4996.5 2033.52  5003.5 2033.52  5009.4 2035.23  5030.9 2035.22
    5056 2035.56  5084.5 2037.67  5091.2 2038.73  5104.5 2044.46  5150.9 2059.48
  5170.4 2068.01  5201.4 2074.29  5248.1 2077.13    5269 2083.04    5336 2095.45
  5377.7 2099.78  5396.8 2103.55  5425.9 2107.51  5437.6 2110.75  5498.9 2119.15
#Mann= 7 ,-1 , 0
  4601.7     .09       0  4893.1     .05       0  4988.9     .05       0
  5009.4     .09       0  5030.9     .05       0  5104.5     .09       0
  5201.4     .05       0
#Block Obstruct= 1 ,-1
  5201.4  5241.4    2080
Bank Sta=4988.9,5009.4
Exp/Cntr=0.5,0.3

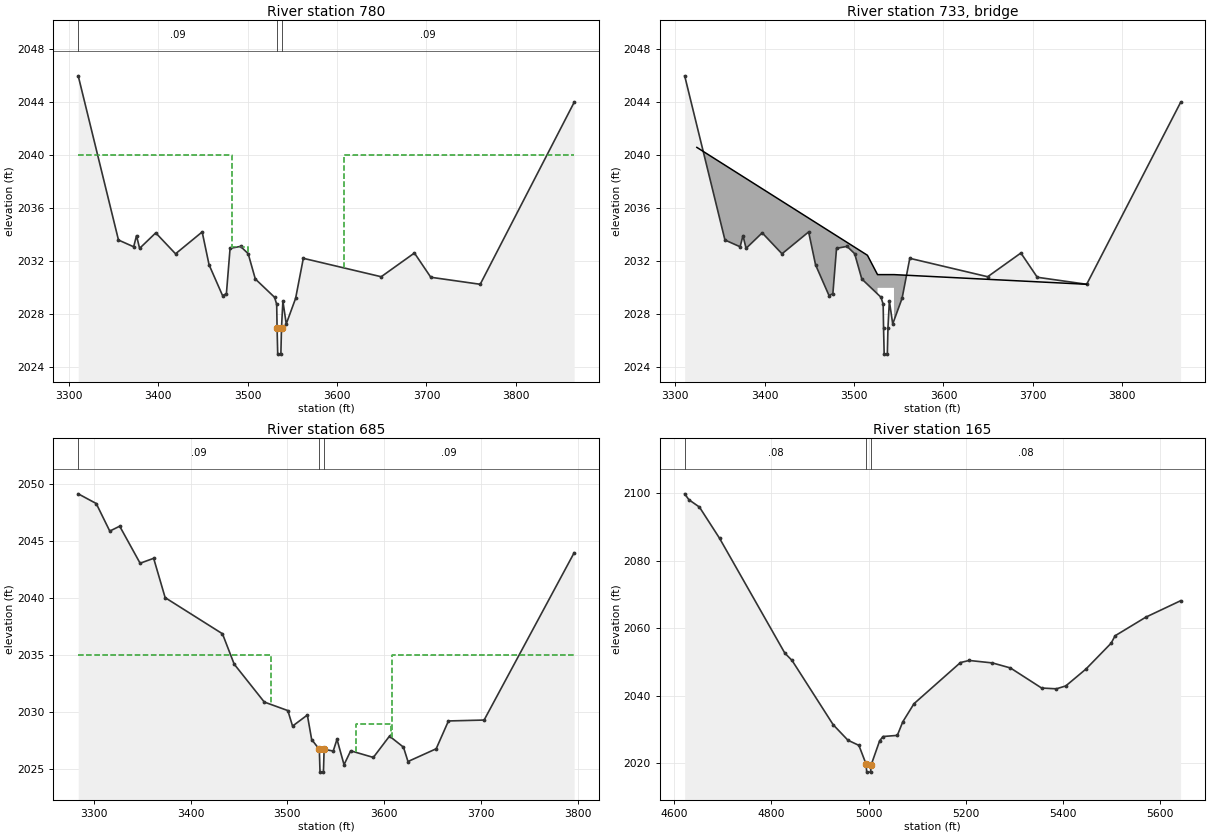
Type RM Length L Ch R = 1 ,780     ,95,95,95
BEGIN DESCRIPTION:
Herron_Cove_Bch_XS4
END DESCRIPTION:
XS GIS Cut Line= 6
       943282.02       722177.36       943237.06       722240.71
       943200.27       722302.02       943163.49       722516.61
       943112.39       722665.79  943099.2311743  722817.4067633
#Sta/Elev= 30
 3310.78    20463355.787 2033.613372.758  2033.1 3375.94 2033.943379.405 2032.98
3397.436 2034.153419.568 2032.573449.338 2034.223457.045 2031.743472.106 2029.42
 3476.42 2029.563480.521 2032.983492.259 2033.133500.744 2032.583508.735 2030.67
 3530.23 2029.293532.635 2028.763533.059    20273533.766    20253537.302    2025
3538.009    20273539.564    20293543.312 2027.283553.777 2029.213562.404 2032.23
3649.449 2030.843686.572 2032.633704.886  2030.83760.111 2030.273865.111    2044
#Mann= 3 ,-1 , 0
 3310.78     .09       03533.059     .05       03538.009     .09       0
#XS Ineff= 4 ,-1
 3310.783483.058    20403483.0593500.885  2033.1 3570.18    3607 2030.83
3608.0093865.111    2040
Permanent Ineff=
       F       F       F       F
Bank Sta=3533.059,3538.009
Skew Angle= 45
Exp/Cntr=0.5,0.3

Type RM Length L Ch R = 3 ,733     ,,,
BEGIN DESCRIPTION:
Herron_Cove_Bch_XS3
Structure ID: Herron Cove Rd
Approximate Survey Structure
END DESCRIPTION:
Bridge Culvert--1,0,-1,-1, 0
Deck Dist Width WeirC Skew NumUp NumDn MinLoCord MaxHiCord MaxSubmerge Is_Ogee
36,22,3,45, 7, 7, , , , 0, 1,1,,
3324.3923515.0283526.3423526.3423544.7263544.7263760.111
  2040.6 2032.46    2031    2031    2031    2031 2030.27
    2005    2005       0    2030    2030       0    2005
3324.3923515.0283526.3423526.3423544.7263544.7263760.111
  2040.6 2032.46    2031    2031    2031    2031 2030.27
    2005    2005       0    2030    2030       0    2005
Abutment Skew #Up #Dn= , 2 , 2
3526.3423528.109
    2030 2029.43
3526.3423528.109
    2030 2027.29
Abutment Skew #Up #Dn= , 2 , 2
3542.9583544.726
 2027.35    2030
3542.9583544.726
 2026.96    2030
BR Coef= 1 , 1 , 0 ,1.25, 0 ,,,0.8,0,2,0,
WSPro=,,,, 1 ,,,, 0 ,,,, 0 ,,,,-1 ,-1 ,-1 , 0 , 0 , 0 , 0 , 0
BC Design=,, 0 ,, 0 ,,,,,,
BC HTab HWMax=2034.22

Type RM Length L Ch R = 1 ,685     ,520,520,520
BEGIN DESCRIPTION:
Herron_Cove_Bch_XS2
END DESCRIPTION:
XS GIS Cut Line= 6
       943228.88       722148.75       943161.44       722285.67
       943124.66       722410.34       943128.74       722496.17
       943096.04       722596.31  943037.8060953  722800.1732013
#Sta/Elev= 30
3284.016 2049.173302.613 2048.323316.614  2045.93326.866 2046.333347.938 2043.08
3361.939 2043.513373.818 2040.063433.003 2036.893445.095 2034.233476.208  2030.9
3500.532 2030.153505.411 2028.793520.685 2029.763525.139 2027.613533.059 2026.75
3533.766 2024.753537.302 2024.753538.009 2026.753547.413  2026.63551.302 2027.63
3558.586  2025.43565.444 2026.62 3588.85 2026.043605.537 2027.913619.962 2026.94
3624.629 2025.683653.762  2026.83666.419 2029.24 3703.26 2029.32 3796.26    2044
#Mann= 3 ,-1 , 0
3284.016     .09       03533.059     .05       03538.009     .09       0
#XS Ineff= 4 ,-1
3284.0163483.059    20353483.0593500.178    2029 3570.88    3607    2029
3608.009 3796.26    2035
Permanent Ineff=
       F       F       F       F
Bank Sta=3533.059,3538.009
Skew Angle= 45
Exp/Cntr=0.5,0.3

Type RM Length L Ch R = 1 ,165     ,0,0,0
BEGIN DESCRIPTION:
Herron_Cove_Bch_XS1
END DESCRIPTION:
XS GIS Cut Line= 6
       942525.86       722537.04       942783.36       722741.41
        942836.5       722823.16       943006.12       722841.55
       943226.84       722939.64       943380.11       723037.74
#Sta/Elev= 30
  4621.3 2099.83    4630 2098.08  4651.7  2095.9  4693.1 2086.65  4827.5 2052.61
  4842.3 2050.46    4927  2031.4  4957.3 2026.82  4979.9 2025.29  4994.5 2019.81
    4996 2017.36    5004 2017.36 5005.22 2019.53  5022.6 2026.65  5029.6 2027.91
    5059 2028.25  5070.2 2032.26  5093.3 2037.64  5188.9 2049.83  5206.9 2050.45
  5254.7 2049.72  5291.8 2048.23    5356 2042.28  5386.3 2042.05  5405.7  2042.9
  5447.2  2047.9  5499.1 2055.57  5507.2 2057.76  5570.6 2063.29  5642.1 2068.15
#Mann= 3 ,-1 , 0
  4621.3     .08       0  4994.5     .05       0 5005.22     .08       0
Bank Sta=4994.5,5005.22
Exp/Cntr=0.3,0.1

Chan Stop Cuts=-1
Use User Specified Reach Order=0
User Specified Reach Order=Herron Cove Bran,Reach-1