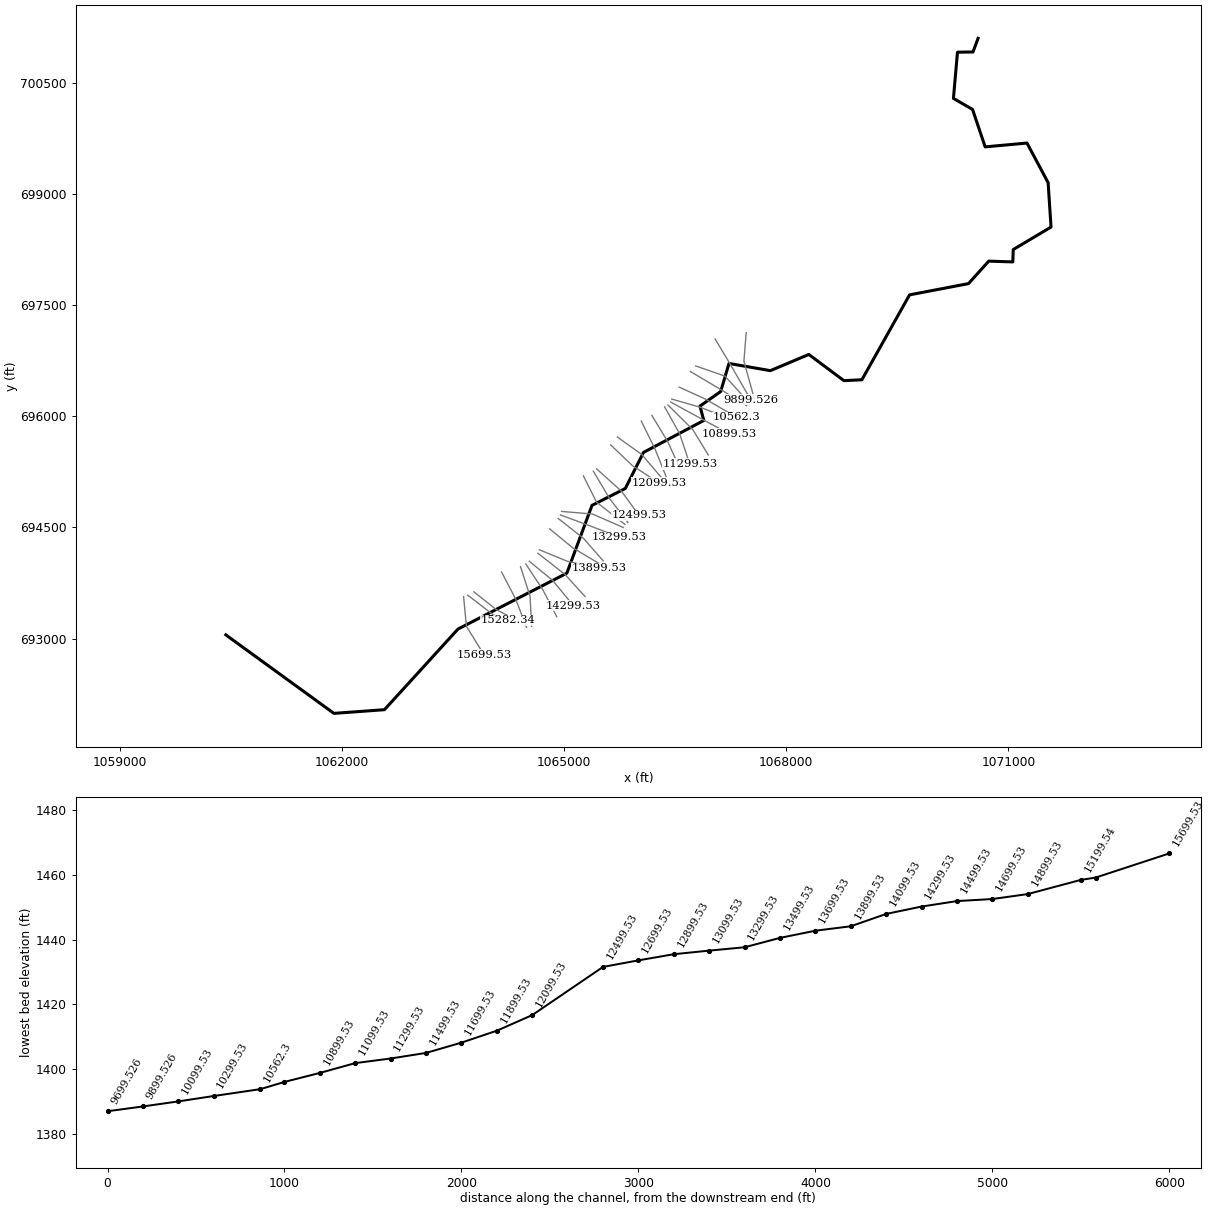
--- BrevardCreek.prj (project) ---

Proj Title=Brevard Creek
Current Plan=p02
Default Exp/Contr=0.3,0.1
English Units
Geom File=g02
Flow File=f01
Plan File=p02
Y Axis Title=Elevation
X Axis Title(PF)=Main Channel Distance
X Axis Title(XS)=Station
BEGIN DESCRIPTION:
END DESCRIPTION:
DSS Export Rating Curves= 0
DSS Export Rating Curve Sorted= 0
DSS Export Volume Flow Curves= 0
DXF OffsetX= 0
DXF OffsetY= 0
DXF ScaleX= 1
DXF ScaleY= 10

--- BrevardCreek.p02 (plan) ---

Plan Title=Flood Plain
Program Version=3.12
Short Identifier=Flood Plain
Geom File=g02
Flow File=f01
Subcritical Flow
K Sum by GR= 0
Std Step Tol= 0.01
Critical Tol= 0.01
Num of Std Step Trials= 20
Max Error Tol= 0.3
Flow Tol Ratio= 0.001
Split Flow NTrial= 30
Split Flow Tol= 0.02
Split Flow Ratio= 0.02
Log Output Level= 0
Friction Slope Method= 1
Unsteady Friction Slope Method= 2
Unsteady Bridges Friction Slope Method= 1
Parabolic Critical Depth
Global Vel Dist= 0 , 0 , 0
Global Log Level= 0
CheckData=True
Encroach Param=-1 ,0,0, 2
Encroach River=Brevard Creek
Encroach Reach=Main
Encroach Node=15699.53
       1  400.14  426.53
Encroach Node=15282.34
       1  379.57  461.29
Encroach Node=15199.54
       1     363     418
Encroach Node=14899.53
       1  365.07  439.59
Encroach Node=14699.53
       1  365.62  442.33
Encroach Node=14499.53
       1  357.33  440.35
Encroach Node=14299.53
       1   386.3   431.9
Encroach Node=14099.53
       1  451.23  494.26
Encroach Node=13899.53
       1  330.11  428.94
Encroach Node=13699.53
       1  373.34  428.27
Encroach Node=13499.53
       1   394.4  451.47
Encroach Node=13299.53
       1     430     460
Encroach Node=13099.53
       1     402     450
Encroach Node=12899.53
       1     402     447
Encroach Node=12699.53
       1     401     446
Encroach Node=12499.53
       1     438     473
Encroach Node=12099.53
       1  389.87  427.89
Encroach Node=11899.53
       1  380.88  444.69
Encroach Node=11699.53
       1     358  426.36
Encroach Node=11499.53
       1     358  436.15
Encroach Node=11299.53
       1  382.52  444.03
Encroach Node=11099.53
       1  407.62  496.79
Encroach Node=10899.53
       1     450  533.63
Encroach Node=10699.53
       1  357.37  429.58
Encroach Node=10562.3
       1  372.84  417.35
Encroach Node=10299.53
       1  454.39  502.22
Encroach Node=10099.53
       1   408.1  449.64
Encroach Node=9899.526
       1  374.67  412.24
Encroach Node=9699.526
       1  365.72     420
Encroach Node=9499.526
       1  375.07  422.28
Encroach Node=9299.526
       1  444.15  506.68
Encroach Node=9099.526
       1  406.08  460.88
Encroach Node=8899.526
       1  386.42  431.09
Encroach Node=8699.526
       1  382.94  429.59
Encroach Node=8499.526
       1     360     445
Encroach Node=8204.383
       1  348.13  611.28
Encroach Node=8111.639
       1  207.42     357
Encroach Node=7699.526
       1     420  602.49
Encroach Node=7499.526
       1     360  517.73
Encroach Node=7299.526
       1     340  479.51
Encroach Node=7099.526
       1  334.31  444.33
Encroach Node=6899.526
       1     360     440
Encroach Node=6699.526
       1  391.96  456.84
Encroach Node=6499.526
       1  365.54  428.18
Encroach Node=6299.526
       1  398.04  444.41
Encroach Node=6099.526
       1  384.64  434.51
Encroach Node=5899.526
       1     370  434.92
Encroach Node=5699.526
       1   366.5  452.42
Encroach Node=5499.526
       1     400  459.61
Encroach Node=5299.526
       1  443.27  494.04
Encroach Node=5099.526
       1  376.78  446.71
Encroach Node=4899.526
       1     410     543
Encroach Node=4662.338
       1  392.29     610
Encroach Node=4517.324
       1     235     422
Encroach Node=4099.526
       1     400  503.33
Encroach Node=3899.526
       1  457.13  579.65
Encroach Node=3699.526
       1     385     482
Encroach Node=3499.526
       1     320  462.06
Encroach Node=3299.526
       1  346.48  458.98
Encroach Node=3099.526
       1  419.37     502
Encroach Node=2636.785
       1   313.9  554.56
Encroach Node=2515.114
       1  202.05  397.22
Encroach Node=2499.526
       1  215.21  401.22
Encroach Node=2395.792
       1  249.01  461.19
Encroach Node=2099.526
       1  359.75  464.09
Encroach Node=1899.526
       1     368     453
Encroach Node=1497.169
       1     270     440
Encroach Node=1403.503
       1  430.98     571
Encroach Node=1099.526
       1   361.4  445.58
Encroach Node=899.526
       1  345.86  458.63
Encroach Node=699.526
       1   372.4  434.41
Encroach Node=499.526
       1  365.22  479.47
Encroach Node=299.526
       1  307.35     481
Encroach Node=99.526
       1  377.16  491.77
Computation Interval=1HOUR
Output Interval=1HOUR
Run HTab= 0
Run UNet= 0
Run PostProcess= 0
UNET Theta= 1
UNET Theta Warmup= 1
UNET ZTol= 0.02
UNET ZSATol= 0.05
UNET MxIter= 20
UNET MaxInSteps= 0
UNET DtIC= 0
UNET DtMin= 0
UNET MaxCRTS= 20
UNET WFStab= 2
UNET SFStab= 1
UNET WFX= 1
UNET SFX= 1
UNET DSS MLevel= 4
UNET DZMax Abort= 100
UNET Convert EG Bridges=-1
UNET Use Existing IB Tables=-1
UNET Froude Reduction=False
UNET Froude Limit= 1
UNET Froude Power= 10
Instantaneous Interval=1HOUR
Write IC File= 0
Echo Input=False
Echo Output=False
Write Detailed= 0
Detailed Automatic Start=False, 10

--- BrevardCreek.f01 (steady flow) ---

Flow Title=FP 100yr flows
Program Version=3.12
Number of Profiles= 2
Profile Names=P100yr,FWY
River Rch & RM=Brevard Creek,Main            ,15699.53
     826     826
River Rch & RM=Brevard Creek,Main            ,14899.53
     903     903
River Rch & RM=Brevard Creek,Main            ,13499.53
    1000    1000
River Rch & RM=Brevard Creek,Main            ,11899.53
    1100    1100
River Rch & RM=Brevard Creek,Main            ,8699.526
    1210    1210
River Rch & RM=Brevard Creek,Main            ,7499.526
    1340    1340
River Rch & RM=Brevard Creek,Main            ,7099.526
    1440    1440
River Rch & RM=Brevard Creek,Main            ,4517.324
    1600    1600
River Rch & RM=Brevard Creek,Main            ,99.526
    1600    1600
Boundary for River Rch & Prof#=Brevard Creek,Main            , 1
Up Type= 0
Dn Type= 3
Dn Slope=0.00221
DSS Import GetInterval= 0
DSS Import GetPeak= 0
DSS Import FillOption= 0

--- BrevardCreek.g02 (geometry) ---

Geom Title=Geometery
Program Version=3.12

River Reach=Brevard Creek   ,Main
Reach XY= 30
  1060429.501245   693049.560829  1061890.130764   691988.999944
  1062572.249937   692038.749947   1063565.75112   693127.941892
  1065036.247895   693882.941181  1065376.498525    694798.94195
  1065826.128728   695026.810621  1066072.249187   695514.439436
  1066886.497103   695945.879291  1066834.748242    696140.30825
  1067114.378047   696336.248595  1067226.755927   696716.058389
  1067785.749315   696618.811151  1068305.249095   696837.558026
  1068779.250498   696483.630858  1069022.245695   696495.750921
  1069666.378569   697642.688262  1070462.378853   697794.629384
  1070735.881051   698098.437917  1071061.001038   698087.808773
   1071067.00169   698254.880537  1071577.379673   698558.689031
  1071537.881948   699158.748931  1071252.378447    699693.50223
  1070687.253335   699641.810691  1070517.130059   700147.691293
  1070258.881381   700296.560398  1070313.501554   700920.938369
   1070523.13071   700923.940637  1070591.628128   701108.059918

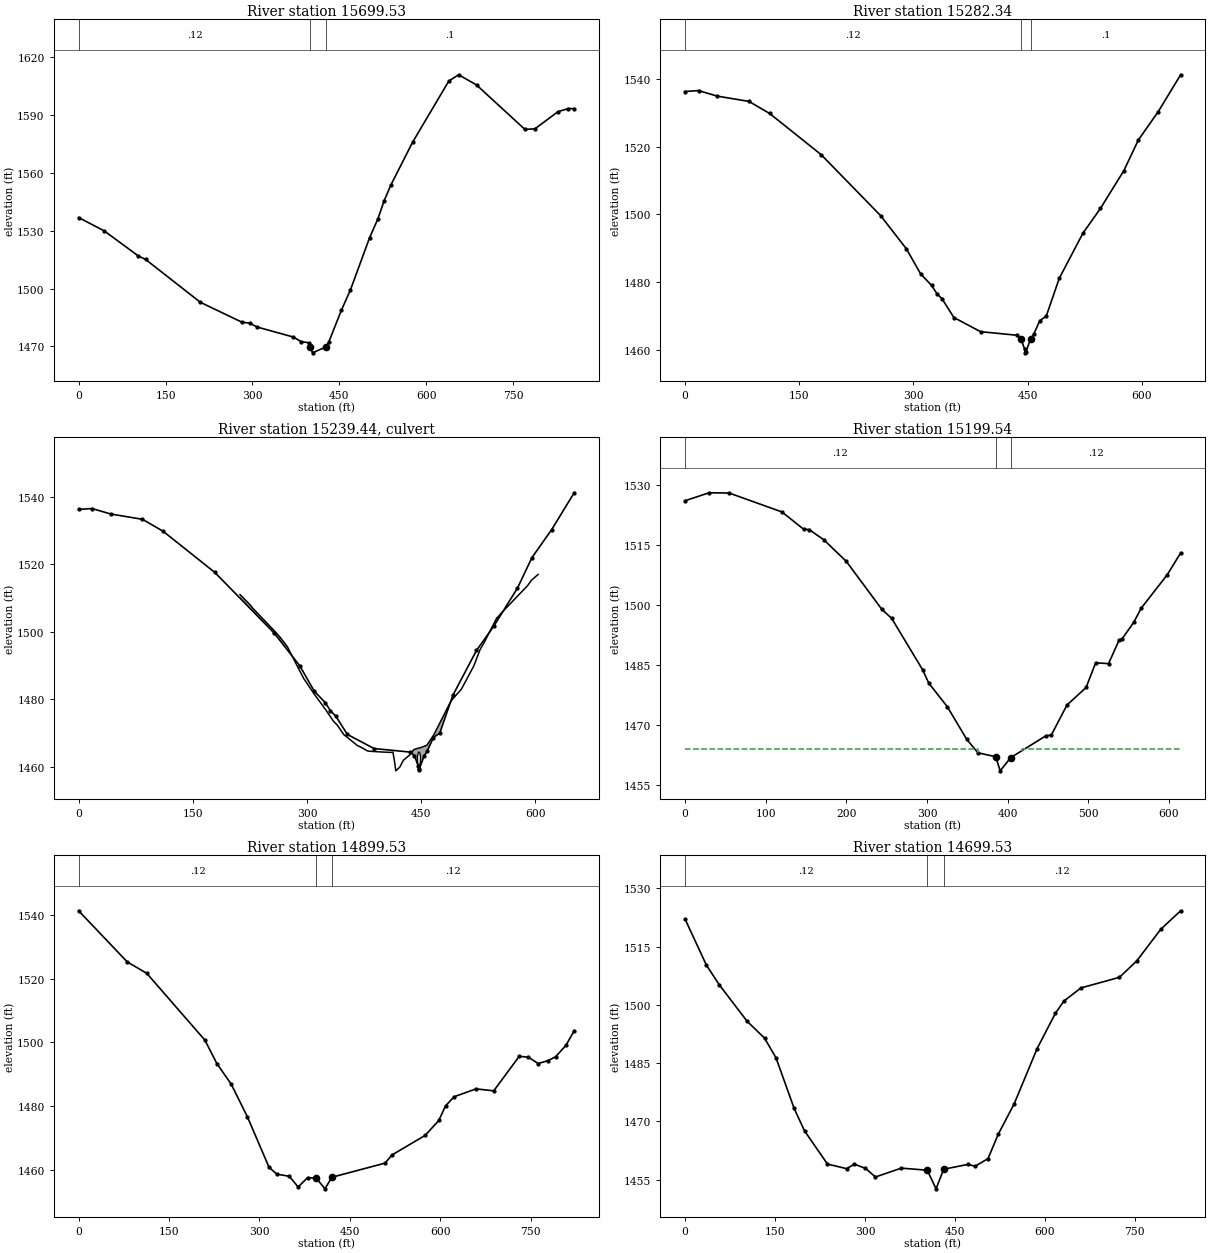
Type RM Length L Ch R = 1 ,15699.53,390.37,417.19,435.24
XS GIS Cut Line= 3
   1063641.77677   693566.315359  1063680.017524   693164.379911
  1063917.547232   692780.260353
#Sta/Elev= 30
       0 1536.88   44.25 1529.94  103.06 1516.95  115.47 1515.18  210.18 1492.91
  281.89  1482.6  295.29 1482.12  307.78 1480.12  370.54 1474.91  384.21 1472.52
  397.36 1471.92  400.14 1469.53  403.75 1466.71  426.53 1469.74   431.5 1472.09
  453.63 1488.87  468.88 1499.11  502.26 1526.45   516.5 1536.13  527.25 1545.51
  539.28 1553.94  576.71 1576.07  639.03 1607.69  655.94 1610.92  686.83 1605.64
  770.39 1582.58  787.69  1582.9  827.44 1591.79  845.41 1593.41  855.38 1593.34
#Mann= 3 , 0 , 0
       0     .12       0  400.14     .05       0  426.53      .1       0
Bank Sta=400.14,426.53
Exp/Cntr=0.5,0.3

Type RM Length L Ch R = 1 ,15282.34,84.48,82.8,81.82
XS GIS Cut Line= 3
  1063698.243641   693586.318773  1064045.516818   693317.452641
   1064244.54087   693244.638973
#Sta/Elev= 30
       0 1536.25   17.62 1536.52   42.25 1534.89   83.87 1533.33  111.09 1529.77
  178.84 1517.62  256.78 1499.69  290.68 1489.91   309.6 1482.45  323.97 1479.07
   330.8 1476.68  337.78 1475.09  353.16 1469.63  388.23 1465.46   435.8 1464.41
  441.28 1463.34  446.25 1460.24  446.68 1459.22  447.83 1459.54  454.06 1463.31
  457.92 1464.64  466.11 1468.72  474.52 1470.02  491.67  1481.2  522.75 1494.49
   545.7 1501.77   576.6 1512.96  595.65 1521.99  621.61 1530.29  651.12 1541.18
#Mann= 3 , 0 , 0
       0     .12       0  441.28     .05       0  454.06      .1       0
#XS Ineff= 2 , 0
       0  417.24    1464   477.2       0  1465.8
Permanent Ineff=
       F       F
Bank Sta=441.28,454.06
Exp/Cntr=0.5,0.3

Type RM Length L Ch R = 2 ,15239.44,,,
BEGIN DESCRIPTION:
37111-0219  Gravel Road
END DESCRIPTION:
Bridge Culvert--1,0,-1,-1, 0
Deck Dist Width WeirC Skew NumUp NumDn MinLoCord MaxHiCord MaxSubmerge Is_Ogee
28,30,2.6,0, 50, 28, , , 0.95, 0, 0,0,,
  211.97  215.08  226.77  228.76  254.46  256.23  257.13  265.28  274.34  287.36
  295.82  310.37  311.81  325.27  335.02   339.8  348.56  364.07  366.12  368.66
   380.1  384.83  385.42  396.38  410.67  412.97  415.13   416.7  422.09  426.51
  435.67  440.38   444.1  450.24  457.53  466.92  487.09  490.99  499.88  503.01
  519.11  527.52  532.99  549.56  550.78  551.26  554.63  589.78  595.11   603.7
 1511.05 1510.37 1507.65 1507.01 1500.97 1500.55 1500.32 1498.26 1495.58 1489.84
 1486.17 1481.33 1480.89 1476.73  1473.5 1472.41 1469.55 1466.76 1466.35 1466.13
  1464.7 1464.63 1464.62 1464.46 1464.31  1464.4 1461.57 1458.86 1459.99 1461.94
 1463.69 1465.14 1465.44  1465.8 1466.44 1469.62 1478.59 1480.02 1482.25 1483.07
 1489.86 1494.78 1496.91 1504.19 1504.31  1504.5 1505.38 1513.66  1515.3 1517.01
                                                                                
                                                                                
                                                                                
                                                                                
                                                                                
  181.74  211.97  215.08  226.77  228.76  254.46  256.23  257.13  265.28  274.34
  287.36  295.82  310.37  311.81  325.27  335.02   339.8  348.56  364.07  366.12
  368.66   380.1  384.83  385.42  396.38  410.67  412.97  430.99
 1514.24 1511.05 1510.37 1507.65 1507.01 1500.97 1500.55 1500.32 1498.26 1495.58
 1489.84 1486.17 1481.33 1480.89 1476.73  1473.5 1472.41 1469.55 1466.76 1466.35
 1466.13  1464.7 1464.63 1464.62 1464.46 1464.31  1464.4 1465.42
                                                                                
                                                                                
                                                                
BR Coef=-1 , 1 , 0 ,, 0 ,,,0.8,0,,0,
WSPro=,,,, 1 ,,,, 0 ,,,, 0 ,,,,-1 ,-1 ,-1 , 0 , 0 , 0 , 0 , 0
Culvert=1,4,,30,0.024,0.9,1,2,3,1460.39,447.22,1459.55,390.72,Culvert #1  , 0 ,28
Culvert Bottom n=0.024
BC Design=,, 0 ,, 0 ,,,,,,

Type RM Length L Ch R = 1 ,15199.54,303.81,300.02,294.31
XS GIS Cut Line= 3
  1063780.960488   693630.551402  1064084.350794   693390.266308
  1064285.840787   693284.725299
#Sta/Elev= 30
       0 1526.06    29.7 1528.05   54.63 1527.99  120.18 1523.25  146.92 1518.94
  153.71 1518.86  171.82 1516.33  199.87 1510.91  244.02 1498.89  256.09 1496.67
  294.73 1483.72  302.16 1480.46  325.15 1474.55  349.27 1466.39  363.08 1463.03
  385.14 1462.05  390.71 1458.52  403.71 1461.82  447.56  1467.3  454.07 1467.45
  473.54 1474.98  497.25 1479.36   509.1 1485.55  525.08 1485.32  538.28 1491.26
  542.04 1491.57  556.21 1495.62   565.7 1499.22  598.08 1507.61  614.48 1513.01
#Mann= 3 , 0 , 0
       0     .12       0  385.14     .05       0  403.71     .12       0
#XS Ineff= 2 , 0
       0     363    1464     418       0    1464
Permanent Ineff=
       F       F
Bank Sta=385.14,403.71
Exp/Cntr=0.5,0.3

Type RM Length L Ch R = 1 ,14899.53,201.22,200,197.61
XS GIS Cut Line= 3
  1064154.145844    693898.55646  1064344.040993   693536.537002
  1064491.400653   693150.227318
#Sta/Elev= 30
       0 1541.24   80.69 1525.22   113.1 1521.64  209.58  1500.7  229.32 1493.38
  253.09 1486.96  280.06 1476.68  316.04 1460.85  329.02 1458.72  349.62 1458.06
  364.28  1454.7  380.03 1457.67  394.66 1457.39   408.8 1454.13  419.99 1457.75
  508.31 1462.18  520.26 1464.78  574.91 1470.86  597.61 1475.54  608.78 1480.12
  623.17 1482.99  659.39 1485.45  688.75 1484.83  731.14 1495.65  746.44 1495.35
  762.57 1493.38   778.7  1494.3  791.29 1495.48  808.57 1499.08  822.26 1503.63
#Mann= 3 , 0 , 0
       0     .12       0  394.66     .05       0  419.99     .12       0
Bank Sta=394.66,419.99
Exp/Cntr=0.3,0.1

Type RM Length L Ch R = 1 ,14699.53,197.9,200,203.16
XS GIS Cut Line= 3
   1064410.49326   693970.240694  1064539.732204   693572.123189
    1064559.2504   693164.690911
#Sta/Elev= 30
       0 1522.06   35.51 1510.23   57.29 1505.09  103.37 1495.78  132.56  1491.4
  151.69 1486.32  181.85 1473.32  199.16 1467.54  237.45 1458.98  269.33  1457.8
  282.44 1458.94  300.85 1457.87   317.5 1455.65  360.54 1457.93  403.86  1457.4
  418.57  1452.6  431.23 1457.65  472.16 1458.91  483.47 1458.41  505.24 1460.38
  522.14 1466.63  548.83 1474.49  587.14 1488.73  617.41 1497.78  631.75 1500.96
   660.2 1504.35  724.28 1507.07  753.03 1511.26  793.32 1519.46  826.47 1524.22
#Mann= 3 , 0 , 0
       0     .12       0  403.86     .05       0  431.23     .12       0
Bank Sta=403.86,431.23
Exp/Cntr=0.3,0.1

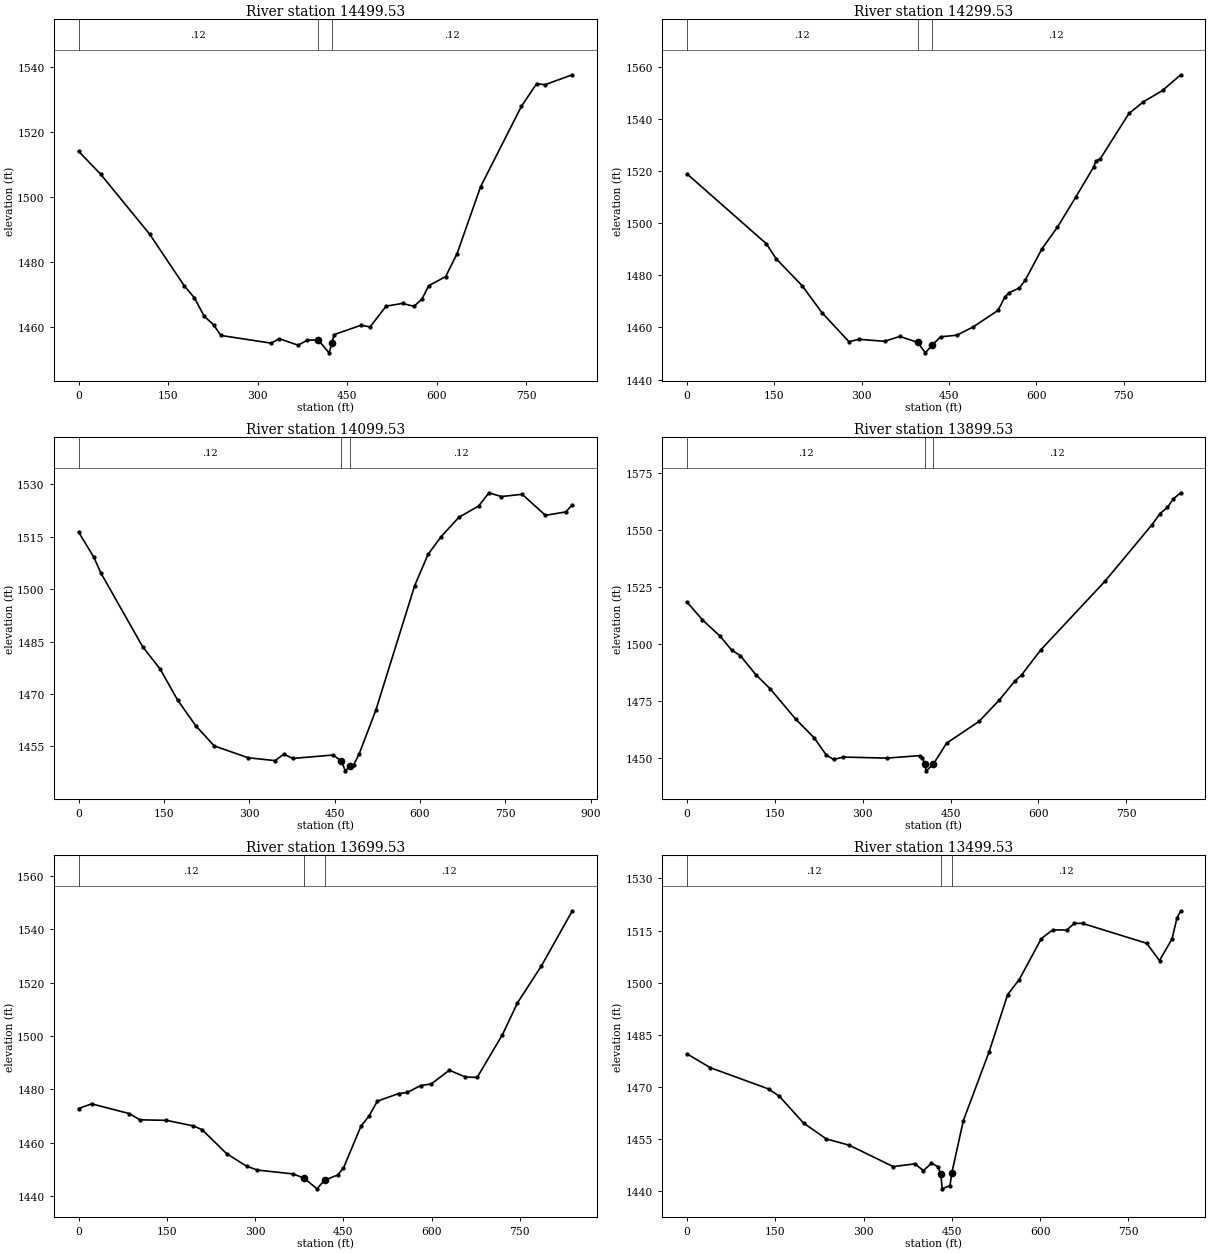
Type RM Length L Ch R = 1 ,14499.53,197.9,200,200.53
XS GIS Cut Line= 3
  1064482.051354   694006.722792   1064713.55874   693656.357481
  1064900.315695   693294.018208
#Sta/Elev= 30
       0 1514.12   36.92 1507.06  119.18 1488.55  177.46 1472.55  194.27 1468.92
  210.59 1463.23  226.34 1460.63  238.39 1457.33  323.04 1454.94  336.42 1456.33
  368.07 1454.31  383.19 1455.85  401.41 1455.97  419.94 1451.96   424.8 1455.06
  428.27 1457.58   473.8 1460.49  488.62 1459.95  515.56 1466.36  543.16  1467.2
  562.17 1466.29  575.47 1468.51  586.87 1472.66   615.3 1475.47  634.38 1482.53
  673.87 1503.19  742.29 1527.99  767.79 1534.96  781.76 1534.64  827.58  1537.7
#Mann= 3 , 0 , 0
       0     .12       0  401.41     .05       0   424.8     .12       0
Bank Sta=401.41,424.8
Exp/Cntr=0.3,0.1

Type RM Length L Ch R = 1 ,14299.53,199.38,200,200.63
XS GIS Cut Line= 3
  1064528.976998   694044.437084  1064845.403396   693784.367533
   1065124.30716   693445.720798
#Sta/Elev= 30
       0    1519  136.48 1492.14  153.22 1486.41  198.18 1475.98  231.78 1465.74
  278.26 1454.56   295.7 1455.45  339.49 1454.71  365.63 1456.57   396.3 1454.29
  409.59 1450.27  420.83 1453.14  435.68 1456.42  463.69 1457.05  492.06 1460.27
  534.38 1466.57   545.9 1471.56   553.1 1473.33  570.91 1475.16  581.18 1478.18
  609.89  1490.2  636.51 1498.53  667.78 1509.98  698.51 1521.55  702.68 1523.96
  709.92 1524.73  759.47 1542.21  784.18 1546.64  817.14 1551.03   848.3 1557.03
#Mann= 3 , 0 , 0
       0     .12       0   396.3     .05       0  420.83     .12       0
Bank Sta=396.3,420.83
Exp/Cntr=0.3,0.1

Type RM Length L Ch R = 1 ,14099.53,197.87,200,204.6
XS GIS Cut Line= 3
   1064645.27632   694152.355136  1065014.209661   693862.953767
  1065282.270681   693567.388674
#Sta/Elev= 30
       0 1516.38   26.45 1509.26    39.5 1504.57  112.47 1483.58  143.56  1477.1
  174.19 1468.23  205.94 1460.92  238.49 1455.13  298.46 1451.72  345.43 1450.92
  360.84 1452.77  376.56 1451.54  447.56 1452.52  462.17 1450.73   468.9 1447.99
  477.49 1449.32   483.3 1449.58  493.34 1452.89  522.47 1465.31  590.77 1500.97
   614.2 1509.93  637.23 1515.01   668.4 1520.56  703.04 1523.77  721.48 1527.59
  743.26 1526.51  779.76 1527.16  820.67 1521.13  856.27 1522.11  867.92 1524.15
#Mann= 3 , 0 , 0
       0     .12       0  462.17     .05       0  477.49     .12       0
Bank Sta=462.17,477.49
Exp/Cntr=0.3,0.1

Type RM Length L Ch R = 1 ,13899.53,202.12,200,197.5
XS GIS Cut Line= 3
  1064666.027291   694198.600255  1065044.040485   694043.529211
  1065468.056422   693950.055371
#Sta/Elev= 30
       0 1518.26   26.51 1510.38   56.52 1503.24   76.26 1497.17   91.22 1494.69
  117.39 1486.41   142.3 1480.08  185.47  1466.9  216.99 1458.69  237.71 1451.15
  250.19 1449.16  267.09 1450.21  341.01 1449.75  397.52 1450.86     402 1449.99
  405.49 1447.14  408.58 1444.17  420.56 1447.14  443.16 1456.31  498.38 1465.82
  533.07  1475.2  559.51 1483.54  571.03 1486.19  604.03 1497.27  713.62 1527.38
  793.92  1552.2  807.54 1557.05  820.17 1559.73  829.88 1563.44  842.78 1566.15
#Mann= 3 , 0 , 0
       0     .12       0  405.49     .05       0  420.56     .12       0
Bank Sta=405.49,420.56
Exp/Cntr=0.3,0.1

Type RM Length L Ch R = 1 ,13699.53,199.81,200,197.24
XS GIS Cut Line= 3
   1064803.60494   694481.925009  1065117.102083    694225.22131
  1065489.927932   694003.183654
#Sta/Elev= 30
       0 1472.86   22.18 1474.61   86.05 1470.97  104.44 1468.63  149.33 1468.43
  195.18 1466.35  209.91 1464.94  251.92 1455.91  285.65 1451.28  303.71 1449.83
  364.64 1448.38  383.34 1446.81  405.19  1442.8  418.27 1446.08  440.08 1447.92
  450.22  1450.6  479.95 1466.25  493.96 1470.14  507.76 1475.61  543.92 1478.45
  558.44 1478.86  581.21 1481.43  599.49 1482.07  630.13 1487.19  657.49 1484.64
  677.45  1484.5  720.45 1500.53  745.86 1512.37   786.6 1526.23  839.12 1546.86
#Mann= 3 , 0 , 0
       0     .12       0  383.34     .05       0  418.27     .12       0
Bank Sta=383.34,418.27
Exp/Cntr=0.3,0.1

Type RM Length L Ch R = 1 ,13499.53,198.14,200,202.81
XS GIS Cut Line= 3
  1064920.554223   694621.611538  1065261.130145   694353.137923
  1065528.593399   694048.706497
#Sta/Elev= 30
       0 1479.48    39.7 1475.48  138.97 1469.34  157.11 1467.22  198.26 1459.51
  236.96 1454.95  275.84 1453.15  350.33 1446.99   386.9 1447.77  401.88 1445.85
  415.39 1447.94   426.4 1446.97  431.34 1444.81  433.67 1440.58  446.86 1441.52
  450.14 1445.26   469.5 1460.19  513.26 1480.02   544.9 1496.56  564.47 1500.85
  602.21  1512.7  621.42 1515.19   645.4 1515.14  658.32  1517.1  672.11 1517.05
  781.04 1511.32  802.88 1506.34  824.09 1512.59  832.55 1518.62  838.91 1520.69
#Mann= 3 , 0 , 0
       0     .12       0  431.34     .05       0  450.14     .12       0
Bank Sta=431.34,450.14
Exp/Cntr=0.3,0.1

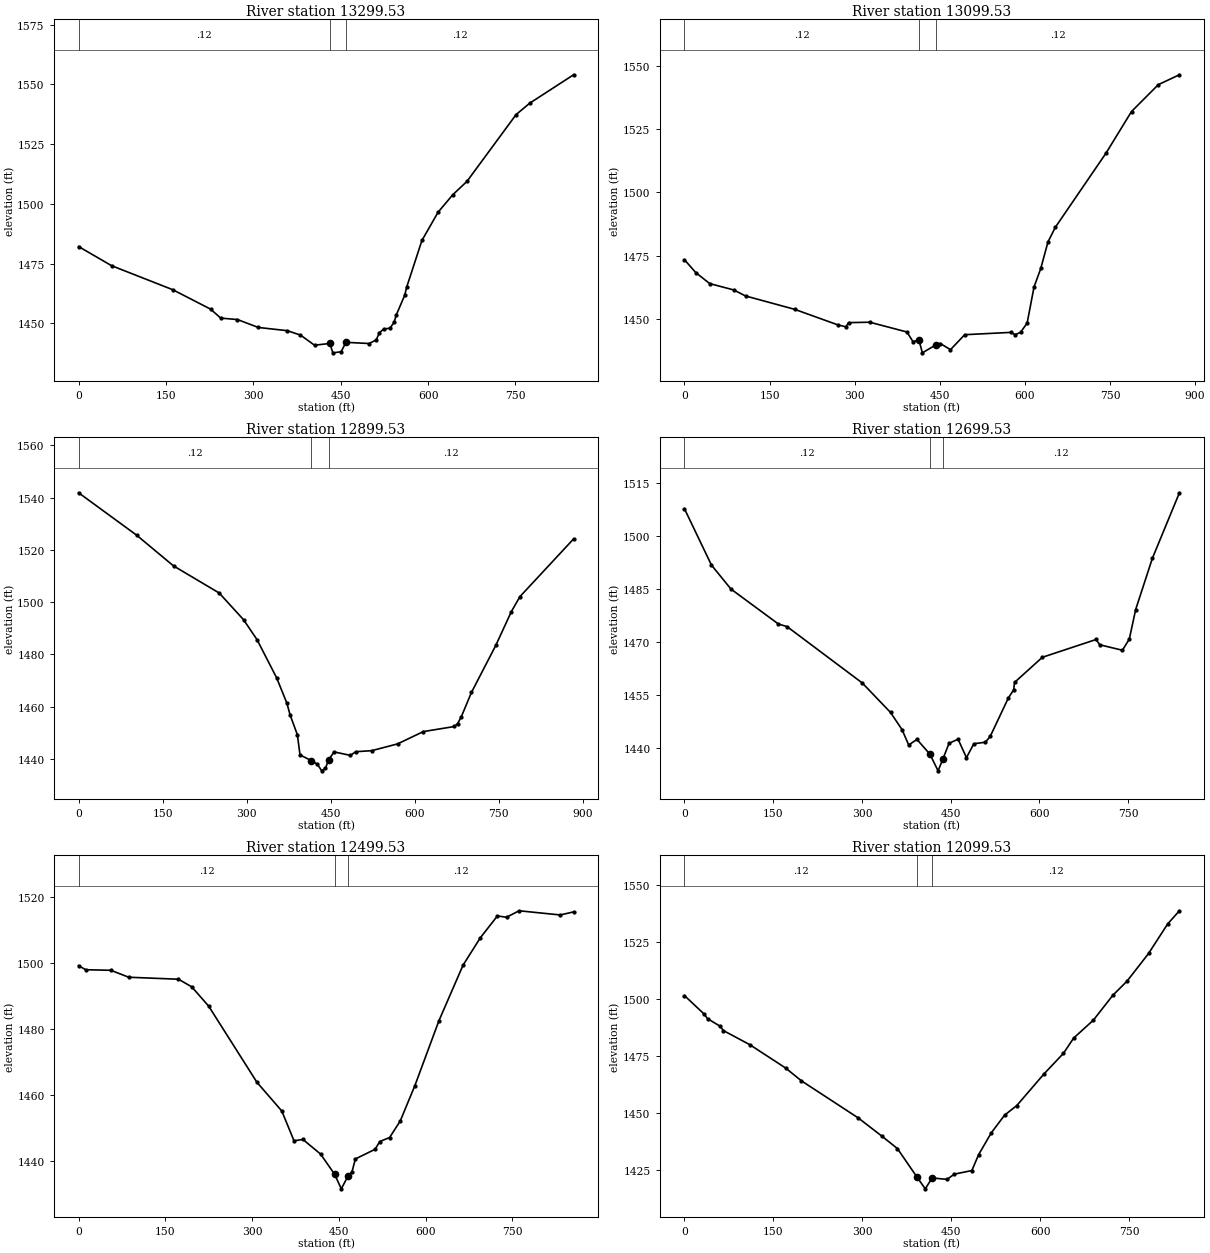
Type RM Length L Ch R = 1 ,13299.53,198.48,200,193.34
XS GIS Cut Line= 3
  1064950.145235   694669.649955  1065359.539942   694518.016221
  1065745.329416   694369.905315
#Sta/Elev= 30
       0 1482.14   56.81 1474.12  161.83 1464.07  226.82 1455.93     244 1452.21
  272.71 1451.61   308.6  1448.3  358.31 1446.95  380.94  1445.1  405.07 1440.88
   431.3  1441.6  436.57 1437.68  450.77 1438.12   458.9 1442.08  498.71 1441.58
  510.99 1443.08  516.37 1446.06  523.59  1447.6  534.67 1448.01   541.7 1450.47
  545.57 1453.61   559.8 1461.73  563.44 1465.29  589.44 1484.69  617.11 1496.49
  642.38 1503.81  666.76 1509.41  751.15 1537.36  774.56 1542.13  849.82 1554.01
#Mann= 3 , 0 , 0
       0     .12       0   431.3     .05       0   458.9     .12       0
Bank Sta=431.3,458.9
Exp/Cntr=0.3,0.1

Type RM Length L Ch R = 1 ,13099.53,206.18,200,204.92
XS GIS Cut Line= 3
  1064965.652393   694717.133713  1065383.504761   694681.767766
  1065798.564381   694500.189573
#Sta/Elev= 30
       0  1473.4   20.08 1468.29    44.6 1463.97   86.83 1461.47  107.73 1459.09
  194.03 1453.83  270.39 1447.68   284.6 1446.91   289.2 1448.56  326.58 1448.73
  392.15 1444.87  402.81 1441.04  413.25 1441.72  419.35 1436.64  443.11 1439.78
  450.93 1440.32  468.91 1437.89  493.93  1443.8   574.8 1444.71  582.99 1443.83
  592.35 1444.74  603.98 1448.37  616.11  1462.6  628.01 1469.95  640.69  1480.4
  653.67  1486.2  743.04 1515.49  787.98 1531.91  835.17 1542.51  872.39 1546.41
#Mann= 3 , 0 , 0
       0     .12       0  413.25     .05       0  443.11     .12       0
Bank Sta=413.25,443.11
Exp/Cntr=0.3,0.1

Type RM Length L Ch R = 1 ,12899.53,199.26,200,197.69
XS GIS Cut Line= 3
  1065260.268681   695196.931839  1065437.202886   694842.973912
  1065820.889071   694542.071527
#Sta/Elev= 30
       0 1541.81  103.39 1525.63  169.41 1513.86  250.96 1503.49  294.57 1493.24
  318.38 1485.68  353.44 1471.07  371.63 1461.41  377.51 1456.85  390.39 1449.33
  395.11 1441.62  415.32 1439.43  426.27 1438.04  433.79 1435.53  440.58 1436.51
  446.04  1439.7  455.93 1442.77  485.13 1441.43  494.47 1442.84  523.09 1443.24
   569.3 1445.83  615.12 1450.53  670.74 1452.48  676.24 1453.57  682.94 1456.18
  701.02 1465.48  744.41 1483.44  772.37 1496.43  787.59 1502.12  883.32 1524.17
#Mann= 3 , 0 , 0
       0     .12       0  415.32     .05       0  446.04     .12       0
Bank Sta=415.32,446.04
Exp/Cntr=0.3,0.1

Type RM Length L Ch R = 1 ,12699.53,197.48,200,199.55
XS GIS Cut Line= 3
  1065394.266802   695260.399625  1065613.590511   694892.100906
   1065861.07641   694567.783235
#Sta/Elev= 30
       0 1507.83   45.62 1491.88   78.71 1485.07  158.83 1475.19   173.5 1474.45
  300.58  1458.5  348.36 1450.15  367.71 1445.31  379.06 1440.95  393.02 1442.52
  415.01 1438.33  428.66 1433.63  436.94    1437   447.2 1441.41  462.49 1442.59
  476.65 1437.35  489.07 1441.29  508.83 1441.74  516.95 1443.42  547.45 1454.25
  556.45 1456.55   557.9 1458.65  604.93 1465.77  695.79 1470.81  701.88 1469.32
  740.29 1467.76  751.93 1470.93  762.65 1479.28  790.92  1493.8  836.62 1512.34
#Mann= 3 , 0 , 0
       0     .12       0  415.01     .05       0  436.94     .12       0
Bank Sta=415.01,436.94
Exp/Cntr=0.3,0.1

Type RM Length L Ch R = 1 ,12499.53,400.16,400,402.71
XS GIS Cut Line= 3
  1065438.814936    695291.71034  1065776.328626   694987.765609
  1066012.765524   694663.128006
#Sta/Elev= 30
       0 1499.28   12.34 1498.06   55.61 1497.89    86.8 1495.78  172.71 1495.18
  195.62 1492.87  224.84 1487.03  308.28 1463.93  351.28 1455.22  372.45 1446.17
  387.81 1446.59  418.44 1442.13  442.71    1436   454.2  1431.6  465.74 1435.45
  472.51 1436.67  478.55 1440.66  512.72 1443.61  520.65 1445.95   537.7 1447.16
  556.06 1452.16   581.4  1462.9  622.98 1482.58  664.75 1499.46  694.43 1507.71
  724.12 1514.37   739.9 1513.98  761.59 1515.94  832.83 1514.67  855.81 1515.61
#Mann= 3 , 0 , 0
       0     .12       0  442.71     .05       0  465.74     .12       0
Bank Sta=442.71,465.74
Exp/Cntr=0.3,0.1

Type RM Length L Ch R = 1 ,12099.53,198.94,200,197.76
XS GIS Cut Line= 3
  1065627.937012   695616.561115  1065921.770285   695336.186705
  1066281.310559   695102.975033
#Sta/Elev= 30
       0 1501.51   33.16 1493.41   38.91 1491.39   60.33 1488.02   65.51 1486.18
  110.34 1479.94   170.5 1469.74  197.18 1464.11  293.06 1447.82   332.8 1439.85
  359.04  1434.4  392.48 1421.74  406.14  1416.7  417.59 1421.48  442.89 1420.85
  454.96 1423.14  484.71 1424.73  496.06  1431.7   517.5 1441.29  539.85 1449.03
  560.47 1453.26  606.46 1467.17  639.06 1476.14  656.36 1482.87  689.58 1490.72
  722.28  1501.6  746.35 1507.84  782.68 1519.99  814.85 1532.94  834.69 1538.72
#Mann= 3 , 0 , 0
       0     .12       0  392.48     .05       0  417.59     .12       0
Bank Sta=392.48,417.59
Exp/Cntr=0.3,0.1

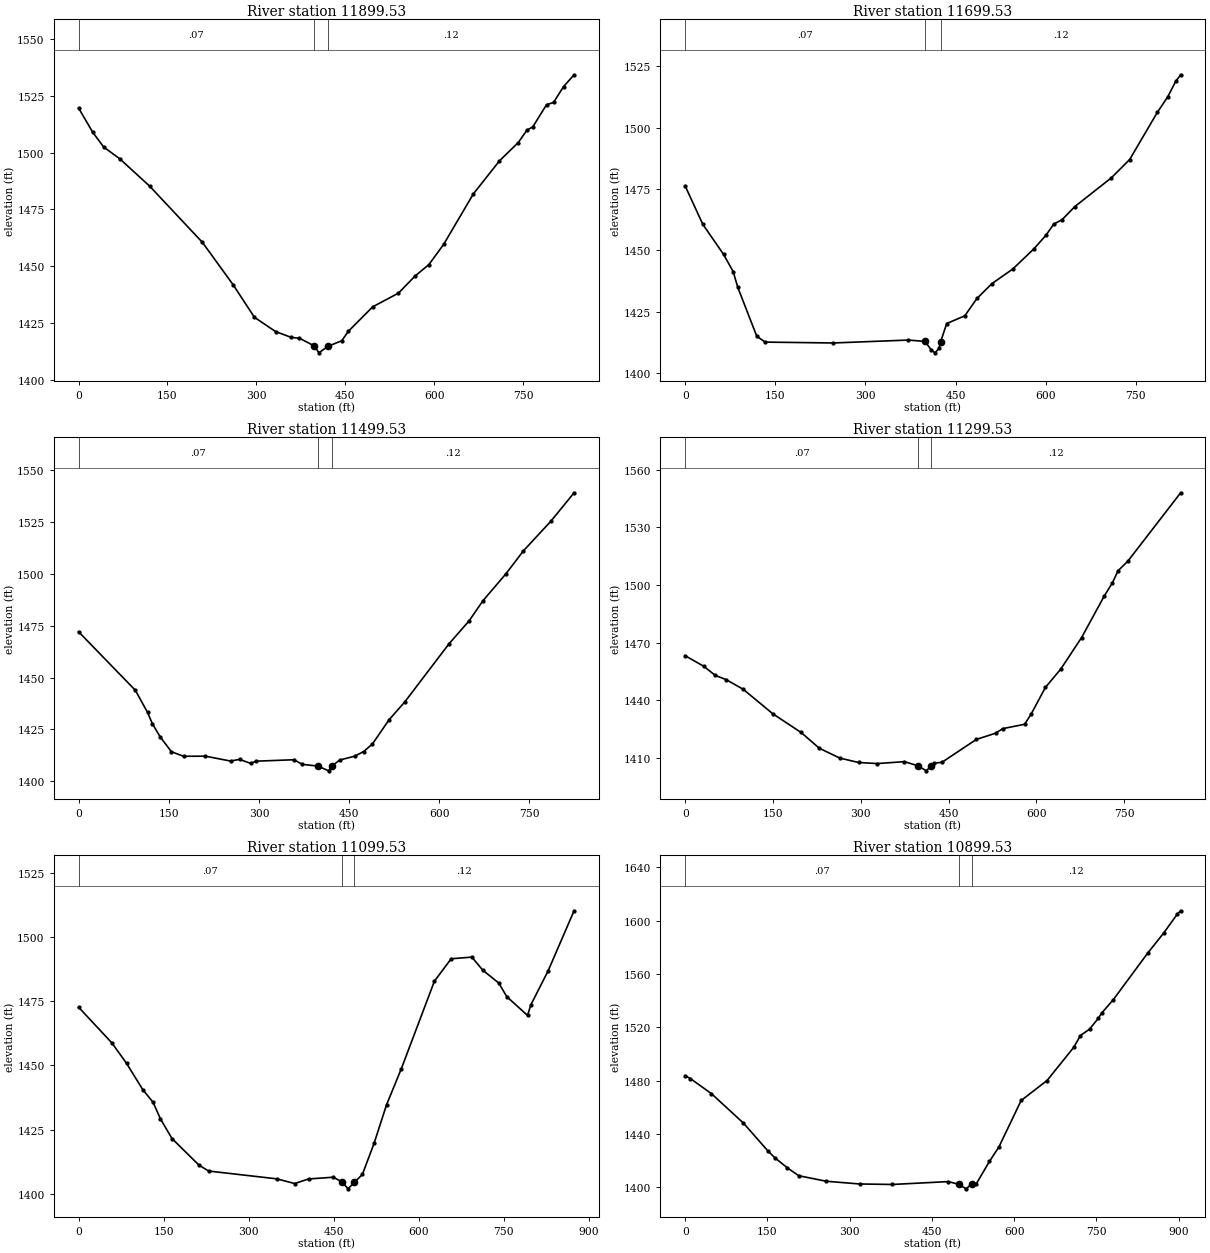
Type RM Length L Ch R = 1 ,11899.53,203.67,200,197.52
XS GIS Cut Line= 3
  1065719.406401   695721.817766  1066049.092083    695485.56833
  1066328.326187   695157.700685
#Sta/Elev= 30
       0  1519.6   23.55 1509.04   42.34 1502.44    69.4 1497.28  119.86 1485.24
  208.84 1460.52  260.58 1441.91  296.74 1427.51  332.39 1421.24  358.83 1418.67
  372.79 1418.28   397.7 1414.94  405.59 1411.87  420.69 1414.74  444.17 1417.19
  455.14 1421.31  496.33 1432.12  539.67 1438.12  567.63 1445.61  591.32 1450.74
  616.11 1459.61  666.34 1481.85  710.38 1496.38  742.11 1504.44  756.74 1509.89
  766.57 1511.32  789.72 1521.06  801.55 1522.06  818.51 1529.04  836.25 1534.25
#Mann= 3 , 0 , 0
       0     .07       0   397.7     .05       0  420.69     .12       0
Bank Sta=397.7,420.69
Exp/Cntr=0.3,0.1

Type RM Length L Ch R = 1 ,11699.53,199.34,200,200.29
XS GIS Cut Line= 3
    1066042.1902     695937.2485  1066226.078639    695564.31387
  1066378.583817   695185.182233
#Sta/Elev= 30
       0 1476.18   29.36 1460.55   63.92 1448.29   79.79 1441.32   87.53 1434.87
  119.09 1414.95  133.02 1412.56  246.09  1412.2  370.94 1413.39  399.26 1412.84
  409.44 1409.35  415.81 1408.18  422.23    1410  425.21 1412.79  435.15 1420.13
  465.28 1423.27  485.44 1430.35   510.6 1436.43  545.14 1442.36  580.27 1450.58
  600.06 1456.04  613.29 1460.64  627.36 1462.52  648.42 1467.82  709.18 1479.54
  739.61 1486.99  785.58 1506.19  803.06 1512.58  816.09 1518.81  824.46 1521.55
#Mann= 3 , 0 , 0
       0     .07       0  399.26     .05       0  425.21     .12       0
Bank Sta=399.26,425.21
Exp/Cntr=0.3,0.1

Type RM Length L Ch R = 1 ,11499.53,199.87,200,199.23
XS GIS Cut Line= 3
  1066186.018333   696012.413541  1066401.158379   695656.466426
  1066569.775666   695284.535128
#Sta/Elev= 30
       0 1472.13   94.36 1443.89  114.64 1433.24  122.56 1427.84  135.55 1421.46
  154.34 1414.24  174.74 1412.02  210.93 1412.09  252.68 1409.72  267.65 1410.54
  286.13  1408.6  295.01 1409.66  358.21 1410.36  372.14 1408.12  397.97 1407.31
  415.91    1405  420.75  1407.2   434.5 1410.23  459.29 1412.07   474.2 1414.32
  488.78 1417.96  516.47 1429.65  542.29 1438.15  616.36 1466.38  649.56 1477.37
  672.86 1487.19   710.8 1500.08  739.75 1511.11  785.79 1525.55  824.28 1539.24
#Mann= 3 , 0 , 0
       0     .07       0  397.97     .05       0  420.75     .12       0
Bank Sta=397.97,420.75
Exp/Cntr=0.3,0.1

Type RM Length L Ch R = 1 ,11299.53,198.02,200,201.56
XS GIS Cut Line= 3
  1066357.396794   696129.355212   1066558.87797   695769.628408
  1066697.294636   695357.869666
#Sta/Elev= 30
       0 1463.14   31.51 1457.69   51.62 1452.87   69.86 1450.74   99.32 1445.65
  149.56 1432.99  198.03 1423.22  229.36    1415  264.17 1409.91  296.19 1407.62
  327.75 1407.05  374.74 1408.05  397.36 1405.92  412.31 1403.27   419.7 1405.81
  425.97 1407.29  438.72 1407.69  497.61 1419.62  530.46 1422.84  542.57 1425.22
  579.91 1427.47  590.93 1432.65  615.59 1446.65  641.95 1456.26  677.41 1472.57
  715.93 1494.08  730.02 1501.03  739.84 1507.38   756.3 1512.26  846.71  1547.9
#Mann= 3 , 0 , 0
       0     .07       0  397.36     .05       0   419.7     .12       0
Bank Sta=397.36,419.7
Exp/Cntr=0.3,0.1

Type RM Length L Ch R = 1 ,11099.53,197.83,200,203.96
XS GIS Cut Line= 3
  1066401.624024   696155.641034  1066739.642197    695819.85229
  1066946.988914   695480.499863
#Sta/Elev= 30
       0 1472.72   58.65  1458.8    84.6 1450.81  113.25 1440.54  131.25 1435.66
   144.4 1429.15  164.69 1421.49  212.34  1411.1   229.3  1408.8  349.23 1405.76
  381.29 1403.92   405.6  1405.7     449 1406.38  464.92 1404.56  475.32 1401.85
  486.63  1404.4  500.66 1407.47  521.29 1419.62  543.31 1434.67  569.45 1448.78
  627.79 1482.92  657.27 1491.64  693.82 1492.29  713.09 1487.18  741.38 1482.15
  755.31 1476.88  792.01 1469.53  798.07 1473.74  828.09  1486.8  874.14 1510.37
#Mann= 3 , 0 , 0
       0     .07       0  464.92     .05       0  486.63     .12       0
Bank Sta=464.92,486.63
Exp/Cntr=0.3,0.1

Type RM Length L Ch R = 1 ,10899.53,198.38,200,200.41
XS GIS Cut Line= 3
  1066438.652353   696194.860887  1066888.226826   695949.345145
  1067232.833124    695764.09414
#Sta/Elev= 30
       0 1483.66    9.51 1481.47   47.76  1470.2  106.22 1448.11   151.5 1426.92
  164.01 1421.92  186.48 1414.48  207.12 1408.64  256.97 1404.51  318.33 1402.45
  377.88 1402.09  480.09 1404.25  499.28 1402.13  512.25 1398.81  522.42 1402.47
  531.02 1402.73  554.88 1419.41  572.12 1430.26  612.65 1465.05  659.88 1480.04
  708.76 1505.03  720.74 1513.76  737.32 1518.54  753.36 1526.67  759.25 1530.46
  780.55 1540.58  843.61 1575.66  872.46 1590.57  897.63 1604.93  903.49  1607.3
#Mann= 3 , 0 , 0
       0     .07       0  499.28     .05       0  522.42     .12       0
Bank Sta=499.28,522.42
Exp/Cntr=0.3,0.1

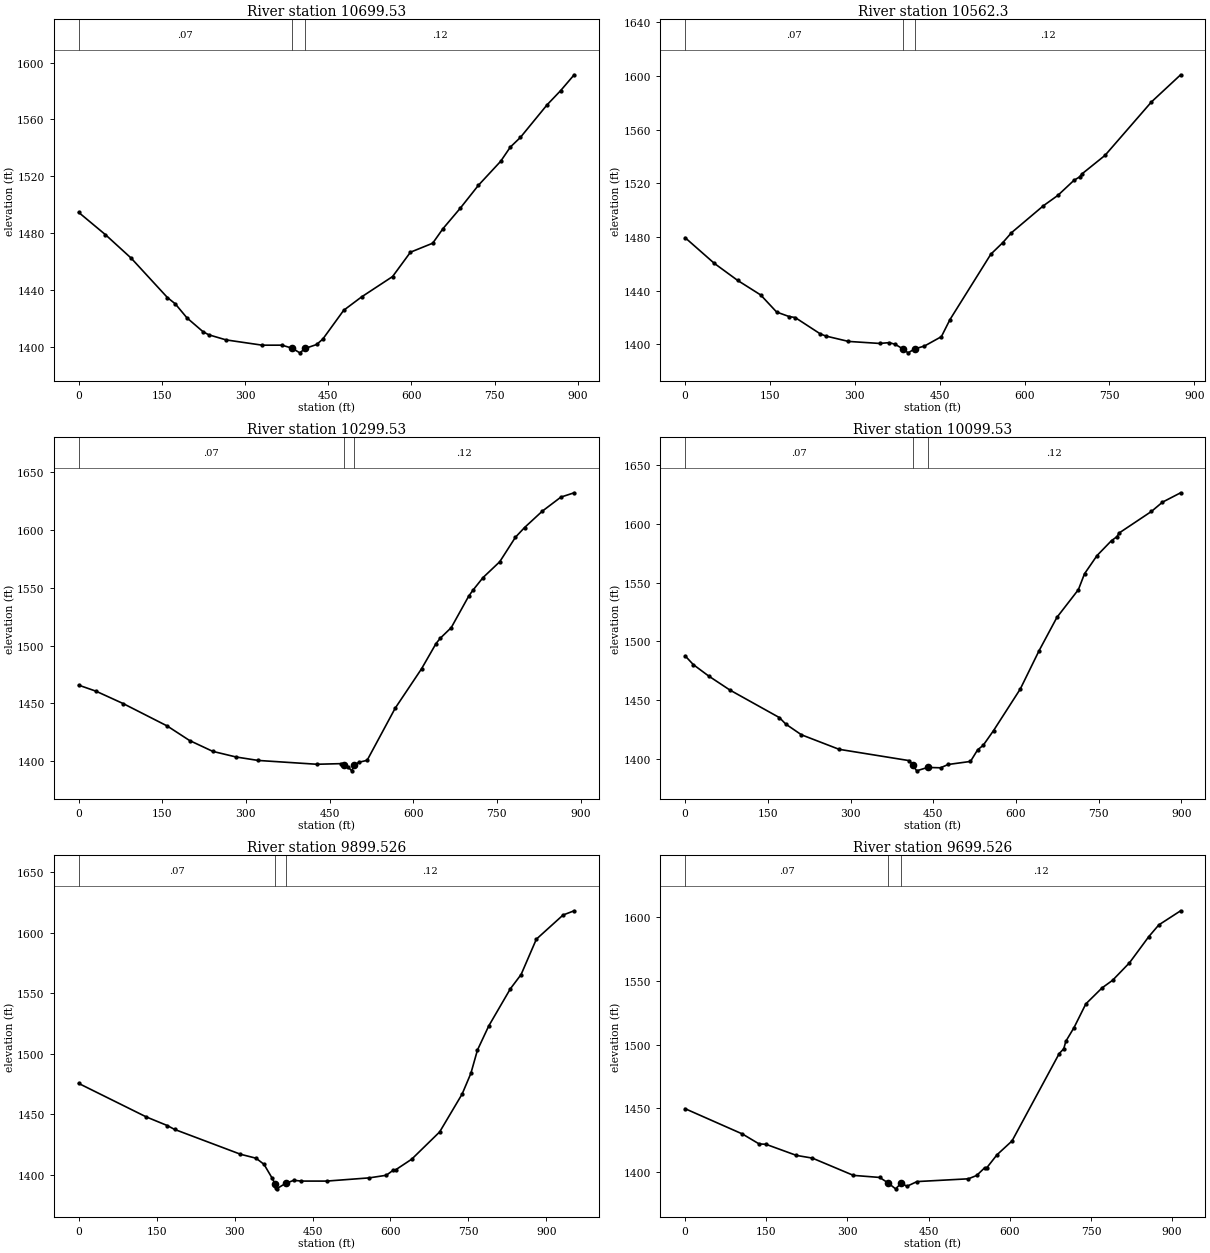
Type RM Length L Ch R = 1 ,10699.53,138.38,137.22,136.14
XS GIS Cut Line= 3
  1066452.813451   696234.946086  1066836.313688   696125.136674
   1067297.29166   695945.765889
#Sta/Elev= 30
       0 1494.74   48.37 1479.04    94.8 1462.54  160.11 1434.88   174.2 1430.48
  195.46 1420.55  224.49 1410.82  234.67 1408.71  265.88 1405.12  331.09 1401.41
  366.67 1401.42  384.66 1399.33  398.89 1396.03   408.6 1399.14  429.22 1401.89
  440.38 1405.74  477.95 1425.92  510.27 1435.34  566.13 1449.64   598.3 1466.73
  638.46 1473.06     657 1483.29  688.07  1497.6  721.04 1513.82  760.94 1530.58
  778.44  1540.6  796.51 1547.35  844.76 1570.31  868.93 1580.18  893.56  1591.4
#Mann= 3 , 0 , 0
       0     .07       0  384.66     .05       0   408.6     .12       0
Bank Sta=384.66,408.6
Exp/Cntr=0.3,0.1

Type RM Length L Ch R = 1 ,10562.3 ,263.23,262.77,262.45
XS GIS Cut Line= 3
  1066552.753121   696396.722735  1066909.649546   696234.497102
  1067327.762038   695990.749143
#Sta/Elev= 30
       0  1479.6    51.8  1460.4   92.89 1447.75  133.63  1436.9  161.83 1424.17
   183.7 1420.85  194.56 1420.09  238.66 1407.99  248.49 1406.33  288.77 1402.29
  343.89 1400.78  360.76 1401.38  371.18 1400.17  384.43 1396.87  394.28 1393.78
  405.67 1396.67  423.21 1398.86  453.04 1405.83   468.3 1418.61  540.51 1467.29
  561.75 1475.96  576.94 1483.27  633.47  1503.4  658.85 1511.05  687.41 1522.31
  697.32 1524.85  701.57  1527.1  742.38 1540.93  824.49 1580.77  876.01 1600.96
#Mann= 3 , 0 , 0
       0     .07       0  384.43     .05       0  405.67     .12       0
Bank Sta=384.43,405.67
Exp/Cntr=0.3,0.1

Type RM Length L Ch R = 1 ,10299.53,199.43,200,188.38
XS GIS Cut Line= 3
  1066705.245211   696607.616087  1067126.196004   696357.647043
  1067464.952219   696146.724137
#Sta/Elev= 30
       0 1465.78   31.23 1460.53   80.03  1449.8  158.83 1430.47  198.95 1417.89
  240.51 1408.51  282.26 1403.65  321.95 1400.66  427.07 1397.36  470.79 1397.89
  476.29 1396.68   483.5 1394.89  489.58 1391.67  494.49 1396.39  502.34 1399.04
  517.34 1400.76  567.69 1445.86  614.89 1479.88  640.94 1501.76  648.39 1506.29
  668.19 1515.52  699.19 1542.47   706.8 1547.69  725.17 1558.78  755.17 1572.48
  783.35  1593.7  799.58 1602.02  831.44 1616.21  864.86 1628.38  888.63 1632.12
#Mann= 3 , 0 , 0
       0     .07       0  476.29     .05       0  494.49     .12       0
Bank Sta=476.29,494.49
Exp/Cntr=0.3,0.1

Type RM Length L Ch R = 1 ,10099.53,204.07,200,207.6
XS GIS Cut Line= 3
  1066775.844325   696682.831381  1067172.403956   696545.057416
  1067494.052147   696190.617959
#Sta/Elev= 30
       0 1487.71      15 1480.21   42.83 1470.53   81.22 1458.65  170.93 1435.24
  182.65 1429.69  210.81 1420.65  279.15 1408.29  406.29 1398.68  413.28 1394.74
  419.81    1390  439.64 1392.89  463.17 1392.59  476.93  1395.4  517.41 1397.99
   530.5 1407.94  540.31 1411.58  559.22 1424.19  607.72 1459.54  641.72 1492.03
  674.09 1520.36  713.06 1543.93  724.15 1557.42  746.84 1572.89   773.1  1585.6
  783.26    1589  786.38  1591.9   845.5 1610.38  865.53 1618.27  898.44 1626.24
#Mann= 3 , 0 , 0
       0     .07       0  413.28     .05       0  439.64     .12       0
Bank Sta=413.28,439.64
Exp/Cntr=0.3,0.1

Type RM Length L Ch R = 1 ,9899.526,204.63,200,198.18
XS GIS Cut Line= 3
  1067039.039874   697047.388548   1067234.62984   696720.773602
  1067521.201996   696224.931447
#Sta/Elev= 30
       0 1475.59  130.44 1447.83  170.36 1440.79  184.55 1437.57  311.42 1417.03
  341.42 1413.74  356.65 1408.69   372.4 1397.21  377.93 1392.46  379.97 1389.02
   380.7 1388.44  398.13 1392.91  414.04  1395.5  428.08 1394.86  477.04 1394.84
   559.5 1397.52  591.84 1399.65   604.8 1403.69  610.33 1404.28   640.8 1412.94
  694.62 1435.49  737.83 1466.78  754.65 1483.88  767.33 1503.16  789.04 1523.07
  830.61 1553.77  851.28 1565.56  880.62 1594.78  932.08 1614.77   953.4 1618.26
#Mann= 3 , 0 , 0
       0     .07       0  377.93     .05       0  398.13     .12       0
Bank Sta=377.93,398.13
Exp/Cntr=0.3,0.1

Type RM Length L Ch R = 1 ,9699.526,202.47,200,198.26
XS GIS Cut Line= 3
  1067459.270723   697131.877683  1067428.469499    696744.17549
  1067570.516607   696236.985217
#Sta/Elev= 30
       0 1449.75  105.71 1429.97  136.71 1422.16   149.4 1421.85  205.65 1413.16
  235.18 1411.03  311.05  1397.5   359.5 1395.89   374.5 1391.75  388.92 1386.96
  399.46 1391.42  409.87 1388.96  428.53 1392.65  523.43 1394.82  538.67 1397.42
  553.44 1403.41  557.62 1403.56  576.32 1413.64  604.11 1424.49  691.24 1492.92
  699.64 1496.68  703.53 1502.57  718.64 1513.27  740.45 1531.82  770.46 1544.38
  789.81  1550.3  821.08 1564.02  856.77 1584.52  875.35 1593.73  915.63 1604.78
#Mann= 3 , 0 , 0
       0     .07       0   374.5     .05       0  399.46     .12       0
Bank Sta=374.5,399.46
Exp/Cntr=0.3,0.1