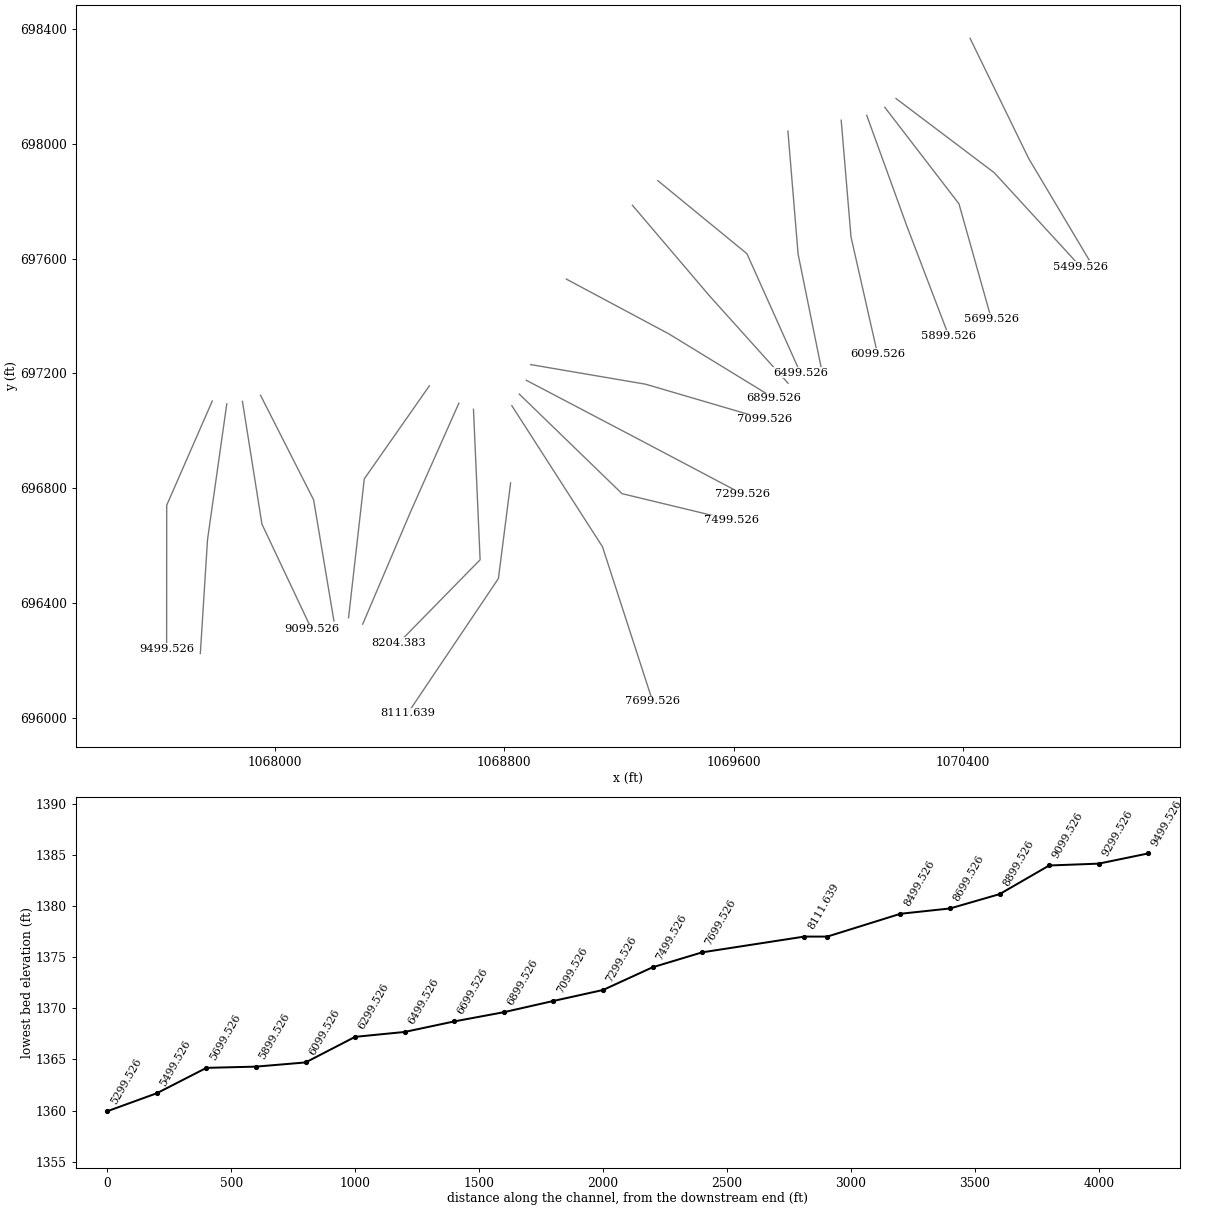
HEC-RAS study BrevardCreek.prj: Brevard Creek

--- BrevardCreek.g02 (geometry) --- (continued)

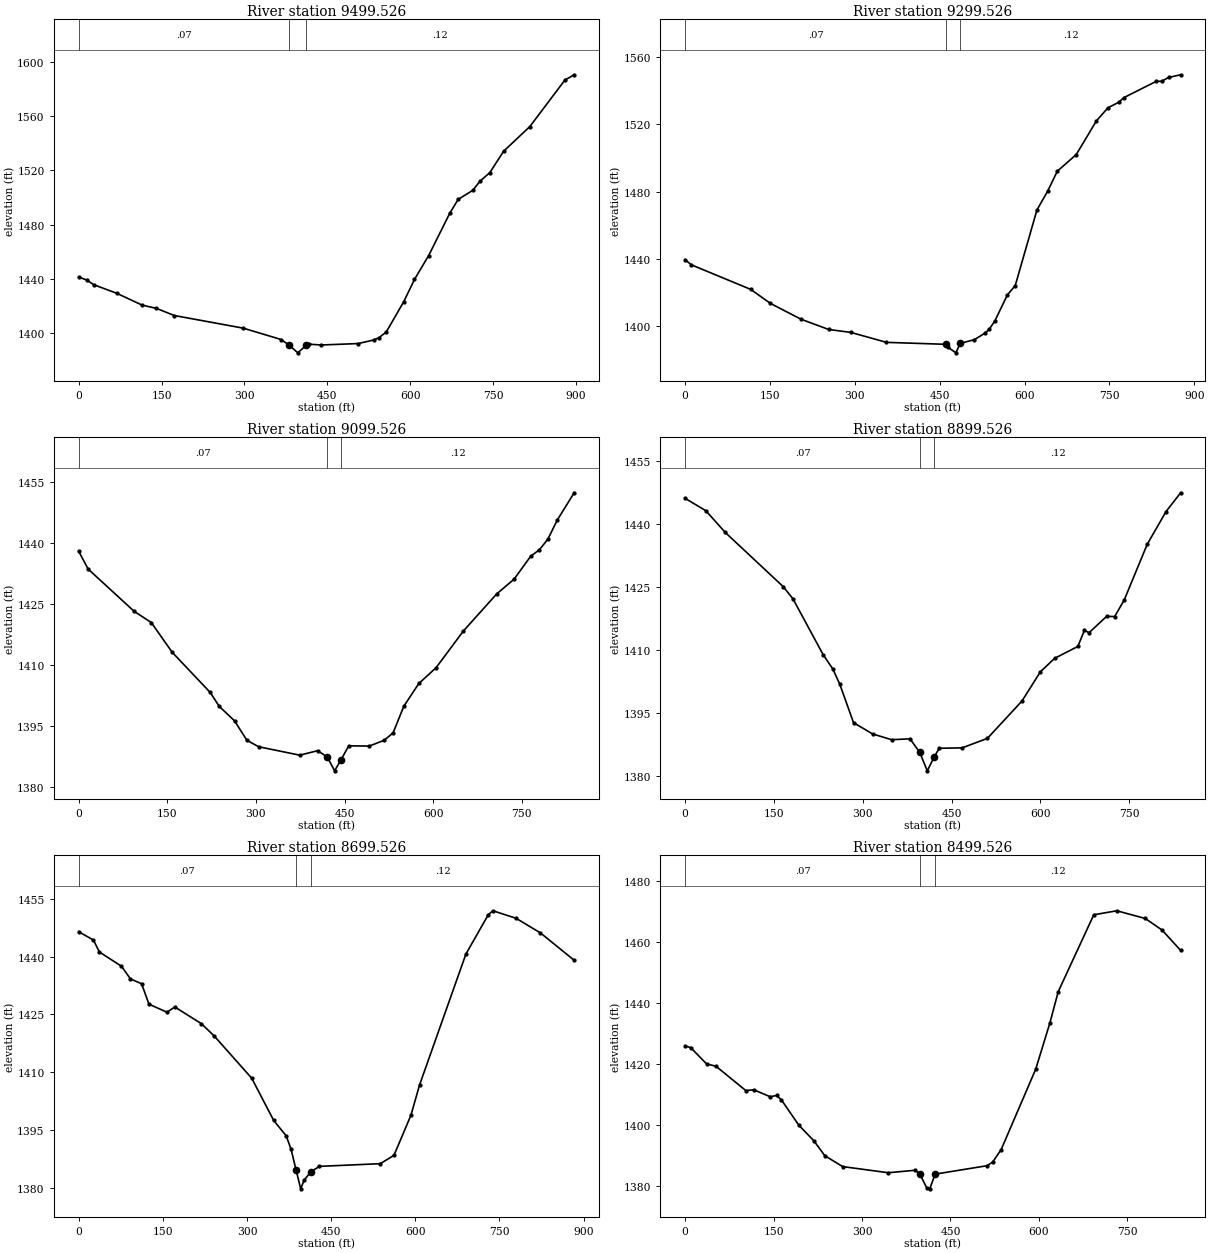
Type RM Length L Ch R = 1 ,9499.526,197.87,200,198.82
XS GIS Cut Line= 3
  1067782.765378   697103.773941  1067623.899266   696740.330245
  1067623.561275   696240.212773
#Sta/Elev= 30
       0 1441.19   14.83 1438.97    27.4 1435.51   68.56 1429.24  115.22 1420.39
  140.85 1418.01  173.09 1412.74  297.89 1403.39  366.37 1394.99  381.05 1390.81
  396.65 1385.13  412.28 1390.87  416.56 1391.54   439.2 1390.94  505.78 1391.99
   533.8  1394.6  543.39 1396.33  556.62 1400.49  588.22 1422.84  607.74 1439.39
  633.33    1457  671.72 1488.45  686.86 1498.63  713.39 1505.36  726.02 1511.91
  744.26 1518.51  769.17 1534.27  816.58 1552.51  880.03 1586.91  896.77  1590.8
#Mann= 3 , 0 , 0
       0     .07       0  381.05     .05       0  412.28     .12       0
Bank Sta=381.05,412.28
Exp/Cntr=0.3,0.1

Type RM Length L Ch R = 1 ,9299.526,197.81,200,203.78
XS GIS Cut Line= 3
  1067833.357039   697094.001872  1067766.098028    696620.05115
  1067741.078809   696223.551365
#Sta/Elev= 30
       0 1439.47   11.19 1436.44  115.81 1421.89  150.83 1413.53   205.1 1404.09
  253.72 1398.03  292.97 1396.28  356.01 1390.36  461.22  1389.2  465.11 1387.38
   478.7 1384.13  486.44 1389.78  511.51 1391.96  529.93 1395.82   537.4 1398.05
  547.56 1403.08  569.77 1418.59  583.59 1424.11  621.99  1469.1  640.96 1480.31
  657.98 1492.13  691.51 1502.05  727.13 1522.06  747.44 1529.82  766.72 1533.15
  775.42 1535.84  833.14 1545.61  842.39  1545.6  854.94 1547.91  875.99 1549.47
#Mann= 3 , 0 , 0
       0     .07       0  461.22     .05       0  486.44     .12       0
Bank Sta=461.22,486.44
Exp/Cntr=0.3,0.1

Type RM Length L Ch R = 1 ,9099.526,197.59,200,197.86
XS GIS Cut Line= 3
  1067887.906219   697102.381277  1067955.839153   696674.481104
  1068129.006407   696308.029121
#Sta/Elev= 30
       0 1437.93   16.12 1433.53   93.81 1423.16  122.91  1420.4  158.37 1413.08
  222.65 1403.22  237.96 1399.79  263.89 1396.23  284.58 1391.48  304.38 1389.88
  374.14  1387.8  404.56  1388.9  420.81 1387.33   433.2 1383.95  444.31 1386.73
  457.08 1390.09  491.89 1390.04  517.03 1391.46  532.18 1393.28  550.31 1399.84
  575.76 1405.42  604.85 1409.29  650.75 1418.25  707.48 1427.43  736.86 1431.05
  764.99 1436.68  779.58 1438.26  793.96 1440.85  810.03 1445.59  838.57 1452.28
#Mann= 3 , 0 , 0
       0     .07       0  420.81     .05       0  444.31     .12       0
Bank Sta=420.81,444.31
Exp/Cntr=0.3,0.1

Type RM Length L Ch R = 1 ,8899.526,208.1,200,198.06
XS GIS Cut Line= 3
  1067950.879777   697123.802948  1068136.003438   696759.068533
   1068206.82085   696336.968967
#Sta/Elev= 30
       0 1446.13   35.06 1443.18   67.93 1437.99  165.77 1425.07  182.23 1422.16
  233.06 1408.88  249.63 1405.42  261.34 1401.79  284.49 1392.63  316.85 1389.94
  348.71 1388.58  379.92 1388.78  396.42 1385.54  409.02 1381.15  421.09 1384.55
  429.24 1386.53  467.97 1386.63  510.69  1388.9  569.07 1397.81  600.25 1404.79
  624.28 1407.99  663.36 1410.81  674.43 1414.63  682.47 1414.11  712.07    1418
  725.56 1417.94  741.65 1421.86  780.58 1435.18  812.37 1442.98  837.02 1447.46
#Mann= 3 , 0 , 0
       0     .07       0  396.42     .05       0  421.09     .12       0
Bank Sta=396.42,421.09
Exp/Cntr=0.3,0.1

Type RM Length L Ch R = 1 ,8699.526,198.46,200,197.55
XS GIS Cut Line= 3
  1068539.552529   697156.642332  1068312.710685   696832.338836
  1068257.814969    696348.10935
#Sta/Elev= 30
       0 1446.47   26.41 1444.31   36.91 1441.21   76.26 1437.52   92.39 1434.22
   112.2 1432.96  125.38 1427.66  157.46 1425.58  171.45 1426.94  218.68 1422.61
   241.4 1419.45  308.48 1408.45  347.65 1397.49  369.89 1393.51   378.7 1389.97
  387.67 1384.53  395.76 1379.75  401.65 1381.95  413.65 1384.15   429.1 1385.58
  537.71 1386.28  561.97 1388.45  592.19 1398.85  607.54  1406.7  690.16 1440.67
  730.19 1450.91  738.36  1451.9  779.44 1449.96  822.98 1446.16   883.1 1439.06
#Mann= 3 , 0 , 0
       0     .07       0  387.67     .05       0  413.65     .12       0
Bank Sta=387.67,413.65
Exp/Cntr=0.3,0.1

Type RM Length L Ch R = 1 ,8499.526,290.45,295.14,293.03
XS GIS Cut Line= 3
  1068642.446776   697096.294836  1068473.889762   696717.140247
  1068307.097307   696325.745785
#Sta/Elev= 30
       0 1426.04    9.59 1425.48   36.32 1420.17   52.46 1419.38  102.93 1411.43
  116.67 1411.68  144.29  1409.4  155.03 1409.82  163.32 1408.38  192.82 1400.09
  218.47 1394.95  236.91 1390.09  267.17 1386.52  344.51 1384.51   390.5 1385.32
  398.39    1384  409.57  1379.6  414.93 1379.23  424.09 1384.05  512.32 1386.81
  521.76 1388.05  535.96 1392.06  594.56 1418.41  618.53 1433.49  632.85 1443.85
  693.11 1469.01  732.17 1470.32  780.33  1467.8  808.78 1464.03  840.39 1457.34
#Mann= 3 , 0 , 0
       0     .07       0  398.39     .05       0  424.09     .12       0
Bank Sta=398.39,424.09
Exp/Cntr=0.5,0.3

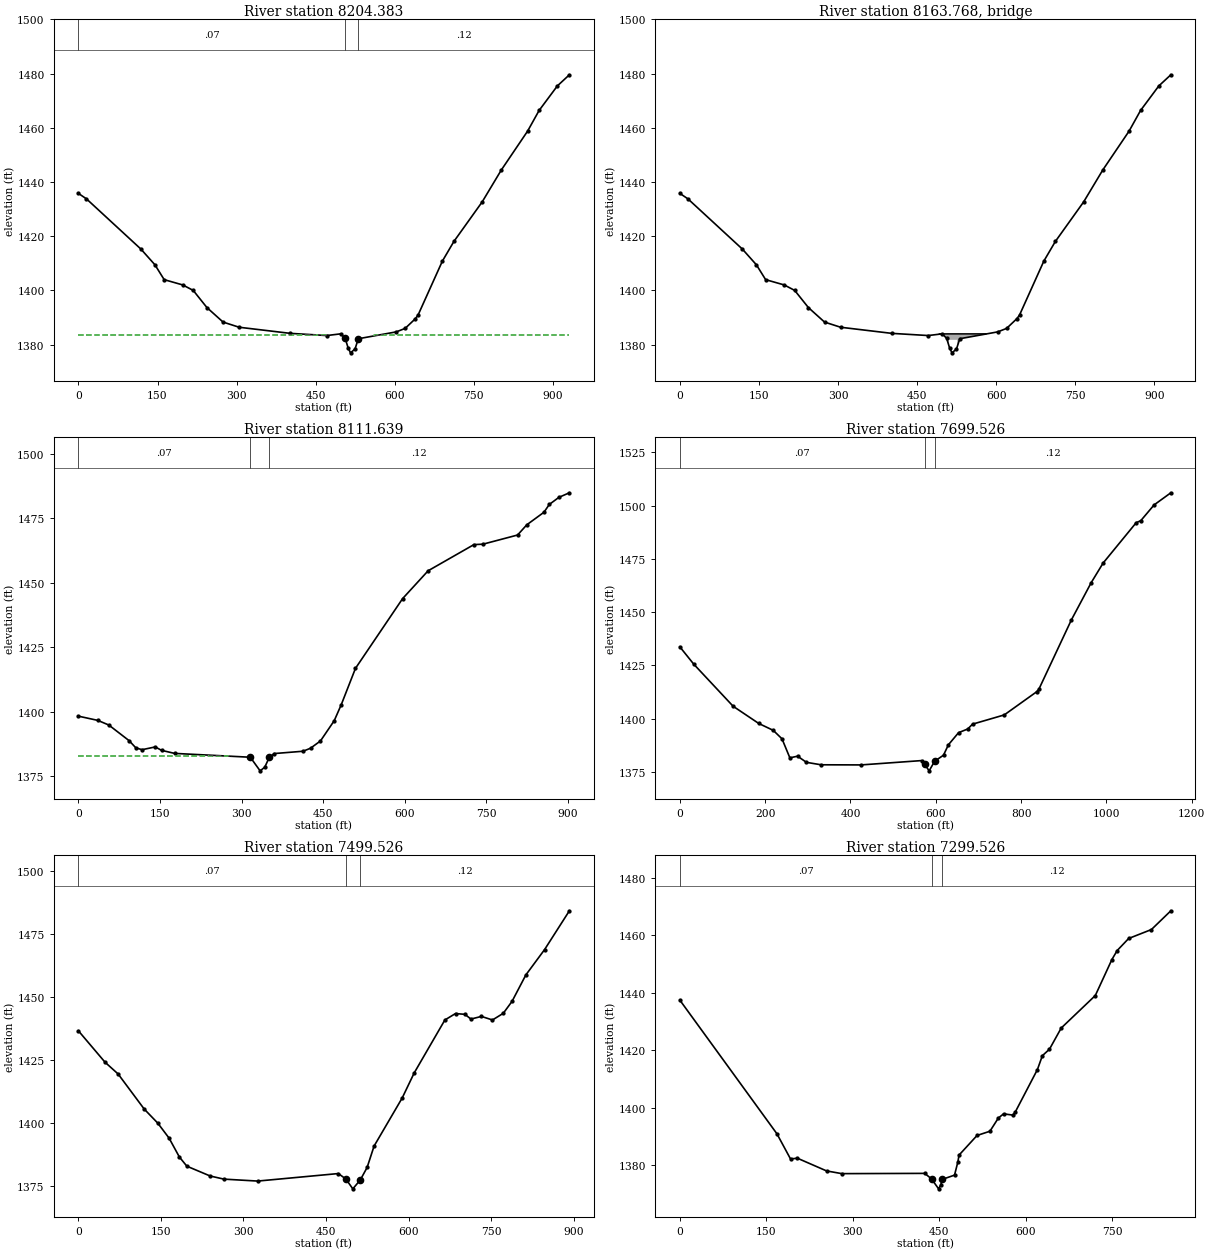
Type RM Length L Ch R = 1 ,8204.383,95.31,92.75,93.34
XS GIS Cut Line= 3
   1068693.30093   697074.820464   1068716.41912   696550.209924
  1068432.304671   696260.242829
#Sta/Elev= 30
       0 1435.82   15.19 1433.82  118.51 1415.28  145.12 1409.48  162.66    1404
  197.87 1402.05  217.75 1400.03  243.72  1393.7  274.34 1388.35  304.84 1386.44
  401.58 1384.19  470.98 1383.38  497.54 1384.01   505.9 1382.34   511.5  1378.8
     516    1377   524.5  1378.4  530.85  1382.2  602.72 1384.73  619.55 1386.01
  639.08  1389.6  644.09 1390.93   690.2 1410.84  712.02 1418.08  765.75  1432.7
  802.04 1444.47  851.88 1458.81  873.61 1466.41  908.25 1475.47  931.08 1479.58
#Mann= 3 , 0 , 0
       0     .07       0   505.9     .05       0  530.85     .12       0
#XS Ineff= 2 , 0
       0     476  1383.5     560       0  1383.5
Permanent Ineff=
       F       F
Bank Sta=505.9,530.85
Exp/Cntr=0.5,0.3

Type RM Length L Ch R = 3 ,8163.768,,,
BEGIN DESCRIPTION:
37111-0201  Souther Road
END DESCRIPTION:
Bridge Culvert--1,0,-1,-1, 0
Deck Dist Width WeirC Skew NumUp NumDn MinLoCord MaxHiCord MaxSubmerge Is_Ogee
34,13,2.6,0, 6, 6, , , 0.95, 0, 0,0,,
  492.32     510     510     526     526  580.15
 1383.98    1384    1384    1384    1384    1384
                  1381.8  1381.8
  286.44     328     328     344     344     375
 1383.27    1384    1384    1384    1384    1384
                  1381.8  1381.8
BR Coef=-1 , 1 , 0 ,, 0 ,,,0.8,0,1.2,0,
WSPro=,,,, 1 ,,,, 0 ,,,, 0 ,,,,-1 ,-1 ,-1 , 0 , 0 , 0 , 0 , 0
BC Design=,, 0 ,, 0 ,,,,,,

Type RM Length L Ch R = 1 ,8111.639,407.06,412.11,417.68
XS GIS Cut Line= 3
   1068822.73223   696818.076376  1068780.210605   696484.782777
  1068463.977378   696014.729612
#Sta/Elev= 30
       0 1398.23   35.75 1396.58   55.87 1394.79   93.12 1388.73  105.62 1385.92
  117.01 1385.21  141.29 1386.28  152.77 1384.96  176.84 1383.77     316 1382.28
     334    1377   342.5  1378.4  350.78 1382.19  359.98 1383.71  412.99 1384.61
  426.66 1385.78  444.97 1388.61  470.27 1396.48  483.26 1402.73   509.3 1416.79
  595.93 1443.86  642.83 1454.67  727.02 1464.83  743.55 1464.99  807.25 1468.55
  824.24 1472.52  855.76 1477.39  865.65 1480.43  883.26 1483.18  902.52 1484.95
#Mann= 3 , 0 , 0
       0     .07       0     316     .05       0  350.78     .12       0
#XS Ineff= 2 , 0
       0     283  1382.9     389       0  1383.9
Permanent Ineff=
       F       F
Bank Sta=316,350.78
Exp/Cntr=0.5,0.3

Type RM Length L Ch R = 1 ,7699.526,198.46,200,208.82
XS GIS Cut Line= 3
  1068827.141065   697087.226012  1069143.024146    696595.52181
  1069317.945977   696056.547681
#Sta/Elev= 30
       0 1433.65   32.67 1425.51   124.9 1405.77  185.02 1397.69  218.88 1394.47
  239.42  1390.5  257.88 1381.56  275.95 1382.34   296.7 1379.45  331.04  1378.3
  424.96 1378.24  566.51 1380.27  573.97 1378.46  584.43 1375.46  597.14 1379.93
  618.07 1382.81  629.55 1387.69  653.39 1393.38   674.9 1395.11  686.09 1397.37
  760.52 1401.71   836.7 1412.61  841.59 1413.75  917.75 1446.27   964.5 1463.86
   992.3 1473.01  1069.8 1491.95 1080.59  1492.9 1111.83  1500.3 1151.08 1505.99
#Mann= 3 , 0 , 0
       0     .07       0  573.97     .05       0  597.14     .12       0
Bank Sta=573.97,597.14
Exp/Cntr=0.3,0.1

Type RM Length L Ch R = 1 ,7499.526,197.35,200,198.11
XS GIS Cut Line= 3
  1068852.936231   697127.774022  1069211.137629    696780.68322
   1069593.82623   696688.474391
#Sta/Elev= 30
       0 1436.65    48.4  1424.2   72.12 1419.55   119.6 1405.63  144.24 1400.06
  164.83  1394.1  183.53 1386.62  197.14 1382.98  239.47 1379.09  264.46 1377.85
   325.9 1377.08  472.44 1380.06  486.01 1377.92  498.78    1374  512.32 1377.51
  524.76 1382.47  537.42 1390.96  588.58 1410.05  610.27 1419.93   666.1 1440.95
  685.42  1443.5  702.55 1443.18  713.48 1441.31  732.52 1442.36  752.61 1440.95
  772.23 1443.59  788.18 1448.33   813.3 1458.81  847.36 1468.87  892.42 1484.24
#Mann= 3 , 0 , 0
       0     .07       0  486.01     .05       0  512.32     .12       0
Bank Sta=486.01,512.32
Exp/Cntr=0.3,0.1

Type RM Length L Ch R = 1 ,7299.526,197.66,200,201.38
XS GIS Cut Line= 3
  1068877.278381   697175.981803  1069274.861734   696967.282539
  1069631.314106   696779.063481
#Sta/Elev= 30
       0 1437.43   168.4 1390.95  192.02 1382.19  204.08 1382.43  254.53 1378.02
  281.09 1377.07  425.06 1377.16  436.76 1375.23  449.03 1371.78  452.78 1373.12
  455.36 1375.08  476.67 1376.55  482.55  1381.2  484.49 1383.52  515.77 1390.35
   538.1 1391.82  552.75 1396.42  561.76 1397.87  577.87 1397.44  582.03 1398.48
  620.52 1413.28  629.14 1418.11  641.47 1420.37  661.83 1427.73  721.03 1439.05
  749.77 1451.55  758.97  1454.7  778.88 1458.89  818.37    1462  852.12 1468.53
#Mann= 3 , 0 , 0
       0     .07       0  436.76     .05       0  455.36     .12       0
Bank Sta=436.76,455.36
Exp/Cntr=0.3,0.1

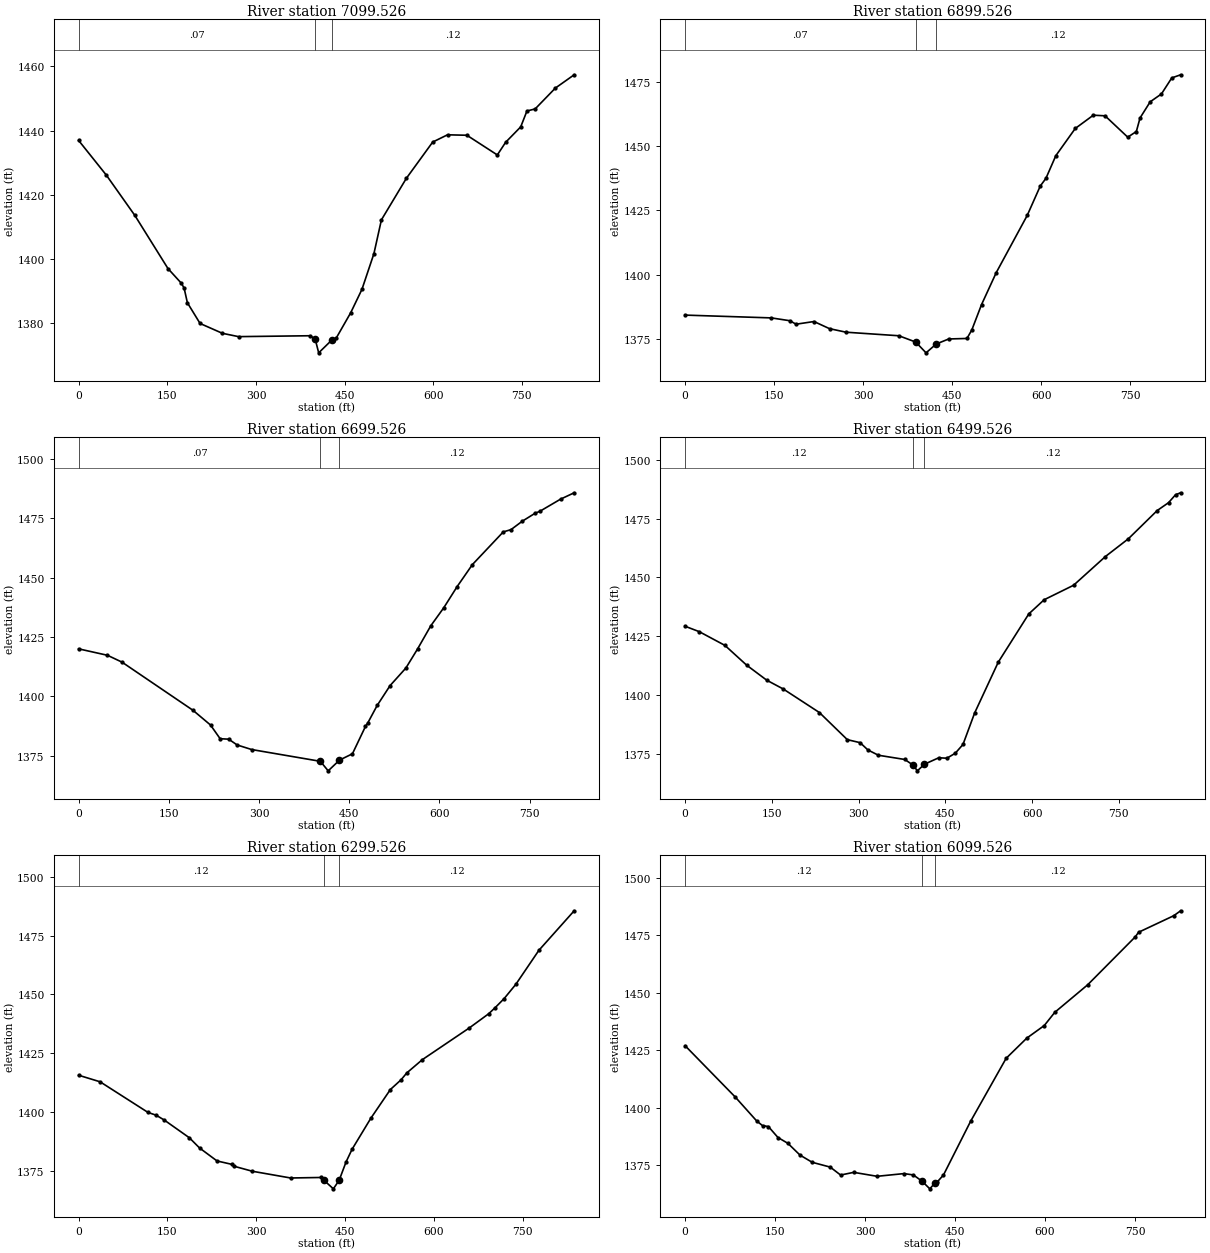
Type RM Length L Ch R = 1 ,7099.526,202.33,200,197.74
XS GIS Cut Line= 3
  1068892.706664   697230.621511  1069293.099501   697162.283788
   1069707.88688   697040.623563
#Sta/Elev= 30
       0 1436.91   46.88  1426.1   95.18 1413.52  151.24 1396.96  173.83  1392.4
  178.48 1390.89  184.01 1386.32   205.5 1379.86  243.21  1376.8  270.53 1375.76
  392.12 1376.04  400.37 1374.89  406.18 1370.71  428.67 1374.75  435.76 1375.29
  460.31  1383.2  479.35 1390.49  499.62 1401.63  512.29 1412.16  554.52 1425.11
  599.08 1436.41  624.17 1438.67  656.94 1438.53  708.41 1432.39  722.49 1436.34
  747.98 1441.14  758.52 1446.09  772.43 1446.74  806.66 1453.24  838.44 1457.38
#Mann= 3 , 0 , 0
       0     .07       0  400.37     .05       0  428.67     .12       0
Bank Sta=400.37,428.67
Exp/Cntr=0.3,0.1

Type RM Length L Ch R = 1 ,6899.526,202.78,200,197.81
XS GIS Cut Line= 3
  1069016.854849   697528.721052  1069374.770335   697337.411179
   1069740.53853   697113.598944
#Sta/Elev= 30
       0 1384.28  145.34 1383.19  176.54 1382.09  186.86 1380.74   217.1 1381.78
  243.23 1379.01  271.17 1377.63  360.06 1376.25  388.48  1373.8  405.84 1369.61
  422.97 1373.04  444.02    1375  474.75  1375.2   482.9 1378.49  499.28 1388.35
   524.1 1400.81  576.18    1423  598.23 1434.45  607.78 1437.45  624.39 1446.23
  657.16 1456.83   687.6 1461.99  707.33 1461.75  745.53 1453.45  760.03 1455.63
  766.26 1460.91   783.4  1467.2  802.29 1470.24  819.72 1476.48  834.65  1477.7
#Mann= 3 , 0 , 0
       0     .07       0  388.48     .05       0  422.97     .12       0
Bank Sta=388.48,422.97
Exp/Cntr=0.3,0.1

Type RM Length L Ch R = 1 ,6699.526,198.51,200,197.33
XS GIS Cut Line= 3
  1069247.338825   697785.972379  1069516.346865   697469.907351
  1069789.891861   697165.756283
#Sta/Elev= 30
       0 1420.04   47.96 1417.33   72.12 1414.45   190.2 1394.18  219.32 1387.99
  235.31 1382.23  249.62 1382.03  263.53  1379.6  287.77 1377.67  401.96 1372.72
  415.05 1368.71  433.82 1373.22  455.36 1375.89  477.03  1387.4  480.66 1388.76
  496.47 1396.22  518.04  1404.6  544.24 1411.97   563.6 1419.97  585.68 1429.75
  607.18 1437.31  629.55 1446.26  654.83 1455.49   706.2 1469.25  719.04  1470.2
  737.71 1473.73  759.53 1477.16  766.53 1477.84  801.41 1483.02  824.11 1485.71
#Mann= 3 , 0 , 0
       0     .07       0  401.96     .05       0  433.82     .12       0
Bank Sta=401.96,433.82
Exp/Cntr=0.3,0.1

Type RM Length L Ch R = 1 ,6499.526,205.98,200,198.11
XS GIS Cut Line= 3
  1069335.966845   697871.813322  1069646.545723   697617.201455
   1069832.83711   697201.953441
#Sta/Elev= 30
       0 1429.17   24.49 1426.87   68.88 1421.03  106.47 1412.61   141.1 1406.24
  169.89 1402.46  232.23 1392.47  280.49 1380.94   302.6 1379.66  316.06 1376.56
  334.24 1374.31  379.86 1372.51  394.04 1370.13   401.6 1367.68  413.78  1370.5
  438.58 1373.24  452.58 1373.05  467.08 1375.16  480.43 1378.89  500.62 1392.31
  541.45 1413.91  594.24 1434.43  620.73 1440.44  671.65 1446.61  726.69 1458.83
  766.33 1466.37   816.2 1478.38  835.85 1481.74  847.96 1485.12  856.73 1485.94
#Mann= 3 , 0 , 0
       0     .12       0  394.04     .05       0  413.78     .12       0
Bank Sta=394.04,413.78
Exp/Cntr=0.3,0.1

Type RM Length L Ch R = 1 ,6299.526,199.9,200,200.09
XS GIS Cut Line= 3
  1069789.424856   698044.594778  1069824.930924   697615.892599
  1069905.895212   697217.347703
#Sta/Elev= 30
       0 1415.58   36.22 1412.79  117.23 1399.73  130.79 1398.57  144.56 1396.51
   187.1 1388.93  204.22  1384.6  233.75 1379.07  258.78 1377.63  261.93 1376.86
  293.37 1374.69  358.07 1371.82  409.46 1372.04  414.58 1370.79  430.17  1367.2
  440.02 1370.87  451.63 1378.66  461.75 1384.04   493.4 1397.24   526.5  1409.5
  544.49 1413.63  554.16 1416.56  580.47 1422.22  659.74 1435.72  692.43 1441.75
  703.58  1444.4  718.65 1448.24  738.34  1454.3  777.24 1468.77  836.86 1485.62
#Mann= 3 , 0 , 0
       0     .12       0  414.58     .05       0  440.02     .12       0
Bank Sta=414.58,440.02
Exp/Cntr=0.3,0.1

Type RM Length L Ch R = 1 ,6099.526,198.01,200,201.06
XS GIS Cut Line= 3
  1069975.158634   698082.379518  1070009.329476   697675.841248
  1070101.755128   697268.026861
#Sta/Elev= 30
       0 1426.94   83.83 1404.56   119.4  1394.2  129.17 1392.18  138.81  1391.8
  154.82 1387.02  171.41 1384.48  191.61 1379.36  211.91 1376.24  241.98 1374.15
  259.23  1370.7  281.12 1371.87  320.12 1370.15  364.94 1371.33  380.51 1370.74
  395.12 1368.01  407.97  1364.7  417.05 1367.39  419.81 1367.53  430.71  1370.7
  475.91 1394.03  535.22 1421.46  569.66 1430.24  598.84 1435.72  616.35 1441.46
  671.14 1453.42  750.59  1474.3  755.92 1476.26  814.62 1483.46  826.13 1485.61
#Mann= 3 , 0 , 0
       0     .12       0  395.12     .05       0  417.05     .12       0
Bank Sta=395.12,417.05
Exp/Cntr=0.3,0.1

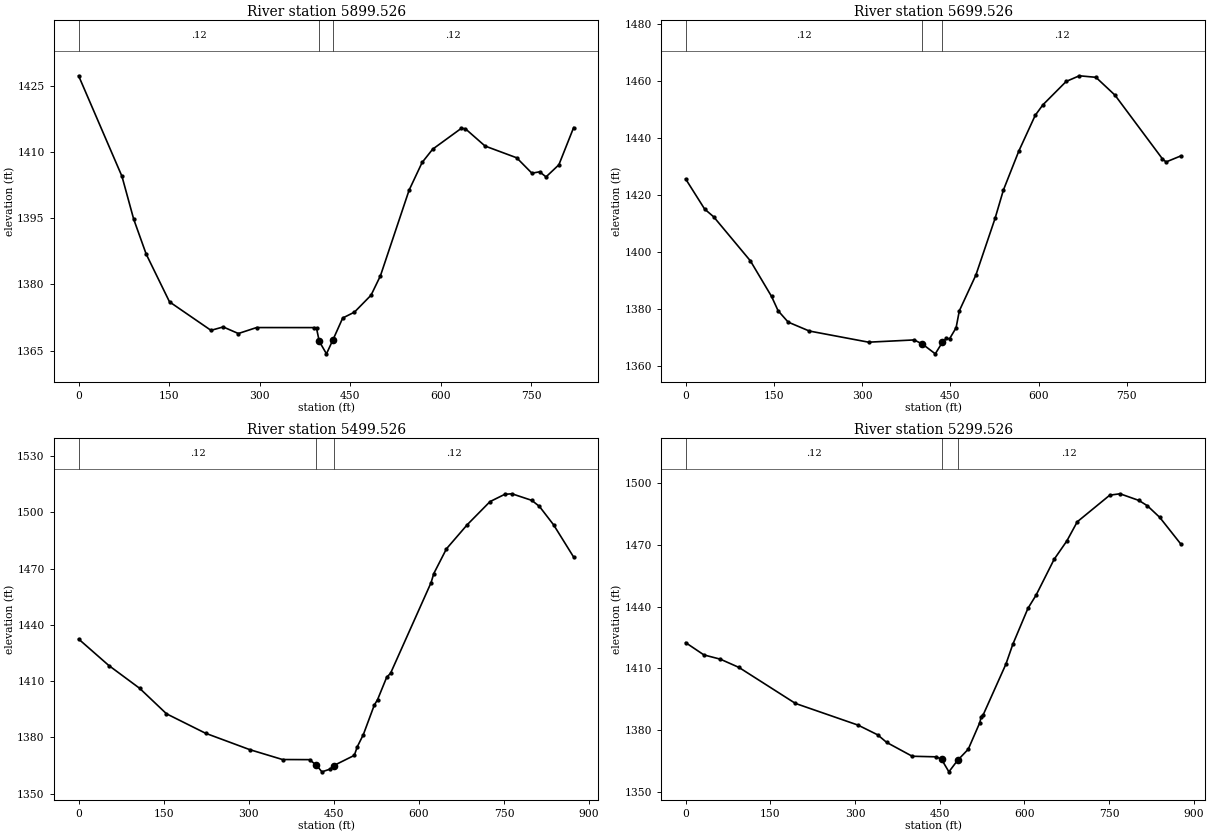
Type RM Length L Ch R = 1 ,5899.526,197.44,200,199.29
XS GIS Cut Line= 3
  1070064.132023   698099.647818   1070203.98081   697713.680048
  1070349.980234   697331.223881
#Sta/Elev= 30
       0 1427.25   71.82 1404.48   91.22 1394.79  111.93 1386.87  150.57 1376.06
  219.24 1369.61  239.48 1370.38  264.58 1368.89  294.76 1370.24  389.79 1370.23
  394.07 1370.06  398.62 1367.11  410.52 1364.29  421.37  1367.5  437.42  1372.4
  456.83 1373.73  484.37 1377.57   499.9 1381.96  547.41 1401.36  568.94 1407.62
  586.42 1410.63  634.08 1415.37   640.7 1415.24  673.22 1411.34  725.59 1408.68
  750.79 1405.19  763.66 1405.51  774.18 1404.35  795.46  1407.1   819.9 1415.52
#Mann= 3 , 0 , 0
       0     .12       0  398.62     .05       0  421.37     .12       0
Bank Sta=398.62,421.37
Exp/Cntr=0.3,0.1

Type RM Length L Ch R = 1 ,5699.526,198.12,200,202.99
XS GIS Cut Line= 3
  1070127.109542   698127.609498  1070385.729067   697791.068381
  1070498.744598   697389.475118
#Sta/Elev= 30
       0 1425.53   32.32 1414.96   47.66 1412.25   110.1 1396.79  146.07 1384.31
  157.27 1379.27  174.34  1375.3  210.16 1372.18  311.06 1368.26  388.37 1369.05
  402.45 1367.63  424.43 1364.17  436.59 1368.25  443.37  1369.6  448.76 1369.46
  459.81 1373.31  465.32 1379.26  493.51 1391.84  526.12 1411.72  540.26 1421.64
   566.4 1435.29  594.35 1447.85  607.41 1451.54  646.98 1459.74  669.35 1461.73
  697.54 1461.19  729.93 1454.94  810.49 1432.62   816.8 1431.49  841.63 1433.59
#Mann= 3 , 0 , 0
       0     .12       0  402.45     .05       0  436.59     .12       0
Bank Sta=402.45,436.59
Exp/Cntr=0.3,0.1

Type RM Length L Ch R = 1 ,5499.526,203.22,200,197.13
XS GIS Cut Line= 3
  1070166.451884   698157.943406  1070508.759082    697899.51045
  1070808.720661   697572.558173
#Sta/Elev= 30
       0 1432.45   53.33 1418.33  107.49 1406.22  154.92 1392.62   223.7 1382.26
  301.65 1373.52  359.43 1368.25  407.02 1368.19  419.33 1365.18  428.91 1361.69
  443.33 1363.14  449.61    1365  485.99 1370.46   491.2 1375.02  501.98 1381.58
  521.19 1397.23  526.99 1400.16  542.91 1411.97  549.98 1414.27  621.29 1462.48
  626.11 1467.34  648.43 1480.52  685.16 1493.39  725.22 1505.67  751.19 1509.55
  763.87 1509.84  798.85 1506.33  812.33  1503.1  837.33 1493.28  872.61 1476.12
#Mann= 3 , 0 , 0
       0     .12       0  419.33     .05       0  449.61     .12       0
Bank Sta=419.33,449.61
Exp/Cntr=0.3,0.1

Type RM Length L Ch R = 1 ,5299.526,199.56,200,198.6
XS GIS Cut Line= 3
  1070424.398961   698367.955876  1070628.894561   697948.882073
  1070838.978062   697596.194942
#Sta/Elev= 30
       0 1422.52   32.39 1416.57    61.5  1414.5   94.39 1410.52   194.5 1393.07
  305.43 1382.56  339.99 1377.88  356.19 1374.17  401.35 1367.48   444.1  1367.2
  453.27 1365.99  466.31 1359.93  481.54 1365.45  500.56 1370.88  521.06 1383.78
  523.56 1386.71  527.25 1387.67  567.26 1412.09  579.44 1421.67  606.27  1439.1
  620.85 1445.59  652.64 1462.86  675.17 1471.76  693.66 1481.06  751.26 1493.96
  769.46 1494.63  802.99 1491.39     818 1488.79  839.66 1483.23  876.82 1470.37
#Mann= 3 , 0 , 0
       0     .12       0  453.27     .05       0  481.54     .12       0
Bank Sta=453.27,481.54
Exp/Cntr=0.3,0.1