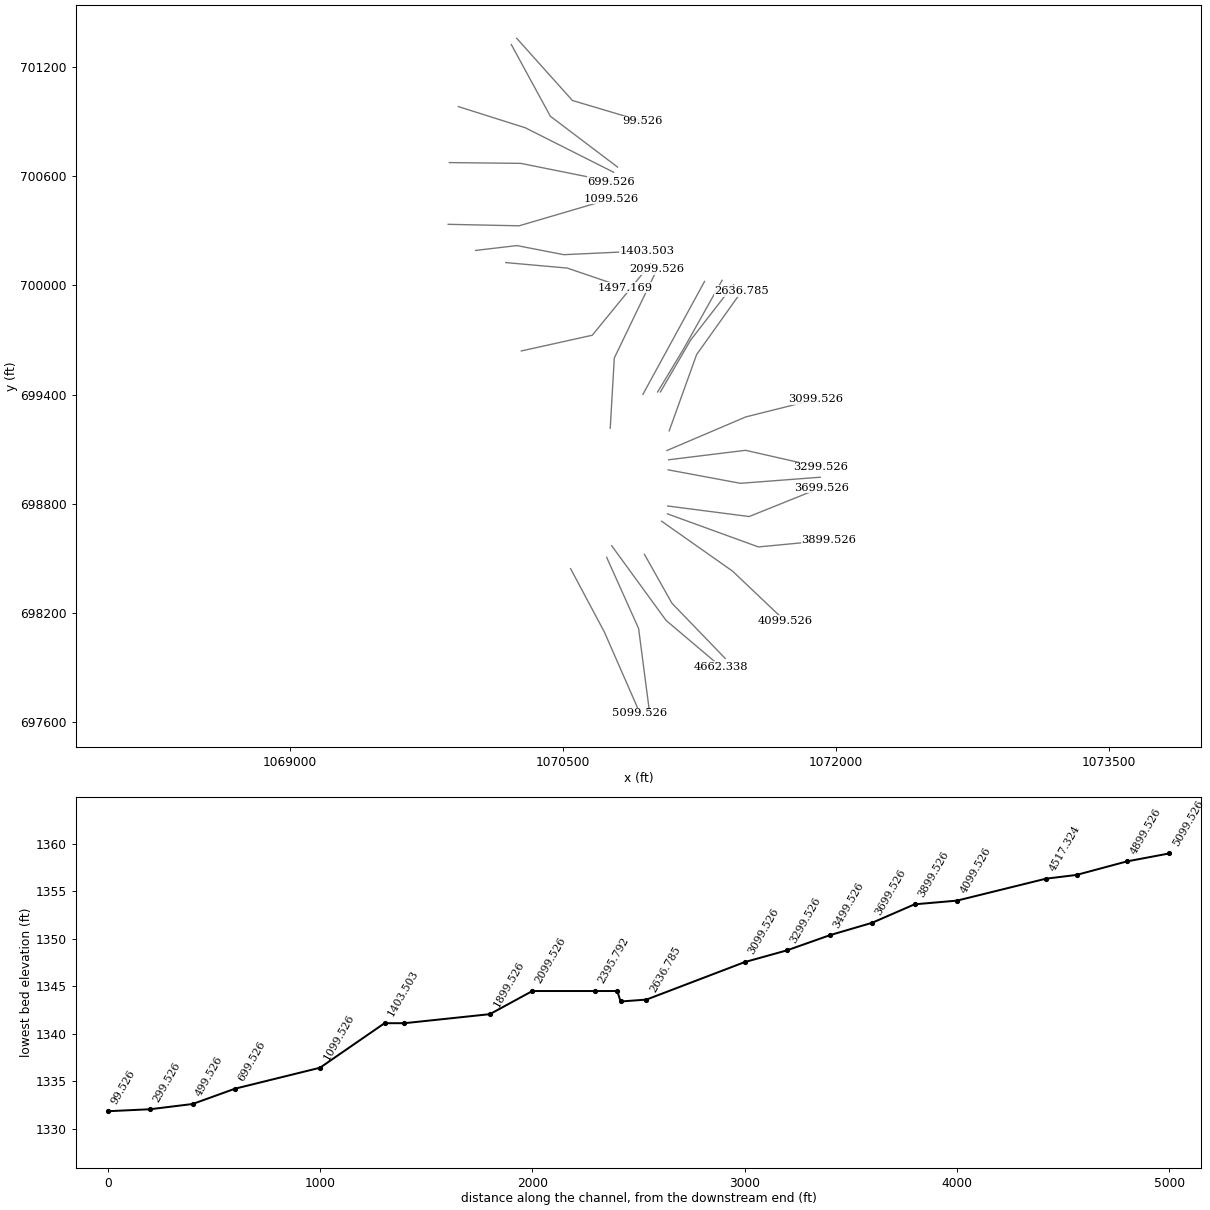
HEC-RAS study BrevardCreek.prj: Brevard Creek

--- BrevardCreek.g02 (geometry) --- (continued)

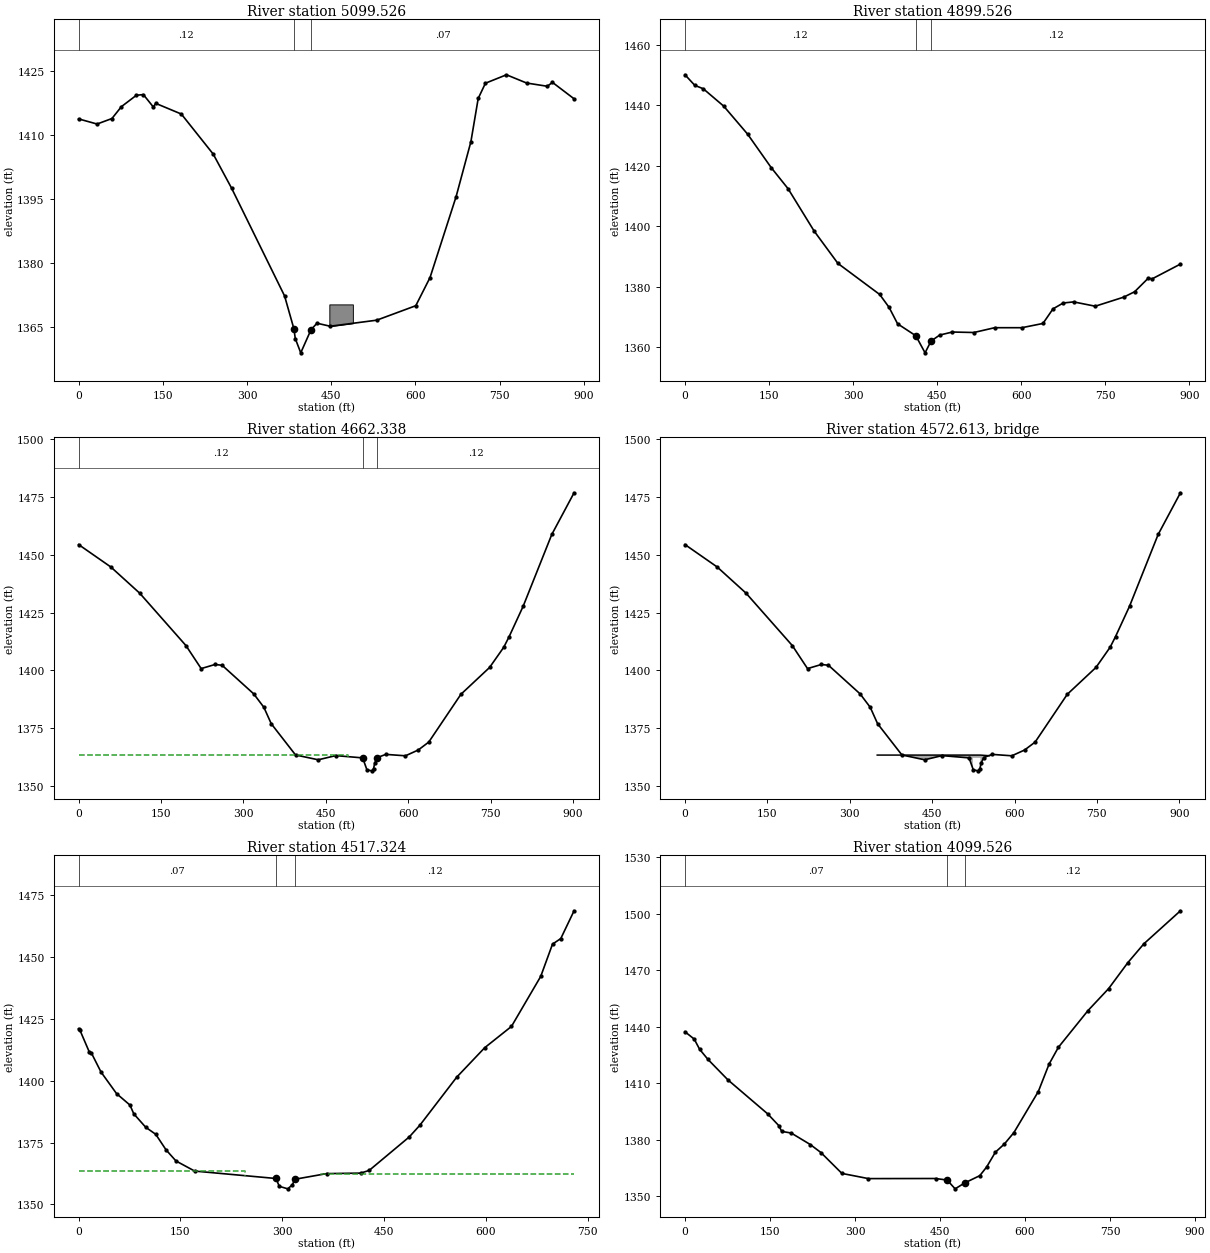
Type RM Length L Ch R = 1 ,5099.526,199.95,200,197.63
XS GIS Cut Line= 3
  1070543.644665    698444.20161  1070729.721094   698094.904371
  1070925.075285   697648.794859
#Sta/Elev= 30
       0 1413.77   32.87 1412.57   59.36 1413.86   76.21 1416.64  102.92 1419.31
  115.36 1419.47  133.12 1416.56  137.41 1417.41  183.02 1414.91  239.85 1405.52
  272.63 1397.52  366.97 1372.29  383.57 1364.59  386.04  1362.3  395.77 1358.96
  414.09 1364.39  424.75  1365.9  448.29 1365.19  531.13 1366.61  600.72    1370
  626.12  1376.6  672.59 1395.56  698.97 1408.45  711.96 1418.57  724.84 1422.13
  762.31 1424.11  798.15 1422.18  835.02 1421.42  844.26 1422.33  882.78 1418.48
#Mann= 3 , 0 , 0
       0     .12       0  383.57     .05       0  414.09     .07       0
#Block Obstruct= 1 ,-1
  446.71  488.65 1370.31
Bank Sta=383.57,414.09
Exp/Cntr=0.3,0.1

Type RM Length L Ch R = 1 ,4899.526,237.61,237.19,241.01
XS GIS Cut Line= 3
  1070741.995182   698506.074473  1070917.410427   698115.217387
  1070976.421998    697663.36929
#Sta/Elev= 30
       0 1450.03   17.49 1446.54    32.7  1445.4   69.11 1439.66  111.77  1430.4
  153.82 1419.35  183.96 1412.37  230.46 1398.37  272.89 1387.68  347.44 1377.41
  364.16 1373.16  379.35 1367.72  411.85 1363.77  428.41 1358.12  439.08 1362.02
  454.59    1364  477.15    1365  515.45 1364.84  552.64 1366.43  601.17 1366.43
  638.76 1367.83  656.68 1372.65  674.86 1374.59  693.47 1374.96   732.1 1373.53
  782.86 1376.53  802.39 1378.32  827.01 1382.86  833.36 1382.55   884.1 1387.46
#Mann= 3 , 0 , 0
       0     .12       0  411.85     .05       0  439.08     .12       0
Bank Sta=411.85,439.08
Exp/Cntr=0.5,0.3

Type RM Length L Ch R = 1 ,4662.338,143.79,145.01,144.93
XS GIS Cut Line= 3
  1070769.455448   698570.010857  1071068.393111   698159.526406
  1071369.425636   697904.828401
#Sta/Elev= 30
       0 1454.34   58.68 1444.66  111.17 1433.37  195.43 1410.75  223.12 1400.82
   248.4  1402.6  261.28 1402.25  318.88  1389.9  337.31 1384.11   350.7 1377.04
  394.95 1363.55  436.31 1361.47  468.15 1363.27   517.2 1362.29     525  1357.1
     534  1356.7     537  1357.7  539.34 1360.14  544.07 1362.45  559.35  1363.8
   595.1 1363.19  618.38 1365.69  637.57 1369.12  696.09 1389.73   748.3 1401.31
  774.15 1410.05  783.92 1414.63  809.39 1427.71  861.54  1458.7  902.12 1476.69
#Mann= 3 , 0 , 0
       0     .12       0   517.2     .05       0  544.07     .12       0
#XS Ineff= 2 , 0
       0     490  1363.4     588       0  1363.1
Permanent Ineff=
       F       F
Bank Sta=517.2,544.07
Exp/Cntr=0.5,0.3

Type RM Length L Ch R = 3 ,4572.613,,,
BEGIN DESCRIPTION:
37111-0194 Gravel Road
END DESCRIPTION:
Bridge Culvert--1,0,-1,-1, 0
Deck Dist Width WeirC Skew NumUp NumDn MinLoCord MaxHiCord MaxSubmerge Is_Ogee
60,12,2.6,0, 7, 6, , , 0.95, 0, 0,0,,
     350  515.34     524     524     538     538  554.51
  1363.5  1363.5  1363.5  1363.5  1363.5  1363.5 1363.22
                          1362.3  1362.3
     200     298     298     312     312     360
  1363.5  1363.1  1363.1  1363.1  1363.1 1362.12
                  1361.9  1361.9
BR Coef=-1 , 1 , 0 ,, 0 ,,,0.8,0,1.2,0,
WSPro=,,,, 1 ,,,, 0 ,,,, 0 ,,,,-1 ,-1 ,-1 , 0 , 0 , 0 , 0 , 0
BC Design=,, 0 ,, 0 ,,,,,,

Type RM Length L Ch R = 1 ,4517.324,414.4,417.8,418.12
XS GIS Cut Line= 3
   1070949.53806   698522.611761  1071100.390411   698254.234964
  1071393.324549   697950.776189
#Sta/Elev= 30
       0    1421    1.96 1420.42    15.6 1411.69   18.92 1411.15   32.97 1403.52
   55.86  1394.8   75.64 1390.15    81.2 1386.63   98.76  1381.2  113.55 1378.35
   128.8 1372.04   143.4 1367.56  170.94 1363.48  290.68 1360.48   295.5 1357.32
     308  1356.3  314.91 1357.98   318.4 1360.17  365.09 1362.45  415.32 1362.66
  427.91 1363.75  486.96 1377.29  502.48 1381.99  556.77 1401.43  597.99 1413.34
  637.45 1421.96  680.54 1442.18  697.89 1455.23  710.08 1457.48  729.65 1468.71
#Mann= 3 , 0 , 0
       0     .07       0  290.68     .05       0   318.4     .12       0
#XS Ineff= 2 , 0
       0     245  1363.4     357       0 1362.12
Permanent Ineff=
       F       F
Bank Sta=290.68,318.4
Exp/Cntr=0.5,0.3

Type RM Length L Ch R = 1 ,4099.526,197.93,200,206.35
XS GIS Cut Line= 3
  1071043.861868   698704.598161  1071433.696942   698430.356017
  1071722.026084   698156.646007
#Sta/Elev= 30
       0 1437.31   16.32 1433.43   25.79 1428.03   40.57 1422.64   75.85 1411.77
  146.06 1393.73  165.55 1387.52  170.61 1384.48  187.45  1383.6  220.98 1377.52
  239.79 1373.27  276.87 1362.18  323.64 1359.43  442.07 1359.48  462.56 1358.66
  476.63    1354  493.33  1357.1  520.16 1360.99  532.34 1365.62  547.65 1373.43
  563.66 1377.82  580.37 1383.85  623.43 1405.62  642.39 1420.16  658.87 1429.09
  711.12 1448.58  747.54 1460.24  781.37 1473.98  809.75 1484.01  874.19  1501.5
#Mann= 3 , 0 , 0
       0     .07       0  462.56     .05       0  493.33     .12       0
Bank Sta=462.56,493.33
Exp/Cntr=0.3,0.1

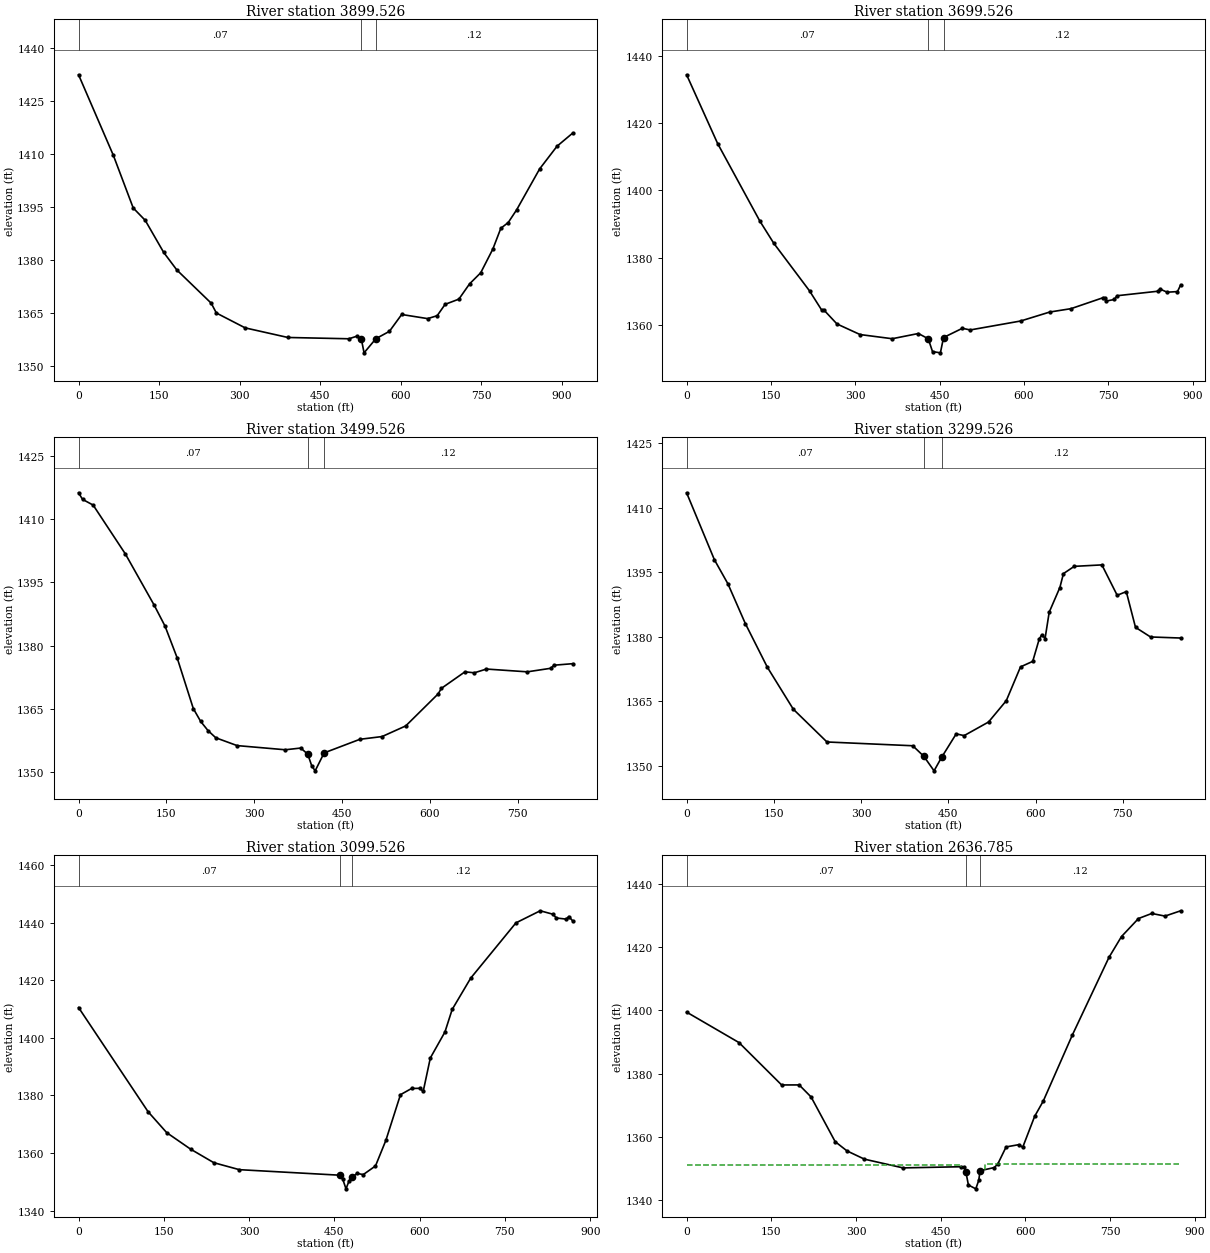
Type RM Length L Ch R = 1 ,3899.526,198.82,200,201.35
XS GIS Cut Line= 3
  1071076.016842   698745.007409  1071575.850732   698563.339194
  1071962.683073   698600.260684
#Sta/Elev= 30
       0 1432.51   64.84 1409.64  101.83 1394.71  124.21  1391.2  158.56 1382.11
  183.09 1377.12  247.02 1367.71  256.72 1364.91  310.41 1360.69  389.88 1357.97
   503.6  1357.6  518.16 1358.32  526.69 1357.58  531.82 1353.61  553.83 1357.62
  579.04 1359.71  601.91 1364.49   650.3 1363.32  668.03 1364.15   682.8 1367.37
  708.44 1368.85  728.31 1373.17  749.09 1376.32   771.7 1383.05  786.57 1388.95
  800.41 1390.59  815.96 1394.17  858.88  1405.8  891.29 1412.24  920.41 1415.96
#Mann= 3 , 0 , 0
       0     .07       0  526.69     .05       0  553.83     .12       0
Bank Sta=526.69,553.83
Exp/Cntr=0.3,0.1

Type RM Length L Ch R = 1 ,3699.526,198.2,200,197.97
XS GIS Cut Line= 3
  1071077.379525   698788.217094  1071524.965005   698730.298023
  1071921.415507   698889.863264
#Sta/Elev= 30
       0 1434.39   55.26 1413.91  130.18 1390.89  154.85 1384.31  218.61  1370.1
   240.3 1364.37  244.42 1364.36  267.42 1360.26  308.47 1357.11   365.6 1355.87
  412.13 1357.42  429.69 1355.86  437.31 1352.04  451.32 1351.67  456.91 1356.23
  490.36 1358.97  504.33 1358.48  594.05 1361.14  645.81 1363.81  683.55 1364.81
  741.29 1368.11  744.62 1367.94  746.49 1367.08  760.65 1367.55  765.45 1368.66
  838.64 1370.01  841.93 1370.64  854.54 1369.71  872.88 1369.89  878.67 1371.91
#Mann= 3 , 0 , 0
       0     .07       0  429.69     .05       0  456.91     .12       0
Bank Sta=429.69,456.91
Exp/Cntr=0.3,0.1

Type RM Length L Ch R = 1 ,3499.526,193.78,200,198.36
XS GIS Cut Line= 3
  1071079.714548    698986.94436  1071477.078283   698912.891897
  1071915.726049    698946.39134
#Sta/Elev= 30
       0 1416.22     6.8 1414.66   24.95  1413.3   79.92 1401.74   129.2  1389.6
  147.75 1384.63  168.32 1377.17  196.04 1365.11  208.59 1362.07  221.13  1359.9
  234.44 1358.19  270.84 1356.34  353.23 1355.35  379.68 1355.76  391.56  1354.3
  398.37 1351.54  404.21 1350.36  419.52 1354.61  480.61 1357.83  518.53 1358.48
  558.93    1361   614.2 1368.57  619.83 1369.89  660.13 1373.81  676.08 1373.58
  696.86 1374.47  766.62 1373.81  806.67 1374.65  812.24 1375.38  844.13 1375.74
#Mann= 3 , 0 , 0
       0     .07       0  391.56     .05       0  419.52     .12       0
Bank Sta=391.56,419.52
Exp/Cntr=0.3,0.1

Type RM Length L Ch R = 1 ,3299.526,201.17,200,202.68
XS GIS Cut Line= 3
  1071082.592424   699042.306886  1071504.909589   699094.245307
  1071918.532389   699000.434874
#Sta/Elev= 30
       0 1413.52   47.87 1397.91   71.02 1392.33  100.95 1383.08  138.81 1372.91
  183.47 1363.13  241.34  1355.5  388.87 1354.62  407.96 1352.16   425.5 1348.78
  438.33 1351.89   463.6 1357.39  477.22 1356.98  519.22 1360.15  549.69 1365.11
  574.16 1372.98  595.16 1374.27  606.37 1379.47  610.88 1380.49  616.39 1379.59
  623.51 1385.72  641.84 1391.46  647.99  1394.7  666.57 1396.39   714.1 1396.73
   740.4 1389.65  756.02 1390.51  771.89 1382.19  797.73 1379.95  849.63  1379.7
#Mann= 3 , 0 , 0
       0     .07       0  407.96     .05       0  438.33     .12       0
Bank Sta=407.96,438.33
Exp/Cntr=0.3,0.1

Type RM Length L Ch R = 1 ,3099.526,458.19,462.74,468.35
XS GIS Cut Line= 3
  1071073.220561   699093.136263  1071505.959874   699277.651129
  1071892.783748   699374.443984
#Sta/Elev= 30
       0 1410.52  122.29 1374.33  155.06 1367.06     197 1361.34  237.92 1356.62
  282.78  1354.2  460.06 1352.27  464.75 1350.89  470.43 1347.54  475.95 1350.35
  481.57 1351.62  489.89 1352.89  500.87  1352.5  522.33 1355.49  540.56 1364.37
  566.26 1380.24  585.76  1382.4  600.15 1382.46  606.28  1381.4  618.79    1393
  644.46 1402.01  657.19 1409.84  689.81 1420.73  769.38 1439.93  812.09 1444.13
  834.47 1442.93   840.5 1441.63  857.74 1441.23   862.4 1442.14  869.18 1440.62
#Mann= 3 , 0 , 0
       0     .07       0  460.06     .05       0  481.57     .12       0
Bank Sta=460.06,481.57
Exp/Cntr=0.5,0.3

Type RM Length L Ch R = 1 ,2636.785,123.95,121.67,118.68
XS GIS Cut Line= 3
  1071085.419967   699200.884369  1071236.144586   699620.292046
  1071485.167892   699969.798418
#Sta/Elev= 30
       0 1399.47    92.8 1389.83  168.22 1376.44  199.31 1376.45  220.42 1372.64
  263.03 1358.52  283.98 1355.59  314.89 1352.98  383.27 1350.22  485.84 1350.59
  491.36 1350.43  494.36 1349.03  498.94 1344.81     512  1343.6  517.18 1346.24
  519.63 1349.33   544.8 1350.33  550.95 1351.46  565.68 1356.85  588.02 1357.56
  595.11 1356.75  616.24 1366.52   631.5 1371.36  682.98 1392.23  747.75 1416.75
     770 1423.36  800.05 1429.05  823.57 1430.65  847.03 1429.82  874.82  1431.5
#Mann= 3 , 0 , 0
       0     .07       0  494.36     .05       0  519.63     .12       0
#XS Ineff= 2 , 0
       0     486  1351.1     528       0  1351.6
Permanent Ineff=
       F       F
Bank Sta=494.36,519.63
Exp/Cntr=0.5,0.3

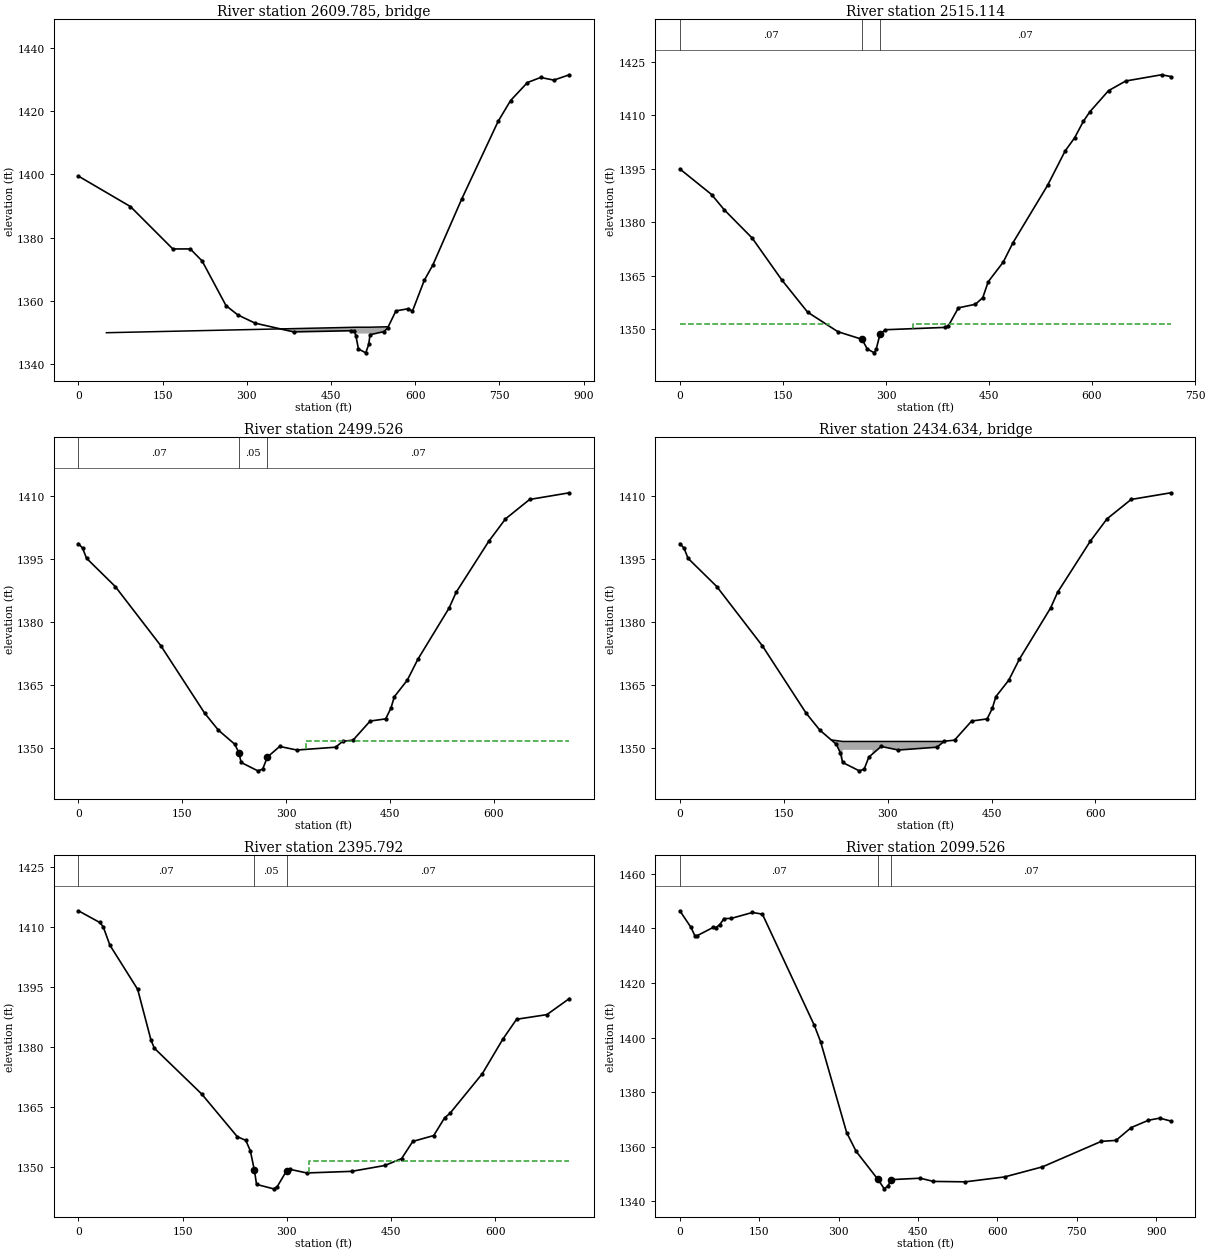
Type RM Length L Ch R = 3 ,2609.785,,,
BEGIN DESCRIPTION:
37111-0195 Gravel Road
END DESCRIPTION:
Bridge Culvert--1,0,-1,-1, 0
Deck Dist Width WeirC Skew NumUp NumDn MinLoCord MaxHiCord MaxSubmerge Is_Ogee
10,30,2.6,0, 6, 6, , , 0.95, 0, 0,0,,
   49.97     496     496     518     518   551.9
 1349.96  1351.7  1351.7  1351.7  1351.7 1351.85
                  1349.7  1349.7
  191.59     267     267     289     289     400
  1351.5  1351.5  1351.5  1351.5  1351.5  1351.5
                  1349.5  1349.5
BR Coef=-1 , 1 , 0 ,, 0 ,,,0.8,0,1.2,0,
WSPro=,,,, 1 ,,,, 0 ,,,, 0 ,,,,-1 ,-1 ,-1 , 0 , 0 , 0 , 0 , 0
BC Design=,, 0 ,, 0 ,,,,,,

Type RM Length L Ch R = 1 ,2515.114,28.35,15.59,15.93
XS GIS Cut Line= 3
  1071037.362832   699414.957003  1071203.378369    699700.02317
  1071439.295173    700004.09373
#Sta/Elev= 30
       0 1394.96   46.23 1387.78   64.57 1383.51  105.21 1375.59  148.45 1363.82
  185.98  1354.8  230.05 1349.32   265.1  1347.2  272.85 1344.47     283  1343.4
  285.77 1344.42   291.3 1348.61  299.22 1349.88   385.6 1350.53   390.9 1350.99
  405.46 1356.02  430.22 1357.02  440.95 1358.88   448.8 1363.33  470.61 1368.82
  484.89 1374.28  535.25 1390.37  560.84 1400.02   574.6 1403.69  587.33 1408.31
  596.75 1410.98  623.98 1416.92  649.09 1419.63  701.13 1421.37  714.74 1420.87
#Mann= 3 , 0 , 0
       0     .07       0   265.1     .05       0   291.3     .07       0
#XS Ineff= 2 , 0
       0     217  1351.4     339       0  1351.4
Permanent Ineff=
       F       F
Bank Sta=265.1,291.3
Exp/Cntr=0.5,0.3

Type RM Length L Ch R = 1 ,2499.526,87.43,103.73,106.71
XS GIS Cut Line= 3
  1071022.071913   699414.957003  1071162.917896   699648.626009
  1071376.401269   700028.777871
#Sta/Elev= 30
       0 1398.65    5.99 1397.56   11.82 1395.13    53.2 1388.42  119.07 1374.29
  182.13 1358.27  202.03  1354.2  225.85 1350.82  231.85 1348.73   234.9  1346.5
     259  1344.5     266  1344.9  272.78 1347.77  290.56 1350.31  315.39 1349.46
  371.19 1350.13   381.8 1351.55   396.5 1351.81  421.16 1356.36  443.57 1356.88
  451.05 1359.39  456.21 1362.19   474.8  1366.1  489.92 1371.04  535.16  1383.3
  545.35 1387.05  592.27 1399.16  616.56 1404.53  651.43 1409.16  708.83 1410.75
#Mann= 3 , 0 , 0
       0     .07       0  231.85     .05       0  272.78     .07       0
#XS Ineff= 2 , 0
       0     177  1351.8     328       0  1351.7
Permanent Ineff=
       F       F
Bank Sta=231.85,272.78
Exp/Cntr=0.5,0.3

Type RM Length L Ch R = 3 ,2434.634,,,
BEGIN DESCRIPTION:
37111-1011  Paved Drive
END DESCRIPTION:
Bridge Culvert--1,0,-1,-1, 0
Deck Dist Width WeirC Skew NumUp NumDn MinLoCord MaxHiCord MaxSubmerge Is_Ogee
58,13,2.6,0, 7, 6, , , 0.95, 0, 0,0,,
     219     235     235     278     278  298.03   381.8
 1351.86  1351.5  1351.5  1351.5  1351.5  1351.5  1351.5
                  1349.5  1349.5
     200     257     257     300     300  457.48
  1351.5  1351.5  1351.5  1351.5  1351.5 1351.51
                  1349.5  1349.5
BR Coef=-1 , 1 , 0 ,, 0 ,,,0.8,0,1.2,0,
WSPro=,,,, 1 ,,,, 0 ,,,, 0 ,,,,-1 ,-1 ,-1 , 0 , 0 , 0 , 0 , 0
BC Design=,, 0 ,, 0 ,,,,,,

Type RM Length L Ch R = 1 ,2395.792,292.8,296.27,296.39
XS GIS Cut Line= 2
  1070941.248561   699401.850539  1071279.832887   700022.224387
#Sta/Elev= 30
       0 1414.01   30.83 1411.08   35.73 1410.01    45.3 1405.42   85.32 1394.36
  104.57 1381.62  109.41 1379.64   177.5  1368.2  228.74 1357.53  240.93 1356.62
  247.44 1354.02  253.36 1349.11  256.43 1345.61     281  1344.5  286.18 1345.05
  299.72 1349.02   303.9  1349.4  328.71 1348.47  393.16 1348.87  441.15 1350.34
  465.23 1352.06  481.27 1356.35  511.44 1357.82  527.19 1362.27  534.77 1363.36
  581.42 1373.29  611.09 1381.96  630.74 1386.89  674.37 1388.05  706.76 1392.08
#Mann= 3 , 0 , 0
       0     .07       0  253.36     .05       0  299.72     .07       0
#XS Ineff= 2 , 0
       0     225  1351.4     332       0  1351.4
Permanent Ineff=
       F       F
Bank Sta=253.36,299.72
Exp/Cntr=0.5,0.3

Type RM Length L Ch R = 1 ,2099.526,209.62,200,208.66
XS GIS Cut Line= 3
  1070761.576175   699215.896522  1070783.935545   699601.453173
  1071019.111511   700089.227001
#Sta/Elev= 30
       0 1446.49      21 1440.38   28.31 1437.36   32.29 1437.32   62.92 1440.39
   67.95 1440.32   75.24 1441.38   83.32  1443.6   97.25 1443.71  137.19 1445.87
   155.9 1445.25   254.1 1404.43  265.97 1398.41  315.13 1365.13  333.04 1358.24
  374.16 1347.98   386.2  1344.5  393.32 1345.62  399.51 1347.88  454.34  1348.4
  479.09 1347.22  539.32 1347.07  613.56 1348.87  685.13 1352.57   796.2 1361.91
  823.98 1362.27  852.83 1366.98  885.39 1369.66  906.56 1370.43  927.71 1369.36
#Mann= 3 , 0 , 0
       0     .07       0  374.16     .05       0  399.51     .07       0
Bank Sta=374.16,399.51
Exp/Cntr=0.3,0.1

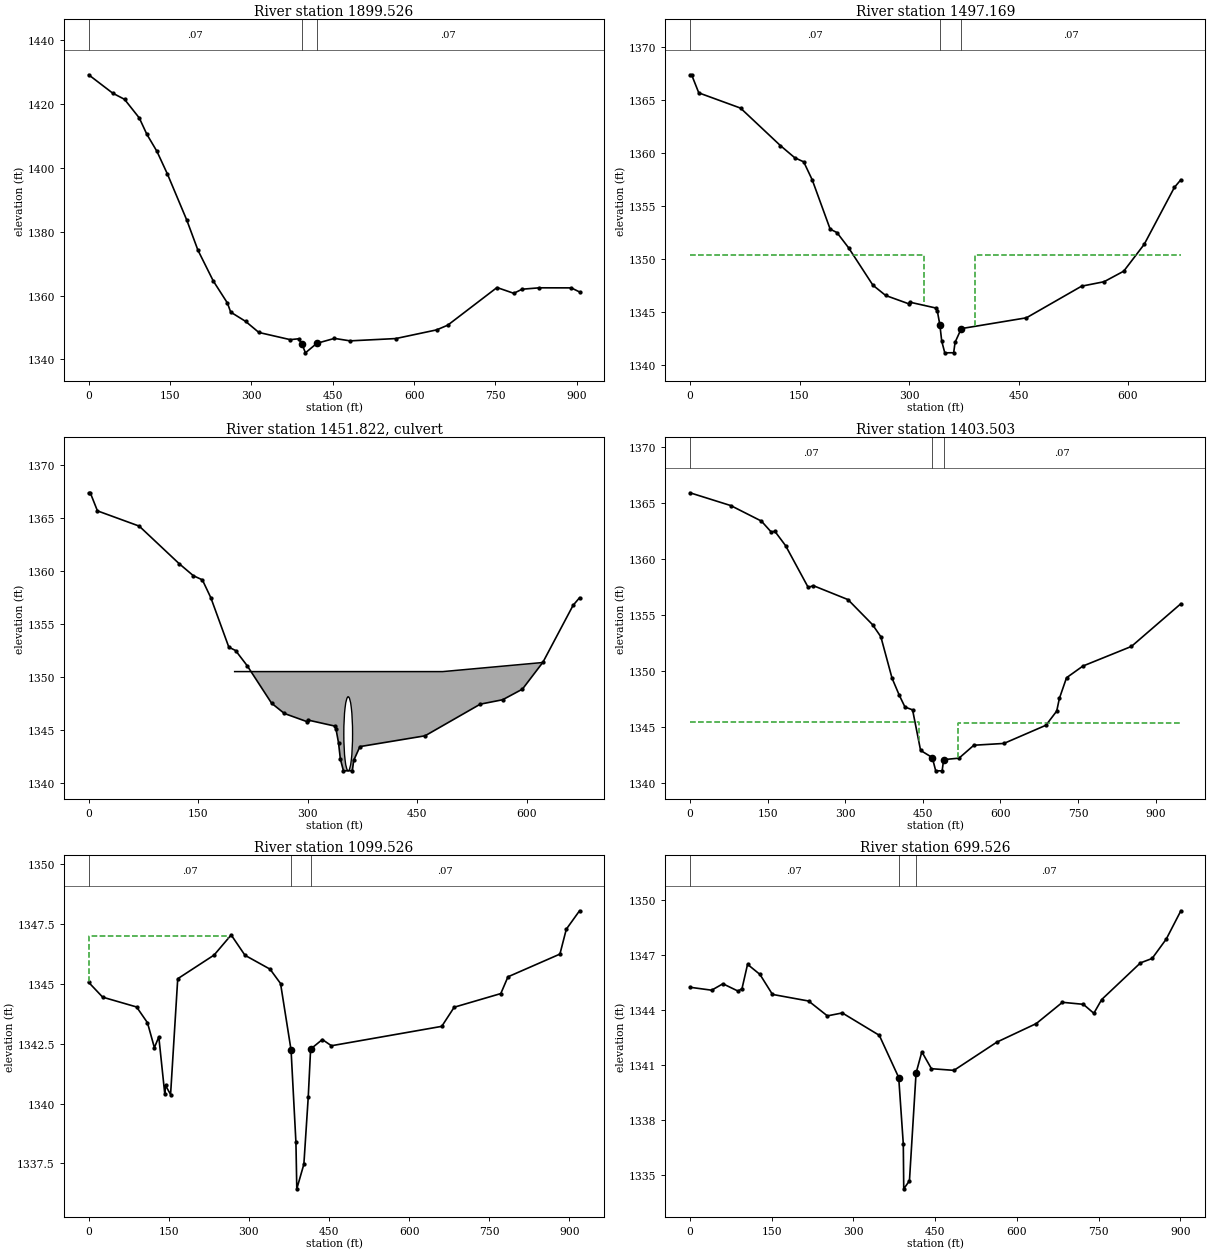
Type RM Length L Ch R = 1 ,1899.526,407.13,402.36,381.26
XS GIS Cut Line= 3
  1070273.033041   699640.135688  1070662.840464   699726.538319
  1070982.762621   700118.127234
#Sta/Elev= 30
       0 1429.13    44.4 1423.37   66.12 1421.45    93.3 1415.62  107.32 1410.49
   125.9 1405.15  145.28 1398.03  181.14 1383.53  201.44 1374.22  229.77 1364.57
   255.8 1357.67  261.85 1354.82  289.27 1351.93  313.83 1348.45  371.56  1346.2
  387.05 1346.47  393.46 1344.75  399.64 1342.07  420.66 1345.05  453.06 1346.59
  481.97 1345.82  566.12 1346.54  641.54 1349.26  661.97 1350.73  752.77 1362.52
  783.73 1360.71  799.04 1361.99  830.77 1362.43  889.61 1362.41  904.93 1361.14
#Mann= 3 , 0 , 0
       0     .07       0  393.46     .05       0  420.66     .07       0
Bank Sta=393.46,420.66
Exp/Cntr=0.5,0.3

Type RM Length L Ch R = 1 ,1497.169,94.92,93.67,92.31
XS GIS Cut Line= 3
  1070187.603062   700125.710497  1070524.970146   700095.626772
  1070840.848916   699988.185044
#Sta/Elev= 30
       0  1367.4    2.45 1367.36   12.05 1365.69   69.25 1364.25  123.96  1360.7
  143.47 1359.56  155.76 1359.17  167.42 1357.47     192 1352.81  201.26 1352.49
  217.22 1351.05  250.58 1347.51  268.07 1346.54  299.43 1345.76  301.01 1345.91
  337.15 1345.35  338.71  1345.1  342.25 1343.77  344.78 1342.23     349 1341.12
  361.17 1341.13  363.07 1342.11  371.58 1343.41  460.78 1344.43  536.37 1347.42
  567.14 1347.84  594.12 1348.84  622.18 1351.38  663.52 1356.76  672.36 1357.48
#Mann= 3 , 0 , 0
       0     .07       0  342.25     .05       0  371.58     .07       0
#XS Ineff= 2 , 0
       0     321  1350.4     391       0  1350.4
Permanent Ineff=
       F       F
Bank Sta=342.25,371.58
Exp/Cntr=0.5,0.3

Type RM Length L Ch R = 2 ,1451.822,,,
BEGIN DESCRIPTION:
37111-0182  Parker Padgett Road
END DESCRIPTION:
Bridge Culvert--1,0,-1,-1, 0
Deck Dist Width WeirC Skew NumUp NumDn MinLoCord MaxHiCord MaxSubmerge Is_Ogee
29,32,2.6,0, 8, 8, , , 0.95, 0, 0,0,,
     200     349   349.5   355.5   361.5  421.06     485     622
  1350.5  1350.5  1350.5  1350.5  1350.5  1350.5  1350.5 1351.36
                                                                
     378     475   475.5   481.5   487.5     571     726     852
  1350.5  1350.5  1350.5  1350.5  1350.5  1350.5 1351.36  1352.2
                                                                
BR Coef=-1 , 1 , 0 ,, 0 ,,,0.8,0,,0,
WSPro=,,,, 1 ,,,, 0 ,,,, 0 ,,,,-1 ,-1 ,-1 , 0 , 0 , 0 , 0 , 0
Culvert=9,7,12,32,0.024,0.5,1,60,1,1341.12,355.5,1341.12,481.5,Culvert #1  , 0 ,29
Culvert Bottom n=0.024
BC Design=,, 0 ,, 0 ,,,,,,

Type RM Length L Ch R = 1 ,1403.503,298.82,303.98,313.16
XS GIS Cut Line= 4
  1070021.851766    700192.51462  1070248.844837   700219.184803
  1070506.682668   700169.123645  1070963.869726   700190.388185
#Sta/Elev= 30
       0 1365.88   78.85 1364.74  138.02 1363.36  156.93 1362.39  164.07 1362.45
  184.82 1361.17  228.55 1357.45  238.36 1357.61  305.33 1356.37  352.81 1354.14
  368.93 1353.06  390.58 1349.37  404.67 1347.84  415.58  1346.8  430.27 1346.55
  445.76 1342.94  468.38  1342.3     475 1341.12  487.41 1341.12  490.32 1342.12
  520.08 1342.25  548.71  1343.4  606.79 1343.56  688.08 1345.18  708.87 1346.44
  714.06 1347.57  727.86 1349.41  759.47 1350.45  853.38  1352.2  948.89    1356
#Mann= 3 , 0 , 0
       0     .07       0  468.38     .05       0  490.32     .07       0
#XS Ineff= 2 , 0
       0  442.73 1345.45  518.83       0 1345.39
Permanent Ineff=
       F       F
Bank Sta=468.38,490.32
Exp/Cntr=0.5,0.3

Type RM Length L Ch R = 1 ,1099.526,398.59,400,393.21
XS GIS Cut Line= 3
    1069871.2395   700335.966004  1070260.853325   700327.799538
  1070768.707463   700477.036848
#Sta/Elev= 30
       0 1345.07   26.28 1344.45   89.77 1344.04  110.16 1343.38  123.08 1342.34
  131.35 1342.79  142.59 1340.39  143.95 1340.76  153.38 1340.38  166.78 1345.22
  234.87 1346.21  266.85 1347.05   292.7  1346.2  339.62 1345.62  359.28 1345.02
  378.96 1342.24  388.07 1338.38   389.7 1336.44  402.94 1337.47  411.14 1340.28
  415.56 1342.28  437.51 1342.68  454.51 1342.42  661.07 1343.23  684.37 1344.03
  771.64  1344.6  785.01  1345.3  882.31 1346.25  894.27 1347.29  919.03 1348.06
#Mann= 3 , 0 , 0
       0     .07       0  378.96     .05       0  415.56     .07       0
#XS Ineff= 2 , 0
          260.45    1347
Permanent Ineff=
       F       F
Bank Sta=378.96,415.56
Exp/Cntr=0.3,0.1

Type RM Length L Ch R = 1 ,699.526 ,202.22,200,197.98
XS GIS Cut Line= 3
  1069877.518257   700675.109337  1070269.785562   700670.919926
  1070768.396153    700570.62774
#Sta/Elev= 30
       0 1345.23   39.76 1345.07   60.42 1345.42   88.28 1345.02   95.49 1345.16
  105.64 1346.48  128.38 1345.93  151.34 1344.84  217.68 1344.48  252.12 1343.67
  279.51 1343.83  347.43 1342.61  383.05 1340.31  391.48 1336.68  392.29 1334.24
  402.76 1334.68   414.9 1340.55  425.51 1341.71  443.09 1340.79  484.44  1340.7
  563.23 1342.24  635.49 1343.25  683.51 1344.41  721.93  1344.3  741.16 1343.81
  755.54 1344.56  826.74 1346.56  848.12  1346.8  874.12 1347.86  900.89  1349.4
#Mann= 3 , 0 , 0
       0     .07       0  383.05     .05       0   414.9     .07       0
Bank Sta=383.05,414.9
Exp/Cntr=0.3,0.1

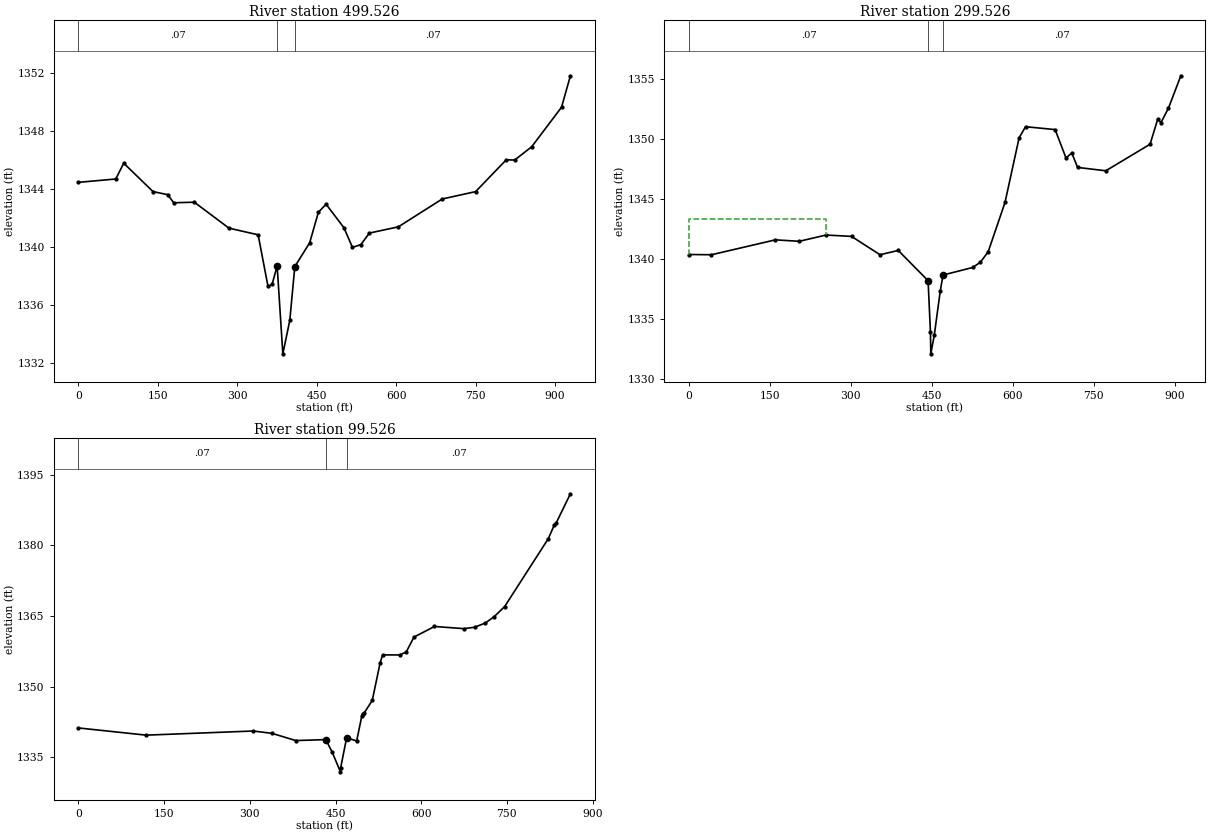
Type RM Length L Ch R = 1 ,499.526 ,205.24,200,199.42
XS GIS Cut Line= 3
  1069926.951202   700982.907585  1070294.915387   700866.447754
  1070779.872818   700622.125719
#Sta/Elev= 30
       0 1344.46   70.43 1344.69    85.5 1345.78  140.84 1343.82  168.43 1343.61
  179.99 1343.05  218.78 1343.09  284.21  1341.3  339.31 1340.84  357.94 1337.28
  365.71 1337.43  375.22 1338.69  385.95 1332.63  399.06 1334.93  408.57 1338.65
  436.63 1340.29  453.12  1342.4  467.62 1342.95  501.47 1341.32  517.42 1339.97
   533.5 1340.17  549.26 1340.96  604.08 1341.39  686.84 1343.31  749.98 1343.82
  807.72 1346.01  823.77    1346  855.79 1346.91  912.23 1349.64  928.98 1351.81
#Mann= 3 , 0 , 0
       0     .07       0  375.22     .05       0  408.57     .07       0
Bank Sta=375.22,408.57
Exp/Cntr=0.3,0.1

Type RM Length L Ch R = 1 ,299.526 ,197.61,200,201.26
XS GIS Cut Line= 3
  1070217.978991   701323.744951   1070432.37012    700929.99861
  1070801.863167   700650.433312
#Sta/Elev= 30
       0 1340.35   41.93 1340.33  160.35 1341.57  204.69 1341.45  254.08 1341.97
   301.4 1341.86  354.23 1340.33  388.01 1340.69  443.29 1338.17  447.67 1333.93
  448.33 1332.08  454.73 1333.61  465.87 1337.31     471 1338.64  525.99 1339.27
  540.37 1339.71  554.69 1340.58  585.91 1344.69  612.02 1350.07  623.92 1350.99
  678.75 1350.75  698.88 1348.39   709.6  1348.8  720.43  1347.6  772.65 1347.32
  854.67 1349.53  868.86 1351.62   874.9 1351.33  888.82 1352.54  911.67 1355.23
#Mann= 3 , 0 , 0
       0     .07       0  443.29     .05       0     471     .07       0
#XS Ineff= 2 , 0
          254.42 1343.33
Permanent Ineff=
       F       F
Bank Sta=443.29,471
Exp/Cntr=0.3,0.1

Type RM Length L Ch R = 1 ,99.526  ,99.526,99.526,99.526
XS GIS Cut Line= 3
  1070247.720492   701357.891288   1070553.83096   701016.325433
   1070939.66727   700901.635559
#Sta/Elev= 30
       0  1341.2  118.57 1339.67  306.03 1340.55  338.88 1340.05  380.31 1338.52
  432.96 1338.72  443.72 1336.17  458.66 1331.87  459.09 1332.78  469.47 1339.11
  487.01 1338.44  496.01 1343.73  497.41 1344.23  500.51 1344.45  514.34 1347.05
  527.98 1354.98  532.38 1356.73  562.48 1356.72  573.84 1357.36  587.34 1360.52
  623.27 1362.77   674.6 1362.31  693.41  1362.6  712.41 1363.52  727.66 1364.85
  746.05    1367  822.45 1381.43  832.75 1384.28  836.17 1384.75  861.18 1390.98
#Mann= 3 , 0 , 0
       0     .07       0  432.96     .05       0  469.47     .07       0
Bank Sta=432.96,469.47
Exp/Cntr=0.3,0.1

Chan Stop Cuts=-1
Use User Specified Reach Order=0
User Specified Reach Order=Brevard Creek   ,Main